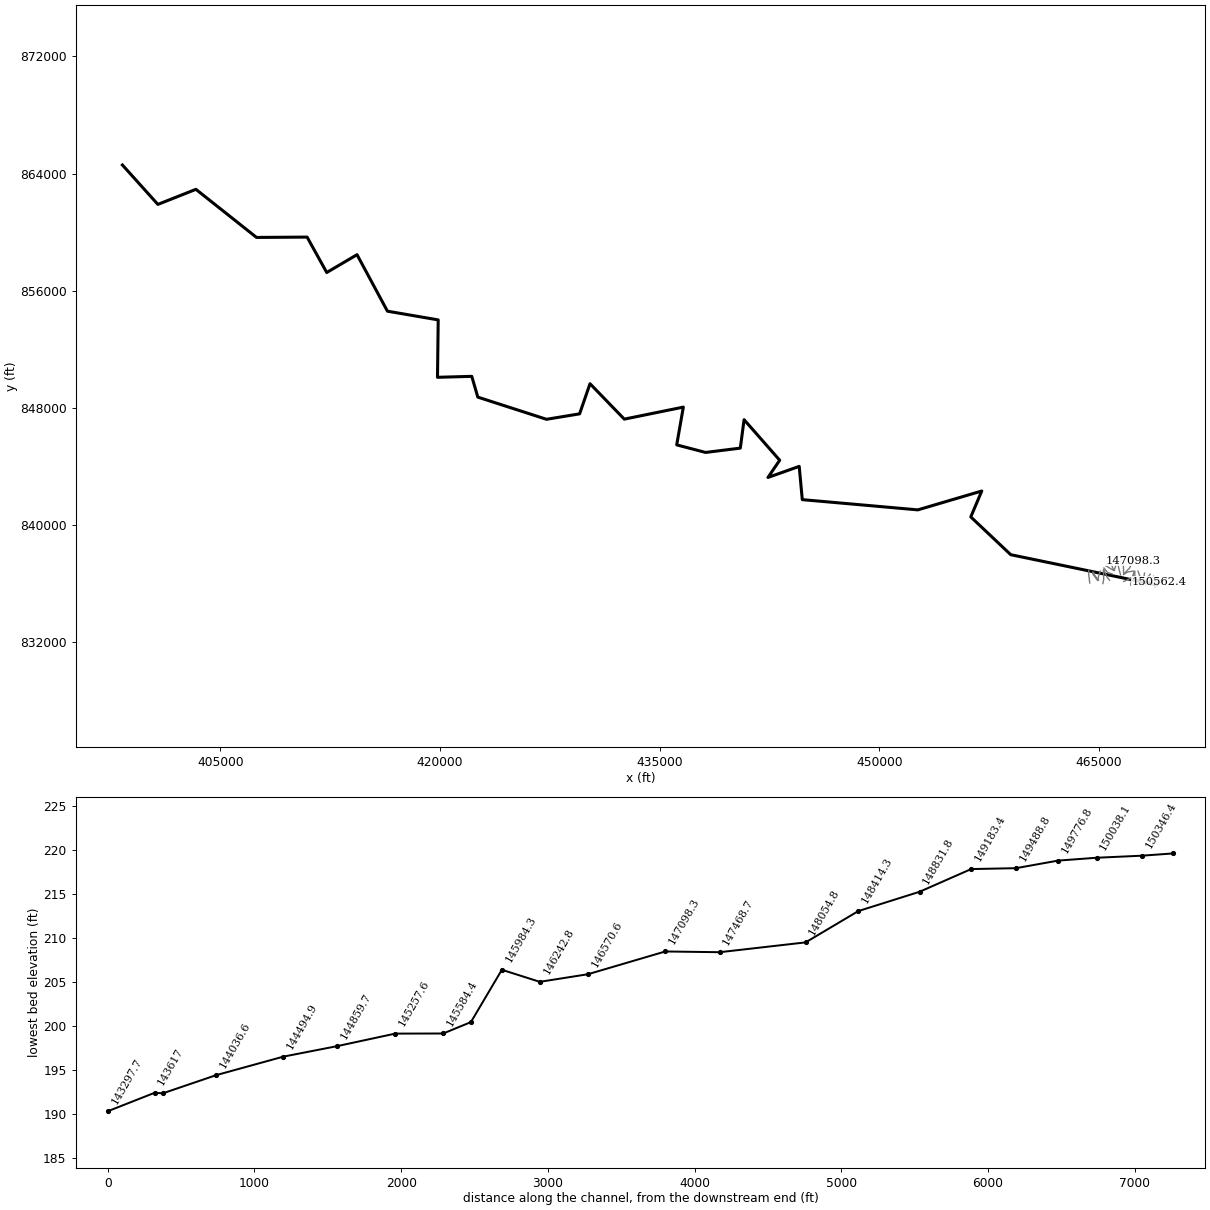
--- 7132_ras.prj (project) ---

Proj Title=7132
Current Plan=p01
Default Exp/Contr=0.3,0.1
English Units
Geom File=g01
Flow File=f01
Plan File=p01
Y Axis Title=Elevation
X Axis Title(PF)=Main Channel Distance
X Axis Title(XS)=Station
BEGIN DESCRIPTION:
RFD model 7132 exported to HEC-RAS
END DESCRIPTION:

--- 7132_ras.p01 (plan) ---

Plan Title=Plan 01
Program Version=4.10
Short Identifier=Plan 01
Geom File=g01
Flow File=f01
Subcritical Flow
Calc Critical at every XS
Secant Critical Depth

--- 7132_ras.f01 (steady flow) ---

Flow Title=Flow 01
Program Version=5.01
Number of Profiles= 6
Profile Names=10yr,25yr,50yr,100yr,100plus,500yr
River Rch & RM=7132,160,150562.4
 9749.7713627.1813945.3215719.8418648.3620520.25
River Rch & RM=7132,160,150346.4
 9755.0113634.03 13952.615727.9818658.0120530.45
River Rch & RM=7132,160,150038.1
 9763.4713645.0913964.3715741.12 18673.620546.91
River Rch & RM=7132,160,149776.8
10090.2914071.6614418.5416248.2719275.2321182.03
River Rch & RM=7132,160,149488.8
10100.6314085.14 14432.9 16264.319294.2521202.09
River Rch & RM=7132,160,149183.4
10121.69 14112.614462.1516296.9619332.9921242.96
River Rch & RM=7132,160,148831.8
10130.82 14124.514474.8416311.1219349.7921260.68
River Rch & RM=7132,160,148414.3
10141.3414138.2114489.4516327.4319369.1521281.09
River Rch & RM=7132,160,148054.8
10148.2914147.27 14499.1 16338.219381.9221294.57
River Rch & RM=7132,160,147468.7
 10158.214160.1914512.8716353.5819400.1621313.81
River Rch & RM=7132,160,147098.3
10232.8614257.4614616.5416469.3119537.4621458.59
River Rch & RM=7132,160,146570.6
10238.5914264.93 14624.5 16478.2   1954821469.71
River Rch & RM=7132,160,146242.8
10249.0714278.5814639.0416494.4419567.2621490.02
River Rch & RM=7132,160,145984.3
10253.4114284.2414645.0816501.1819575.2621498.45
River Rch & RM=7132,160,145773.3
 10254.414285.5314646.4516502.7119577.0721500.36
River Rch & RM=7132,160,145584.4
10289.3514331.0414694.9716556.8719641.32 21568.1
River Rch & RM=7132,160,145257.6
10293.4914336.4314700.7216563.2919648.9421576.13
River Rch & RM=7132,160,144859.7
10303.5514349.5314714.6916578.8819667.4321595.62
River Rch & RM=7132,160,144494.9
10999.3315253.5515679.7117655.7920944.9622940.61
River Rch & RM=7132,160,144036.6
11004.5215260.28 15686.9 17663.820954.4722950.61
River Rch & RM=7132,160,143672.9
11012.5815270.7415698.0817676.2820969.2722966.17
River Rch & RM=7132,160,143297.7
11020.26 15280.715708.7217688.1520983.3622980.98
River Rch & RM=7132,160,142390.8
11670.1816121.6616608.5418691.7322173.8924231.33
River Rch & RM=7132,160,141956.7
11699.0716158.9716648.5118736.2922226.7624286.79
River Rch & RM=7132,160,141801.9
11700.1916160.4216650.0718738.0322228.8224288.95
River Rch & RM=7132,160,141115.9
12502.0617193.6717758.2819973.3123694.2225824.17
River Rch & RM=7132,160,140830.4
 12504.817197.1917762.0619977.5223699.22 25829.4
River Rch & RM=7132,160,140341.2
 12523.617221.3717788.0220006.4523733.5425865.31
River Rch & RM=7132,160,139758.6
12529.2617228.6417795.8420015.1623743.8725876.11
River Rch & RM=7132,160,  139482
12532.9117233.3317800.8820020.7723750.5325883.08
River Rch & RM=7132,160,139106.2
12539.1117241.3117809.4420030.3123761.8525894.93
River Rch & RM=7132,160,138873.9
12541.1217243.8917812.21 20033.423765.5125898.76
River Rch & RM=7132,160,138619.4
12546.9617251.3917820.2720042.3823776.16 25909.9
River Rch & RM=7132,160,  138394
12548.9617253.9717823.0420045.4623779.8325913.73
River Rch & RM=7132,160,  138087
12561.9117270.6117840.9120065.3823803.4525938.45
River Rch & RM=7132,160,137988.3
12568.2917278.8117849.71 20075.2 23815.125950.63
River Rch & RM=7132,160,137738.1
 12571.217282.5617853.7420079.6823820.4225956.19
River Rch & RM=7132,160,137248.5
12576.3117289.1217860.7920087.5323829.7325965.93
River Rch & RM=7132,160,135955.2
12646.9217379.8617958.2720196.1523958.5826100.71
River Rch & RM=7132,160,  135125
12665.4617403.6817983.8620224.66 23992.426136.08
River Rch & RM=7132,160,134083.9
13238.8818139.2918774.8321105.7925037.6827228.29
River Rch & RM=7132,160,  132968
18900.33 25303.526538.5929738.1335278.1837842.41
River Rch & RM=7132,160,132028.5
18928.0725338.2226576.4629780.1635328.0437893.76
River Rch & RM=7132,160,130072.7
19033.7725470.4826720.7129940.3135518.0238089.37
River Rch & RM=7132,160,128712.9
 19079.225527.31 26782.730009.1335599.6638173.42
River Rch & RM=7132,160,127844.2
19089.0825539.6826796.19 30024.135617.42 38191.7
River Rch & RM=7132,160,126948.9
19102.3625556.29 26814.330044.2135641.2838216.26
River Rch & RM=7132,160,126801.3
19104.0625558.4126816.6230046.7835644.33 38219.4
River Rch & RM=7132,160,126218.4
19113.7825570.5726829.8930061.51 35661.838237.39
River Rch & RM=7132,160,125579.9
19129.2125589.8726850.9530084.8835689.5338265.93
River Rch & RM=7132,160,125102.5
19172.0825643.4926909.4430149.8135766.5638345.21
River Rch & RM=7132,160,124088.3
19809.9126440.2627779.2931115.2536911.8639523.24
River Rch & RM=7132,160,122855.9
19846.8726486.3827829.6731171.1636978.1839591.41
River Rch & RM=7132,160,121924.5
19857.2126499.2827843.7631186.7936996.7339610.48
River Rch & RM=7132,160,120666.5
19938.7726601.0327954.9331310.1637143.0739760.89
River Rch & RM=7132,160,119183.6
19954.2526620.3427976.0231333.5737170.8439789.43
River Rch & RM=7132,160,117117.2
20346.4427109.1928510.3731926.4637874.1940511.95
River Rch & RM=7132,160,116626.6
23828.0131423.43   3324237172.2244097.2146882.35
River Rch & RM=7132,160,  116065
 23841.331439.8133260.0337192.1944120.8946906.53
River Rch & RM=7132,160,115975.6
   2384231440.6833260.9937193.2544122.1646907.82
River Rch & RM=7132,160,115503.6
23861.5131464.7333287.4437222.5644156.92 46943.3
River Rch & RM=7132,160,114551.1
25703.2533729.7935782.3639985.69 47434.850283.86
River Rch & RM=7132,160,  113493
25729.4533761.9335817.8240024.9547481.3850331.25
River Rch & RM=7132,160,112471.7
25830.8733886.3535955.0640176.8947661.6250514.67
River Rch & RM=7132,160,111495.9
25869.6233933.8736007.4840234.9347730.4750584.72
River Rch & RM=7132,160,110404.9
25947.5934029.4836112.9840351.7147869.0250725.67
River Rch & RM=7132,160,  109074
25998.4334091.8136181.7540427.8547959.3450817.55
River Rch & RM=7132,160,107563.9
27574.2636020.0638311.8442785.2750755.9353659.09
River Rch & RM=7132,160,106887.7
   2758236029.5138322.2942796.8350769.6553673.01
River Rch & RM=7132,160,106789.6
27586.9436035.5438328.9642804.21 50778.453681.89
River Rch & RM=7132,160,106376.8
27595.3436045.8138340.3142816.77 50793.353697.02
River Rch & RM=7132,160,105905.4
27625.4936082.6238381.0242861.8250846.7453751.25
River Rch & RM=7132,160,103869.3
27643.3636104.4338405.1542888.5150878.4153783.39
River Rch & RM=7132,160,101450.7
27632.1536090.7638390.0242871.7850858.5553763.24
River Rch & RM=7132,160, 99346.7
28790.2637503.0839953.1944600.9752909.8955843.38
River Rch & RM=7132,160,97786.37
29002.3437761.3140239.2544917.35 53285.256223.61
River Rch & RM=7132,160,96436.55
29012.1537773.2540252.4844931.9853302.56 56241.2
River Rch & RM=7132,160,95805.05
29018.6937781.21 40261.344941.7353314.1356252.91
River Rch & RM=7132,160,95052.48
 29033.237798.8840280.8844963.3853339.8156278.93
River Rch & RM=7132,160,93981.39
29220.8538027.2440533.9345243.2353671.7956615.16
River Rch & RM=7132,160,92343.98
29235.4638045.0140553.62   4526553697.6356641.32
River Rch & RM=7132,160,90478.68
30915.7540085.6442817.5747767.9856666.8959644.87
River Rch & RM=7132,160,89527.33
30925.0640096.93 42830.147781.8256683.3259661.47
River Rch & RM=7132,160,88428.36
30940.7440115.9442851.2247805.16   5671159689.45
River Rch & RM=7132,160,87073.96
30980.7640164.45 42905.147864.7156781.6459760.83
River Rch & RM=7132,160,86493.45
31018.7340210.46 42956.2 47921.256848.6659828.53
River Rch & RM=7132,160,85980.43
31021.7840214.1742960.3247925.7556854.0559833.98
River Rch & RM=7132,160,85486.97
31063.6740264.9443016.7147988.0756927.9959908.68
River Rch & RM=7132,160,85180.15
31065.5840267.2543019.2847990.9256931.3659912.09
River Rch & RM=7132,160,85110.36
31065.8440267.5643019.62 47991.356931.8159912.54
River Rch & RM=7132,160,84651.43
31129.33 40344.543105.0948085.7557043.8660025.74
River Rch & RM=7132,160,83844.63
31151.8440371.7743135.3848119.2457083.5960065.87
River Rch & RM=7132,160, 83095.5
31159.9740381.6343146.3448131.3457097.9560080.38
River Rch & RM=7132,160,82249.01
31890.9141266.5944129.8749218.2558387.34 61382.3
River Rch & RM=7132,160, 81463.4
 31909.841289.4544155.2849246.3358420.6661415.91
River Rch & RM=7132,160,78996.69
31968.3441360.2744234.0249333.3458523.8761520.08
River Rch & RM=7132,160,77491.43
32002.9541402.1244280.5749384.7758584.8861581.64
River Rch & RM=7132,160,76642.97
32099.3741518.7444410.2549528.0758754.8861753.19
River Rch & RM=7132,160,75703.51
32125.6341550.4944445.5649567.0858801.1661799.88
River Rch & RM=7132,160,74615.35
32142.5841570.9944468.3649592.2858831.0561830.04
River Rch & RM=7132,160,73683.49
 32206.6 41648.444554.46 49687.458943.8961943.89
River Rch & RM=7132,160,72645.84
32239.7241688.44   4459949736.6159002.2762002.79
River Rch & RM=7132,160,71587.59
32251.8841703.1544615.3649754.6959023.7162024.42
River Rch & RM=7132,160,70784.43
32474.5641972.2844914.7650085.4859416.1362420.25
River Rch & RM=7132,160,70275.97
32502.8242006.4344952.7550127.4659465.9362470.47
River Rch & RM=7132,160,69119.48
 32514.742020.7844968.72 50145.159486.8662491.57
River Rch & RM=7132,160,68155.42
32542.3242054.1645005.8650186.1359535.5362540.66
River Rch & RM=7132,160,67571.77
32597.5342120.8645080.0950268.13 59632.862638.76
River Rch & RM=7132,160,66984.25
32603.5242128.1145088.1450277.0359643.3762649.41
River Rch & RM=7132,160,66433.45
32607.3942132.7845093.3450282.7859650.1962656.29
River Rch & RM=7132,160,65693.54
35316.2445396.6648730.7754299.84 64415.667454.26
River Rch & RM=7132,160,65373.24
 35321.245402.6348737.4254307.1864424.3267463.02
River Rch & RM=7132,160,65148.74
35322.2945403.9348738.88 54308.864426.2367464.95
River Rch & RM=7132,160,64655.49
35327.9845410.77 48746.554317.2164436.2167474.98
River Rch & RM=7132,160,64255.06
 35354.145442.1648781.5454355.89 64482.167521.12
River Rch & RM=7132,160,63247.34
 35402.745500.5648846.7354427.8664567.4767606.93
River Rch & RM=7132,160, 62198.8
35481.3445595.05 48952.254544.29 64705.667745.77
River Rch & RM=7132,160,60906.62
35547.2445674.2349040.5954641.8664821.3467862.11
River Rch & RM=7132,160,59782.91
 35565.745696.4149065.34 54669.264853.7767894.69
River Rch & RM=7132,160,59152.58
35568.3645699.5949068.9154673.1264858.4367899.38
River Rch & RM=7132,160, 58001.5
35621.5445763.4749140.2254751.8564951.8267993.23
River Rch & RM=7132,160, 56867.1
36096.14 46333.349776.5555454.2465785.0668830.41
River Rch & RM=7132,160,54947.44
37362.8447851.7551473.7357327.25   6800771060.77
River Rch & RM=7132,160,53677.99
 37386.547880.0851505.42 57362.268048.4771102.37
River Rch & RM=7132,160,51644.64
37435.5747938.8451571.1357434.7168134.4871188.65
River Rch & RM=7132,160, 50019.3
37629.5948171.0951830.9357721.3768474.5571529.71
River Rch & RM=7132,160,48861.35
37649.9948195.5151858.2557751.51 68510.371565.57
River Rch & RM=7132,160,48277.87
 37667.148215.9851881.1557776.7868540.2771595.63
River Rch & RM=7132,160, 47835.5
37671.5848221.3451887.1457783.3968548.13 71603.5
River Rch & RM=7132,160,47440.56
37674.8848225.2951891.5757788.2768553.91 71609.3
River Rch & RM=7132,160,46420.54
37800.0248375.0452059.1157973.12 68773.271829.19
River Rch & RM=7132,160,43981.02
39499.9850406.1454333.5760482.0571749.5374810.95
River Rch & RM=7132,160,41779.14
39536.6650449.8954382.6260536.1371813.6974875.18
River Rch & RM=7132,160,40674.92
39583.26 50505.554444.9360604.8671895.2274956.78
River Rch & RM=7132,160,38734.43
39605.3450531.8454474.4560637.4271933.8474995.44
River Rch & RM=7132,160,38352.54
39609.1650536.3854479.5560643.0571940.5275002.12
River Rch & RM=7132,160,37554.93
39668.44 50607.154558.8260730.4672044.22 75105.9
River Rch & RM=7132,160,36277.61
39685.88 50627.954582.1360756.1872074.7275136.44
River Rch & RM=7132,160,35608.38
39695.36 50639.2 54594.860770.1472091.2875153.02
River Rch & RM=7132,160,35238.95
39699.63 50644.354600.5160776.4472098.7675160.48
River Rch & RM=7132,160,34247.33
40255.3251306.7755343.2961595.5473070.45 76132.7
River Rch & RM=7132,160, 32404.5
40279.7851335.9255375.9861631.5973113.2276175.46
River Rch & RM=7132,160,26136.22
40368.1651441.2255494.0961761.82 73267.776329.98
River Rch & RM=7132,160,24737.85
40383.0751458.9855514.0161783.7973293.7776356.05
River Rch & RM=7132,160,20813.83
43157.7354757.4459218.3465867.1378137.8181194.46
River Rch & RM=7132,160,18810.24
43210.1154819.5859288.2165944.1378229.1681285.58
River Rch & RM=7132,160,16713.01
43227.0954839.7159310.8565969.0778258.75 81315.1
River Rch & RM=7132,160,15236.48
43237.2554851.77 59324.465984.0178276.4781332.77
River Rch & RM=7132,160,14674.81
43364.5555002.7559494.1966171.1278498.4481554.16
River Rch & RM=7132,160,13024.58
43382.9555024.5759518.7366198.15 78530.581586.16
River Rch & RM=7132,160,12819.79
43458.1955113.7859619.0666308.7178661.6681716.97
River Rch & RM=7132,160,10668.69
 44427.756262.5160911.5867732.8280351.0883401.12
River Rch & RM=7132,160,10496.69
44428.5956263.5560912.7667734.1380352.6383402.66
River Rch & RM=7132,160,6440.186
44490.9756337.41 60995.967825.7180461.2783510.93
River Rch & RM=7132,160,3873.648
44550.4556407.8361075.1767913.0580564.8883614.15
River Rch & RM=7132,160,2021.151
45058.1357008.5961751.6268658.2381448.8984494.74
River Rch & RM=7132,160,       0
45098.3257056.1361805.1668717.2181518.8584564.43
Boundary for River Rch & Prof#=7132,160,1
Up Type= 0
Dn Type= 2
Boundary for River Rch & Prof#=7132,160,2
Up Type= 0
Dn Type= 2
Boundary for River Rch & Prof#=7132,160,2
Up Type= 0
Dn Type= 2
Boundary for River Rch & Prof#=7132,160,2
Up Type= 0
Dn Type= 2
Boundary for River Rch & Prof#=7132,160,2
Up Type= 0
Dn Type= 2
Boundary for River Rch & Prof#=7132,160,2
Up Type= 0
Dn Type= 2

--- 7132_ras.g01 (geometry) ---

Geom Title=7132
Program Version=4.10

River Reach=7132,160
Reach XY= 30
468940.327901781835911.722743481458973.215165883837974.992849216
 456245.11247918840554.772426203 456995.36862874 842324.41739434
452630.008207262841035.501597151444739.903996319841733.939018071
444529.487244219844005.293017015442395.633238196843248.001306877
443197.016548276844425.029698014 440765.94562611847194.355668455
440508.306898713845252.168116987438136.952777416844956.334591255
436166.122168213845473.136954755436617.673395157848051.844280958
432586.079048306847231.135022089430246.327839136849650.084871233
429534.748029768847592.408170253427276.351948768847219.732645765
422584.227196395848734.248448014422172.745553911850153.101163238
419832.143863082850087.373448044419879.956363082854007.304003567
416413.636918634854601.910485059414337.484140843 858460.75076282
412269.254974216857243.216040611410928.809968382859660.451301068
407474.118400097859638.332360044403335.704050183862922.407023296
400739.340554267861893.196786508398318.164044678 864584.86005421

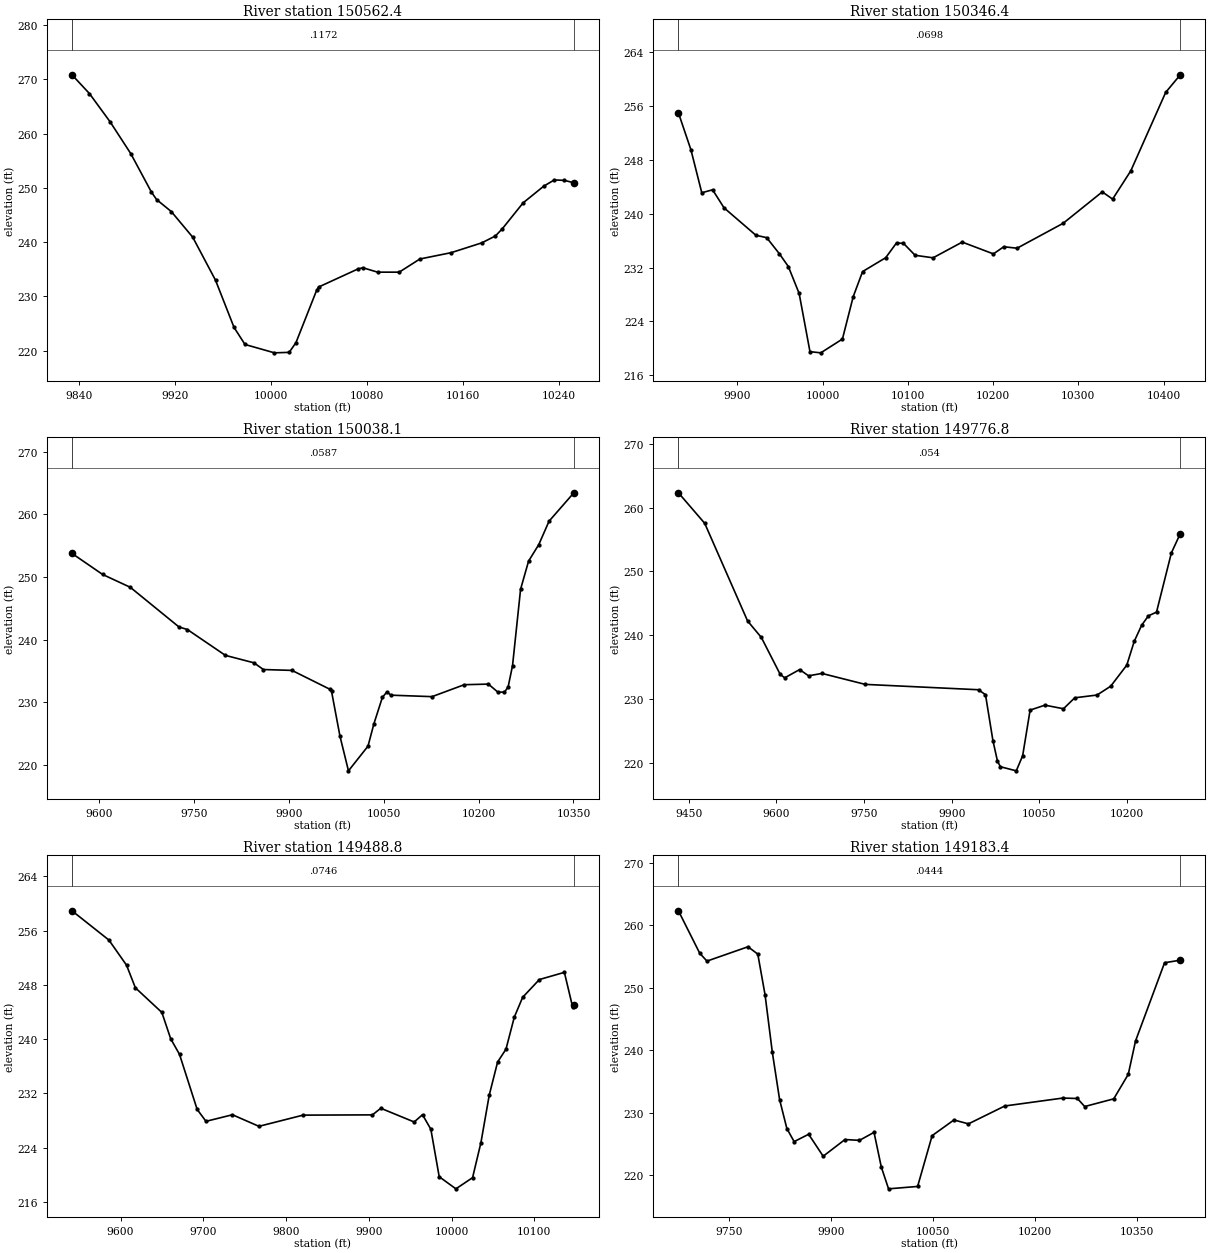
Type RM Length L Ch R = 1 ,150562.4,216.049000,216.049000,216.049000
XS GIS Cut Line= 2
468826.515223525 835787.53855399469069.570779081836128.250359546
#Sta/Elev= 30
9833.768270.82439848.378267.35749865.597262.15219882.816256.29719900.035249.2087
9904.352247.82889916.635245.61359934.474240.89699953.487232.96689968.912224.2784
9978.054221.128310002.62219.585310014.91219.674210020.57221.465410037.79231.1097
10039.47231.715410072.23235.037510076.32235.268110088.61234.453810106.67 234.454
10123.88 236.87710150.03 238.04710175.54239.852510186.88241.122310192.76242.4825
10209.98247.2229 10227.2250.300410236.01 251.44710244.42251.367410252.29250.9232
#Mann= 3 , 0 , 0
9833.768  0.1172       09833.768  0.1172       010252.29  0.1172       0
#XS Ineff= 2 , 0
       0                               0
Bank Sta=9833.768,10252.29
Exp/Cntr=0.3,0.1

Type RM Length L Ch R = 1 ,150346.4,308.260200,308.260200,308.260200
XS GIS Cut Line= 6
 468642.05341804835913.406609565468802.001950979836118.218755484
468849.451034158 836164.38675338468958.826034158836239.039531142
469016.117700815836265.081197798469082.089923054836277.233975589
#Sta/Elev= 30
9830.959255.01419845.669249.50139858.357243.12539871.045243.56749884.488240.8815
9921.798236.81079934.486236.45039949.476234.03879959.862232.1616 9972.55228.1535
9985.239219.50159997.927219.3257 10023.3221.375110035.99227.688610046.96231.4075
10074.06233.471110086.74235.666310094.92235.602810108.57233.827510129.62233.4553
10163.81235.790110200.37234.036810212.56235.098610228.11234.881410282.19238.5874
10328.04243.255710340.19 242.18210361.51246.3853 10402.4258.044610419.59260.6678
#Mann= 3 , 0 , 0
9830.959  0.0698       09830.959  0.0698       010419.59  0.0698       0
#XS Ineff= 2 , 0
       0                10319.09       0
Bank Sta=9830.959,10419.59
Exp/Cntr=0.3,0.1

Type RM Length L Ch R = 1 ,150038.1,261.376100,261.376100,261.376100
XS GIS Cut Line= 3
468203.617700815 835898.76175338468558.720084637836297.087165102
468719.242700815836501.192308918
#Sta/Elev= 30
9557.393253.7591 9605.94250.39799649.635248.35369726.512242.0339  9739.8241.6244
 9799.91237.50329844.992 236.316 9860.02235.24359905.102235.10699965.212232.0935
9967.655231.79169981.052 224.5999994.449219.092510025.32 223.02910034.64226.5897
10048.04230.806710055.38231.688310061.43231.156610126.53230.921110177.42232.8246
10215.59232.921410230.59 231.64410241.03231.642610246.77 232.45710253.76235.8607
10266.48248.041810279.12252.5302 10295.3255.172710311.47258.892810350.69263.4247
#Mann= 3 , 0 , 0
9557.393  0.0587       09557.393  0.0587       010350.69  0.0587       0
#XS Ineff= 2 , 0
       0                               0
Bank Sta=9557.393,10350.69
Exp/Cntr=0.3,0.1

Type RM Length L Ch R = 1 ,149776.8,287.954800,287.954800,287.954800
XS GIS Cut Line= 2
467967.140223563 835972.00035955468498.756589711836647.025642246
#Sta/Elev= 30
9432.105262.30879477.134257.52599550.483242.24179574.109239.64899606.435233.8632
9614.127233.33629639.585234.62549654.922233.65099677.772234.02279751.898232.3074
9945.849 231.4699957.806230.68769970.535 223.4949978.174 220.3429983.264219.4128
 10010.5218.770310021.45221.146410034.18228.280510059.64229.053810091.31228.4915
10110.55230.203610148.74230.640210172.12232.019410199.65235.314510212.38239.0338
10225.11241.565710236.78243.047610250.57243.619410276.03252.898510291.33  255.92
#Mann= 3 , 0 , 0
9432.105   0.054       09432.105   0.054       010291.33   0.054       0
#XS Ineff= 2 , 0
       09707.206                       0
Bank Sta=9432.105,10291.33
Exp/Cntr=0.3,0.1

Type RM Length L Ch R = 1 ,149488.8,305.373600,305.373600,305.373600
XS GIS Cut Line= 3
467951.881589741 836133.13675338468069.136751294836449.430915117
468103.858973533836716.357998431
#Sta/Elev= 30
9541.277258.91429585.925254.59959607.255250.8916 9617.92 247.5589649.915243.9258
 9660.58 240.0489671.245237.74239692.575229.6223 9703.24227.86499735.235228.8356
 9767.23 227.1289820.555228.77939904.391228.81869914.475229.79229954.812227.7704
9964.896228.8424 9974.98226.69539985.065219.697810005.23  217.91 10025.4219.5597
10035.49224.722810045.57231.751710055.65236.613510065.74238.500810075.82243.2311
10085.91246.155310106.08248.771610136.33249.835410146.41244.672410147.78244.9466
#Mann= 3 , 0 , 0
9541.277  0.0746       09541.277  0.0746       010147.78  0.0746       0
#XS Ineff= 2 , 0
       0 9667.39                       0
Bank Sta=9541.277,10147.78
Exp/Cntr=0.3,0.1

Type RM Length L Ch R = 1 ,149183.4,351.644800,351.644800,351.644800
XS GIS Cut Line= 2
467920.631589741836155.706197798467663.687145293836846.678420022
#Sta/Elev= 30
9676.031262.30239707.285255.51849717.954254.24959778.262256.54619792.637255.3657
9803.306248.84749813.975239.65649824.644232.08869835.313227.45949845.982225.3641
 9867.32226.53899888.658223.02519920.665225.69739942.003 225.5689963.341226.8481
 9974.01221.30959984.679217.808710027.36218.191410048.69226.3212 10080.7228.8293
10102.04228.206810155.38231.064710240.74232.335810262.07232.264310272.74230.9775
10315.42232.209110336.76236.125710347.43241.4629 10390.1253.990410413.23254.3951
#Mann= 3 , 0 , 0
9676.031  0.0444       09676.031  0.0444       010413.23  0.0444       0
#XS Ineff= 2 , 0
       0                10165.79       0
Bank Sta=9676.031,10413.23
Exp/Cntr=0.3,0.1

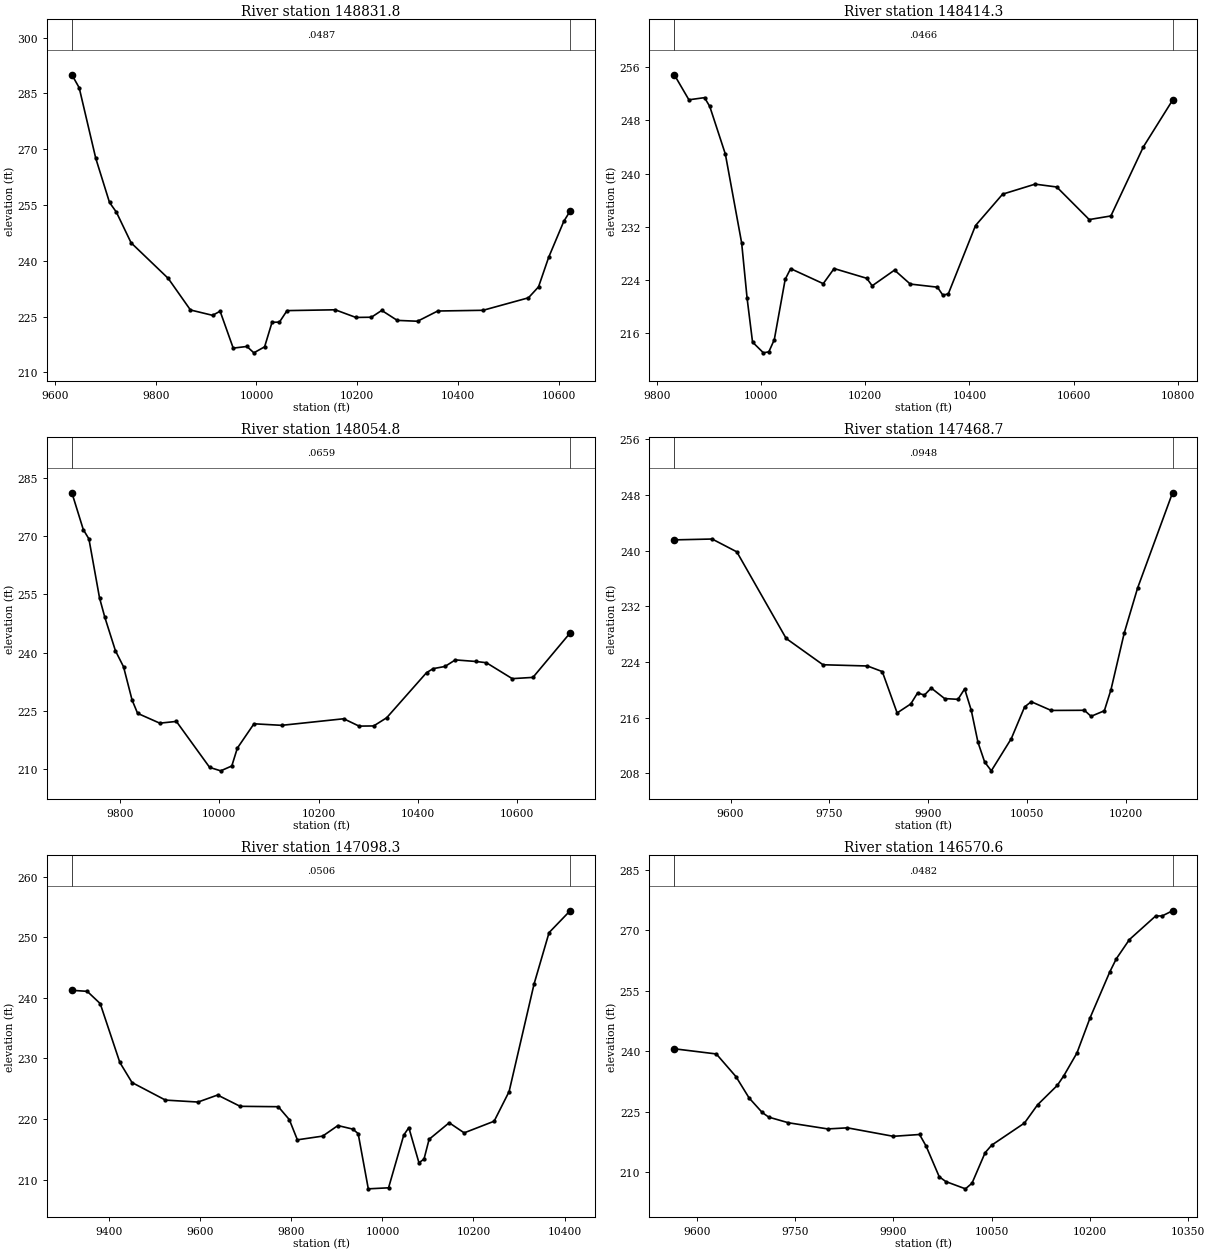
Type RM Length L Ch R = 1 ,148831.8,417.473900,417.473900,417.473900
XS GIS Cut Line= 6
467794.831195742835960.281609565467512.163368165836265.318833575
467497.020478606836294.595086709467476.187145263836364.039531156
467446.673256367  836494.2478645467444.937145263836827.581197813
#Sta/Elev= 30
9633.856290.0099 9648.32286.52759681.189267.55469708.456255.6823 9722.09253.0714
9751.307244.82169824.868235.26279869.006226.76129912.958225.31899927.855226.4292
9953.858216.50369981.125 216.9499994.759215.233110016.13 216.85310030.84223.4463
10045.55223.499510060.63226.589210156.17226.810410197.19224.751910227.95224.8101
10248.46226.637510279.22223.961210319.45223.729710359.45226.481610449.45226.6751
10539.45230.033510559.45232.978610579.45240.885410609.48250.569510622.11253.3643
#Mann= 3 , 0 , 0
9633.856  0.0487       09633.856  0.0487       010622.11  0.0487       0
#XS Ineff= 2 , 0
       0                10309.67       0
Bank Sta=9633.856,10622.11
Exp/Cntr=0.3,0.1

Type RM Length L Ch R = 1 ,148414.3,359.476500,359.476500,359.476500
XS GIS Cut Line= 4
467172.367700815835897.025642261467172.535735935835995.933882102
467313.774434596836469.709263757467411.951034158836818.900642246
#Sta/Elev= 30
9833.738254.86799861.713251.10569891.713 251.4289901.713250.11329931.713242.9293
9962.977229.55859973.412221.24479983.847214.659810004.72213.043610015.15213.2007
10025.59215.025810046.46224.088310056.89225.7078 10119.5223.449810140.37225.7226
10202.98224.256310213.41223.1264 10256.3225.486710286.46223.388510338.63222.9196
10349.07221.7107 10359.5221.919610411.68 232.18710463.69236.909910526.01238.4177
10567.56237.989310629.89233.088710671.44233.632910733.77244.022510789.76251.0405
#Mann= 3 , 0 , 0
9833.738  0.0466       09833.738  0.0466       010789.76  0.0466       0
#XS Ineff= 2 , 0
       0                10431.74       0
Bank Sta=9833.738,10789.76
Exp/Cntr=0.3,0.1

Type RM Length L Ch R = 1 ,148054.8,586.090300,586.090300,586.090300
XS GIS Cut Line= 6
466682.784367591836147.025642261466762.645478606836176.539531142
467122.020478606836355.358975589467280.006589711836489.039531156
467311.539837897836524.211231023467386.777423054836776.799947798
#Sta/Elev= 30
9702.838281.21779725.842271.71319737.183  269.319758.505254.12899769.166249.1281
9790.608240.4683 9806.97236.32099824.117227.77559835.286224.32279879.964 221.787
9913.473222.2407 9980.49210.380510002.83209.491110025.17210.747710036.34215.3484
10069.85221.626410125.69221.229110250.75222.925110281.72221.029210311.18221.0725
10337.38 223.18410417.77234.8271 10431.2235.858510454.83236.4122 10475.7 238.108
10517.44237.698310538.31237.381110590.48233.271910632.21233.597810707.13245.0599
#Mann= 3 , 0 , 0
9702.838  0.0659       09702.838  0.0659       010707.13  0.0659       0
#XS Ineff= 2 , 0
       0                10413.26       0
Bank Sta=9702.838,10707.13
Exp/Cntr=0.3,0.1

Type RM Length L Ch R = 1 ,147468.7,370.406600,370.406600,370.406600
XS GIS Cut Line= 6
466684.154112438836624.344109567466868.843070552836741.138074452
466975.319089711836795.897170022 467030.60855792836810.357492482
467149.798256377836828.015225576467387.645478586836857.529114487
#Sta/Elev= 30
9514.671241.56099572.028 241.6839609.448239.84069684.287227.39759740.114223.6199
9807.584223.44199830.074222.63699852.564216.69749873.265217.99019883.602219.5745
9893.938219.25789904.275220.2735 9924.62218.75919944.839218.65229954.948220.1503
9965.057217.05319975.166 212.4799985.275209.65249995.384208.377810025.71213.0072
10045.88217.563510055.96218.309310086.19217.055210136.57217.077810146.65216.2112
 10166.8217.007310176.88220.044210197.03228.203310217.18234.624210270.23 248.327
#Mann= 3 , 0 , 0
9514.671  0.0948       09514.671  0.0948       010270.23  0.0948       0
#XS Ineff= 2 , 0
       0                               0
Bank Sta=9514.671,10270.23
Exp/Cntr=0.3,0.1

Type RM Length L Ch R = 1 ,147098.3,527.735700,527.735700,527.735700
XS GIS Cut Line= 4
 466701.44756192836670.463142246467085.562145263837064.126336709
467196.673256427837291.556892246467316.464923054837557.181892261
#Sta/Elev= 30
 9317.77241.25889351.494241.08519379.995239.06079423.089229.34299449.854226.0206
9523.322223.11879594.917 222.7999637.874223.95819687.372222.09299771.202222.0286
9795.383219.90059813.117216.55819868.756217.17269902.144218.91449934.845218.3274
9946.663217.58579968.922208.460610013.44208.630510046.83217.341210057.96218.5722
10080.22212.760810091.35213.383310102.48216.641110146.62219.377810179.53217.7081
10245.35 219.63110278.26 224.53210333.11242.306110366.02250.787910412.29254.3955
#Mann= 3 , 0 , 0
 9317.77  0.0506       0 9317.77  0.0506       010412.29  0.0506       0
#XS Ineff= 2 , 0
       0                10135.77       0
Bank Sta=9317.77,10412.29
Exp/Cntr=0.3,0.1

Type RM Length L Ch R = 1 ,146570.6,327.780500,327.780500,327.780500
XS GIS Cut Line= 3
466679.162792981836710.932651207466673.235756367836947.806892246
466653.704506397 837470.81036447
#Sta/Elev= 30
9565.777240.60699629.865239.32529659.874233.70159679.881228.41979699.887224.8146
 9709.89223.65829739.899222.26339799.918220.73469829.938221.00429899.987218.9038
9940.015219.35389950.022216.47399970.036 208.8819980.042207.689710010.06205.8782
10020.07207.277910040.08214.840510050.09216.708310100.13222.195310120.14226.7207
10150.16231.521210160.17233.918710180.18239.5634 10200.2248.268210230.22259.6316
10240.22262.913710260.24267.683610300.27 273.53210310.27273.552910326.09274.8288
#Mann= 3 , 0 , 0
9565.777  0.0482       09565.777  0.0482       010326.09  0.0482       0
#XS Ineff= 2 , 0
       0                               0
Bank Sta=9565.777,10326.09
Exp/Cntr=0.3,0.1

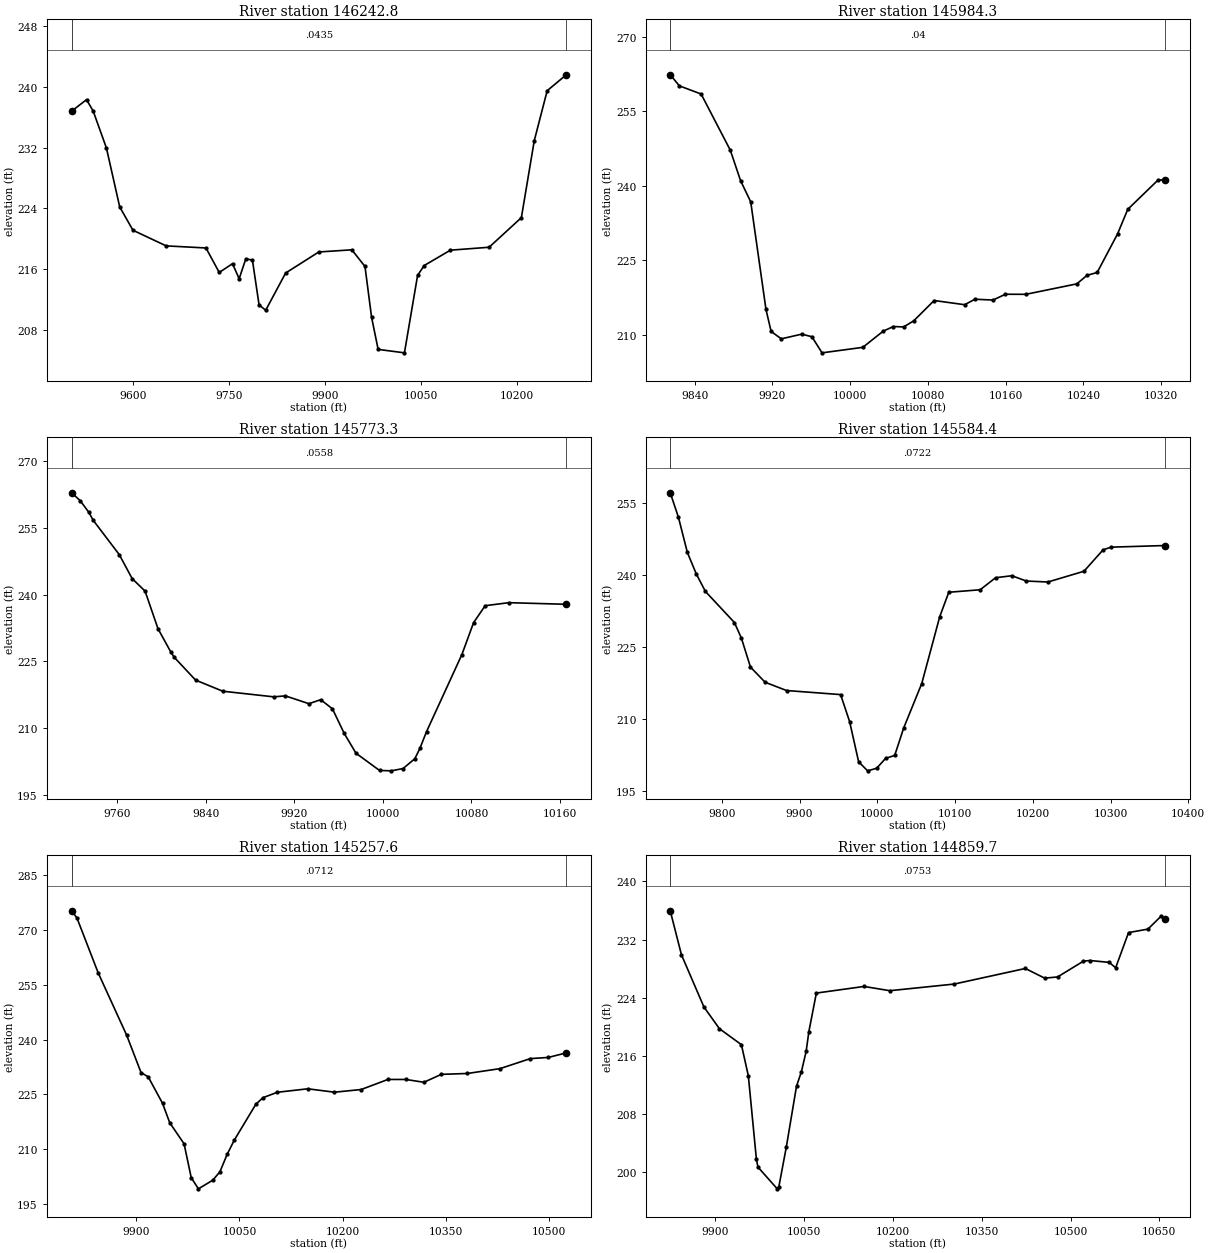
Type RM Length L Ch R = 1 ,146242.8,258.523100,258.523100,258.523100
XS GIS Cut Line= 4
466475.169737414836592.660081768466364.492654081836995.220845657
466325.430154081837160.151401212466301.558626303837344.613206768
#Sta/Elev= 30
9504.229236.80669527.398238.30819537.769 236.8149558.511231.94569579.254224.1994
9599.996 221.1359651.851 219.0829714.077218.80619734.819215.58689755.562216.7417
9765.933214.76229776.304 217.3719786.675 217.2219797.046 211.3279807.417210.6118
 9838.53215.50869890.385218.28069942.054 218.5649962.607 216.3789972.884209.7059
 9983.16205.470910024.27205.017310044.82215.1947 10055.1216.494410096.11218.5166
10156.61218.901210207.03222.793310227.19 232.91710247.36239.483210277.22241.5797
#Mann= 3 , 0 , 0
9504.229  0.0435       09504.229  0.0435       010277.22  0.0435       0
#XS Ineff= 2 , 0
       09732.435                       0
Bank Sta=9504.229,10277.22
Exp/Cntr=0.3,0.1

Type RM Length L Ch R = 1 ,145984.3,211.022300,211.022300,211.022300
XS GIS Cut Line= 2
466045.482237428836916.010776207466197.975339741837401.365920052
#Sta/Elev= 30
9814.903262.36359824.325260.13229846.656258.49159876.735 247.1669887.217241.0641
9897.699236.7776 9913.38 215.1319918.663 210.6989929.145209.20119950.109 210.146
9960.591209.63159971.073206.3842   10013207.489810033.96210.745310044.45211.6865
10054.93211.593310065.41212.832810086.37216.918810117.82216.0724 10128.3217.1768
10146.91217.014310159.75218.180910180.71218.164810233.12220.2687 10243.6221.9817
10254.09222.563610275.05230.326710285.53235.267310316.98241.228410323.65241.1404
#Mann= 3 , 0 , 0
9814.903    0.04       09814.903    0.04       010323.65    0.04       0
#XS Ineff= 2 , 0
       0                               0
Bank Sta=9814.903,10323.65
Exp/Cntr=0.3,0.1

Type RM Length L Ch R = 1 ,145773.3,188.896800,188.896800,188.896800
XS GIS Cut Line= 3
466033.044784158836908.310364485 465942.40064019 837057.72084567
465850.169737428837313.797234565
#Sta/Elev= 30
9718.773262.82819726.598261.01259734.283258.42719738.294256.62469761.687248.9811
9773.383243.5875 9785.08240.76239796.776232.31389808.472227.04689811.401225.9339
 9830.68220.81319855.258218.31269901.267217.05269911.895217.26329933.153215.5109
9943.782216.41619954.411214.3541 9965.04208.84379975.668204.40429996.926200.5366
10007.55200.448910018.18200.962810028.81203.155210033.41205.467210039.44209.2535
10071.33226.509610081.96233.705710092.43237.497310113.84238.174410165.71237.8104
#Mann= 3 , 0 , 0
9718.773  0.0558       09718.773  0.0558       010165.71  0.0558       0
#XS Ineff= 2 , 0
       0                               0
Bank Sta=9718.773,10165.71
Exp/Cntr=0.3,0.1

Type RM Length L Ch R = 1 ,145584.4,326.766300,326.766300,326.766300
XS GIS Cut Line= 2
466014.015223533836893.224317893465465.336450815837215.168003365
#Sta/Elev= 30
9733.637257.0299 9744.09251.98099755.684244.60779767.278240.08899778.873236.4976
9816.185230.0295 9825.25226.74099836.844220.74979855.705217.59079883.222215.8727
9952.788215.02589964.382209.39559975.976201.02849987.571199.15559999.165199.6923
10010.76201.772110022.35202.353110033.95208.084810057.14217.320510080.33231.2597
10091.92236.324610132.34236.8456 10152.1239.348810173.08239.764110191.62238.6606
10219.46238.460610265.84240.697910290.42245.157210300.62245.711110369.79246.0484
#Mann= 3 , 0 , 0
9733.637  0.0722       09733.637  0.0722       010369.79  0.0722       0
#XS Ineff= 2 , 0
       0                               0
Bank Sta=9733.637,10369.79
Exp/Cntr=0.3,0.1

Type RM Length L Ch R = 1 ,145257.6,397.867800,397.867800,397.867800
XS GIS Cut Line= 4
465892.419784158836667.858975574465833.782304734836681.849140793
465590.029014528836752.852465183465333.952625602837065.352465183
#Sta/Elev= 30
9806.361275.28449813.989273.30279844.831258.27239886.208241.19759907.039 230.975
9917.454229.81019938.286 222.5549948.701217.24479969.533211.47729979.948202.1857
9990.364199.143210011.19201.514410021.61203.816410032.03208.562310042.44 212.481
10073.69222.2852 10084.1224.107810104.94225.584810149.16226.537110187.95225.6056
10226.73226.340510265.52229.092310291.38229.095110317.79228.326310343.09 230.491
 10380.9230.732210428.23232.055910472.38234.806510498.23235.119410524.55236.3677
#Mann= 3 , 0 , 0
9806.361  0.0712       09806.361  0.0712       010524.55  0.0712       0
#XS Ineff= 2 , 0
       0                               0
Bank Sta=9806.361,10524.55
Exp/Cntr=0.3,0.1

Type RM Length L Ch R = 1 ,144859.7,364.798100,364.798100,364.798100
XS GIS Cut Line= 3
465716.041745961836230.058773041465545.902857065836448.808773041
465323.101931185836961.185798511
#Sta/Elev= 30
9823.521235.96379842.449229.91659880.455222.73059906.659219.74379943.798217.5467
9955.523213.26269969.136201.79089971.812200.705210004.39197.716110007.14198.0276
10019.81203.513610036.96211.842910045.15 213.80810053.25216.635910057.82219.3426
10070.48224.644610151.02225.554610194.63224.970310303.53225.883910423.63228.0262
10456.34226.696610478.15226.861710521.77229.031610532.67229.123210565.39228.8679
10576.29228.1203 10598.1232.965510630.81 233.43910652.62235.180410659.37234.7854
#Mann= 3 , 0 , 0
9823.521  0.0753       09823.521  0.0753       010659.37  0.0753       0
#XS Ineff= 2 , 0
       0                               0
Bank Sta=9823.521,10659.37
Exp/Cntr=0.3,0.1

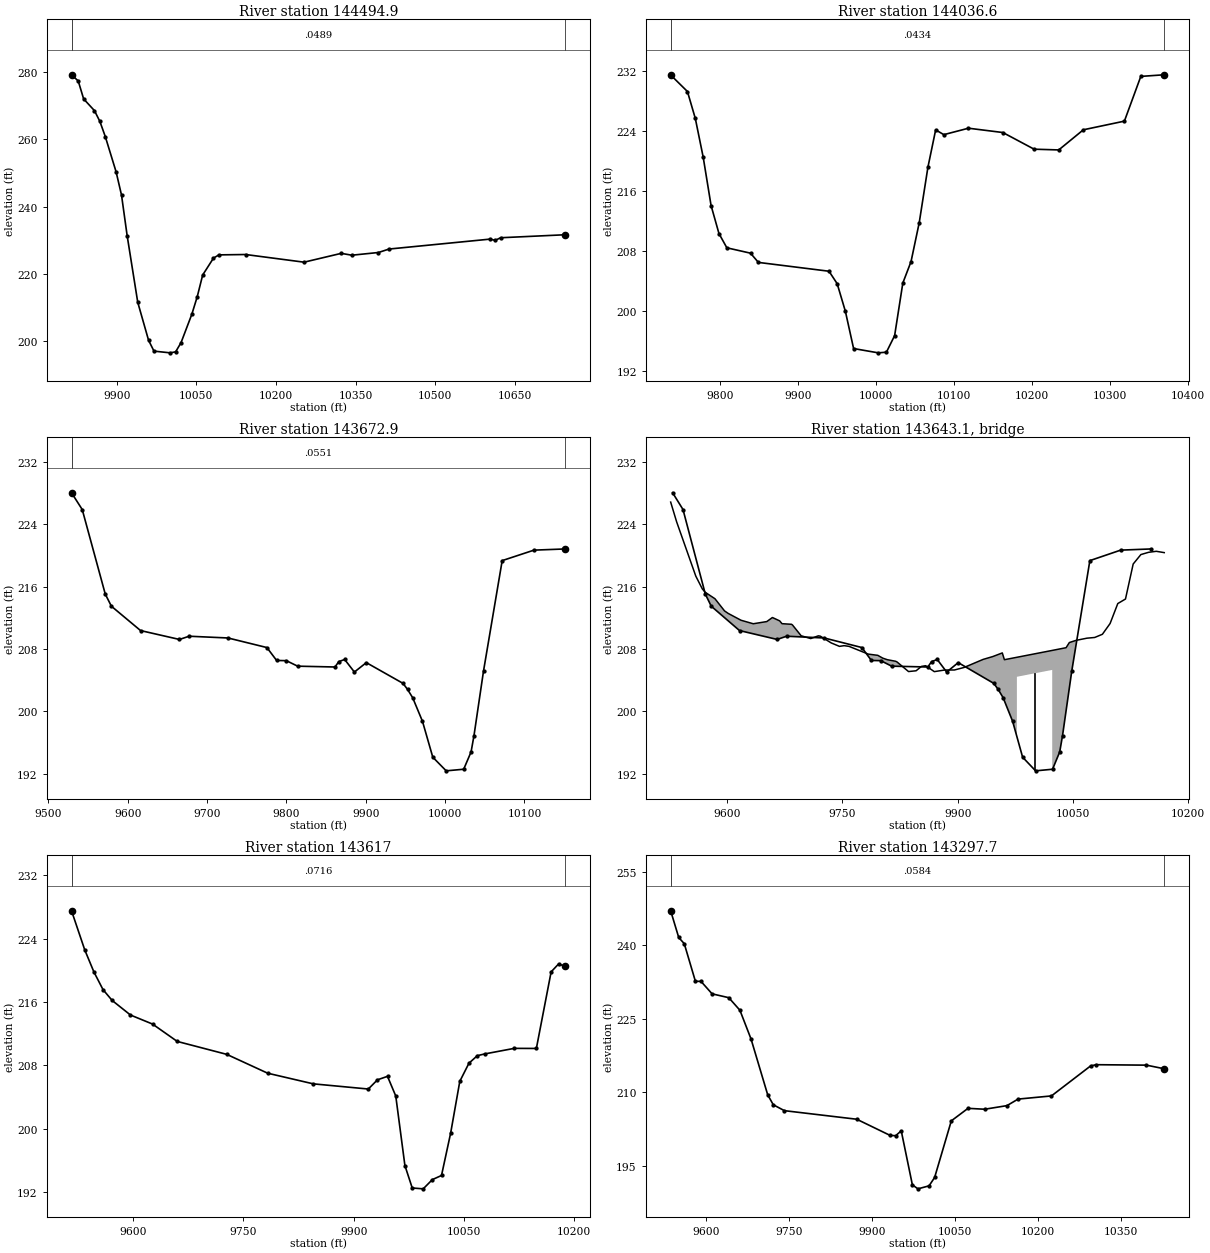
Type RM Length L Ch R = 1 ,144494.9,458.370900,458.370900,458.370900
XS GIS Cut Line= 3
465264.652857065836002.628217474465322.117977679836292.868166298
465299.230403364836926.463576272
#Sta/Elev= 30
  9814.9279.20059827.512277.35939837.706 272.0229858.094268.53539868.288265.3368
9878.482260.8376 9898.87250.34169909.065243.43829919.662231.39539939.647211.5616
9960.035200.26619970.229197.039410000.81196.531810011.01196.8273 10021.2199.5541
10041.59208.018410051.78213.244610061.98219.669410082.36224.701210092.56225.6554
10142.93225.7642   10253223.484310323.04226.107510343.06225.558510393.09226.3619
 10413.1  227.3910603.23230.338810613.23 229.98510623.24230.748510744.78 231.639
#Mann= 3 , 0 , 0
  9814.9  0.0489       0  9814.9  0.0489       010744.78  0.0489       0
#XS Ineff= 2 , 0
       0                               0
Bank Sta=9814.9,10744.78
Exp/Cntr=0.3,0.1

Type RM Length L Ch R = 1 ,144036.6,363.628300,363.628300,363.628300
XS GIS Cut Line= 6
464968.067208916836243.737881824464949.982718229836363.305300817
464949.982718229836403.235856399464953.454940498836437.958078608
464956.831245005 836449.35310638465089.594986737  836853.5469096
#Sta/Elev= 30
9736.387231.41949757.887229.22289767.999225.63719778.111220.47929788.223214.0379
9798.335210.31049808.446208.41359838.792207.69929848.911206.46989939.485 205.294
9949.969 203.6339960.495199.9549 9971.02195.0029 10002.6  194.4310013.12194.5147
10023.65196.721510034.17203.7234 10044.7206.578910055.23211.769610066.34 219.138
10076.28224.1111 10086.8223.477910118.38224.335410162.47223.761510202.58221.5427
10234.16221.443310265.74224.124810318.37225.276810339.42231.233110369.46231.4489
#Mann= 3 , 0 , 0
9736.387  0.0434       09736.387  0.0434       010369.46  0.0434       0
#XS Ineff= 2 , 0
       09806.315                       0
Bank Sta=9736.387,10369.46
Exp/Cntr=0.3,0.1

Type RM Length L Ch R = 1 ,143672.9,55.910400,55.910400,55.910400
XS GIS Cut Line= 4
464939.547630933836243.989653527464684.860130933836604.015695194
464627.308047599836673.546945194464631.735130933836764.171945194
#Sta/Elev= 30
9529.231228.02369542.718225.87439571.736215.03469579.465213.47759616.213210.3563
 9665.21209.21659677.459209.62959726.456 209.4059775.453208.17699787.702206.5215
9799.951 206.4979814.153205.79049861.198205.6841  9866.1206.37729873.447206.6461
9885.696205.03719900.731206.24459946.942203.58779952.677202.81239959.191201.7367
9971.513198.71639984.494194.118710001.38192.369210023.44192.575110032.75194.7962
10036.42196.888410048.43205.169610071.96219.325310112.01220.668710151.23220.8204
#Mann= 3 , 0 , 0
9529.231  0.0551       09529.231  0.0551       010151.23  0.0551       0
#XS Ineff= 2 , 0
       09694.581        10070.54       0
Bank Sta=9529.231,10151.23
Exp/Cntr=0.3,0.1

Type RM Length L Ch R = 3 ,143643.1,,,
BEGIN DESCRIPTION:
END DESCRIPTION:
Bridge Culvert--1,0,-1,-1, 0
Deck Dist Width WeirC Skew NumUp NumDn MinLoCord MaxHiCord MaxSubmerge Is_Ogee
14.503800,26.902800,2.6,0, 60, 60, , , 0.95, 0, 0,0,,
 9526.67 9534.42 9559.34 9567.88 9571.80 9584.26 9596.72 9601.41 9618.17 9634.10
 9651.70 9659.02 9668.46 9671.48 9683.94 9685.22 9696.40 9708.86 9718.75 9721.32
 9735.51 9746.24 9752.27 9758.70 9783.62 9796.08 9802.56 9808.54 9819.32 9821.00
 9836.09 9845.92 9852.85 9858.38 9869.61 9883.30 9895.76 9908.22 9933.14 9945.60
 9958.06 9960.79 9977.03 9977.0310022.9710022.9710041.0310045.2810054.0110068.24
10078.2510088.2710098.2810108.2910118.3010128.3110138.3210148.3310158.3510168.70
  226.83  224.30  217.34  215.69  215.25  214.44  212.88  212.56  211.68  211.23
  211.51  212.03  211.60  211.24  211.16  211.06  209.69  209.33  209.68  209.64
  208.77  208.33  208.42  208.33  207.34  207.18  206.82  206.62  206.42  206.34
  205.10  205.20  205.76  205.85  205.09  205.30  205.30  205.62  206.66  207.02
  207.49  206.62  206.93  206.93  207.81  207.81  208.16  208.82  209.10  209.38
  209.47  209.88  211.26  213.82  214.40  218.89  220.10  220.39  220.52  220.35
 -773.17 -775.70 -782.66 -784.31 -784.75 -785.56 -787.12 -787.44 -788.32 -788.77
 -788.49 -787.97 -788.40 -788.76 -788.84 -788.94 -790.31 -790.67 -790.32 -790.36
 -791.23 -791.67 -791.58 -791.67 -792.66 -792.82 -793.18 -793.38 -793.58 -793.66
 -794.90 -794.80 -794.24 -794.15 -794.91 -794.70 -794.70 -794.38 -793.34 -792.98
 -792.51 -793.38 -793.07  204.43  205.31 -792.19 -791.84 -791.18 -790.90 -790.62
 -790.53 -790.12 -788.74 -786.18 -785.60 -781.11 -779.90 -779.61 -779.48 -779.65
 9526.67 9534.42 9559.34 9567.88 9571.80 9584.26 9596.72 9601.41 9618.17 9634.10
 9651.70 9659.02 9668.46 9671.48 9683.94 9685.22 9696.40 9708.86 9718.75 9721.32
 9735.51 9746.24 9752.27 9758.70 9783.62 9796.08 9802.56 9808.54 9819.32 9821.00
 9836.09 9845.92 9852.85 9858.38 9869.61 9883.30 9895.76 9908.22 9933.14 9945.60
 9958.06 9960.79 9977.03 9977.0310022.9710022.9710041.0310045.2810054.0110068.24
10078.2510088.2710098.2810108.2910118.3010128.3110138.3210148.3310158.3510168.70
  226.83  224.30  217.34  215.69  215.25  214.44  212.88  212.56  211.68  211.23
  211.51  212.03  211.60  211.24  211.16  211.06  209.69  209.33  209.68  209.64
  208.77  208.33  208.42  208.33  207.34  207.18  206.82  206.62  206.42  206.34
  205.10  205.20  205.76  205.85  205.09  205.30  205.30  205.62  206.66  207.02
  207.49  206.62  206.93  206.93  207.81  207.81  208.16  208.82  209.10  209.38
  209.47  209.88  211.26  213.82  214.40  218.89  220.10  220.39  220.52  220.35
 -773.17 -775.70 -782.66 -784.31 -784.75 -785.56 -787.12 -787.44 -788.32 -788.77
 -788.49 -787.97 -788.40 -788.76 -788.84 -788.94 -790.31 -790.67 -790.32 -790.36
 -791.23 -791.67 -791.58 -791.67 -792.66 -792.82 -793.18 -793.38 -793.58 -793.66
 -794.90 -794.80 -794.24 -794.15 -794.91 -794.70 -794.70 -794.38 -793.34 -792.98
 -792.51 -793.38 -793.07  204.43  205.31 -792.19 -791.84 -791.18 -790.90 -790.62
 -790.53 -790.12 -788.74 -786.18 -785.60 -781.11 -779.90 -779.61 -779.48 -779.65
Pier Skew, UpSta & Num, DnSta & Num=  ,10000.00, 2 ,10000.00, 2 , 0 , 0 , 0 ,,
    2.00    2.00
 -792.63  207.37
    2.00    2.00
 -792.63  207.37
BR Coef=-1 , 0 , 0 ,, 0 ,,,0.8,0,1,0,
WSPro=,,,, 1 ,,,, 0 ,,,, 0 ,,,,-1 ,-1 ,-1 , 0 , 0 , 0 , 0 , 0
BC Design=,, 0 ,, 0 ,,,,,,

Type RM Length L Ch R = 1 ,  143617,319.298000,319.298000,319.298000
XS GIS Cut Line= 3
464900.485130933836220.552153527464574.964297599836660.656320194
464585.380964266836783.920209083
#Sta/Elev= 30
9516.341227.49769534.311222.56429546.749219.78489559.187217.54699571.626 216.183
9596.502 214.3489626.463213.21139660.096211.01939727.361209.38949783.074207.0106
9845.076205.66949919.894205.01649932.332 206.1799945.974206.61569957.208 204.136
9969.646195.36559979.607192.53599994.523 192.42810006.96193.5925 10019.4194.1121
10031.84 199.45710044.28205.986210056.71208.270110068.11209.224510078.14209.4418
10118.29210.144410148.39 210.13410168.46219.7922 10178.5220.780410187.45220.5122
#Mann= 3 , 0 , 0
9516.341  0.0716       09516.341  0.0716       010187.45  0.0716       0
#XS Ineff= 2 , 0
       09698.371        10070.09       0
Bank Sta=9516.341,10187.45
Exp/Cntr=0.3,0.1

Type RM Length L Ch R = 1 ,143297.7,906.900300,906.900300,906.900300
XS GIS Cut Line= 3
464368.501236737836040.526076287464281.695681155836752.331631824
464309.473458916836926.810798511
#Sta/Elev= 30
9535.194247.07229549.775241.62389559.849240.35129579.997232.68079590.071232.6717
9610.219230.12329640.442229.3396 9660.59226.77449680.738220.9089 9710.96209.5056
9721.034207.48929741.182206.28739872.146204.5389 9932.59201.23819942.664201.1823
9952.738202.17549972.886191.1511 9982.96190.336810003.11190.949510013.18192.6545
 10043.4204.207710073.63206.761910103.85 206.57910144.15207.314810164.29208.6472
10224.74 209.29610295.48215.4036 10305.6215.666710396.74215.573910428.95214.8362
#Mann= 3 , 0 , 0
9535.194  0.0584       09535.194  0.0584       010428.95  0.0584       0
#XS Ineff= 2 , 0
       0 9719.07        10083.08       0
Bank Sta=9535.194,10428.95
Exp/Cntr=0.3,0.1