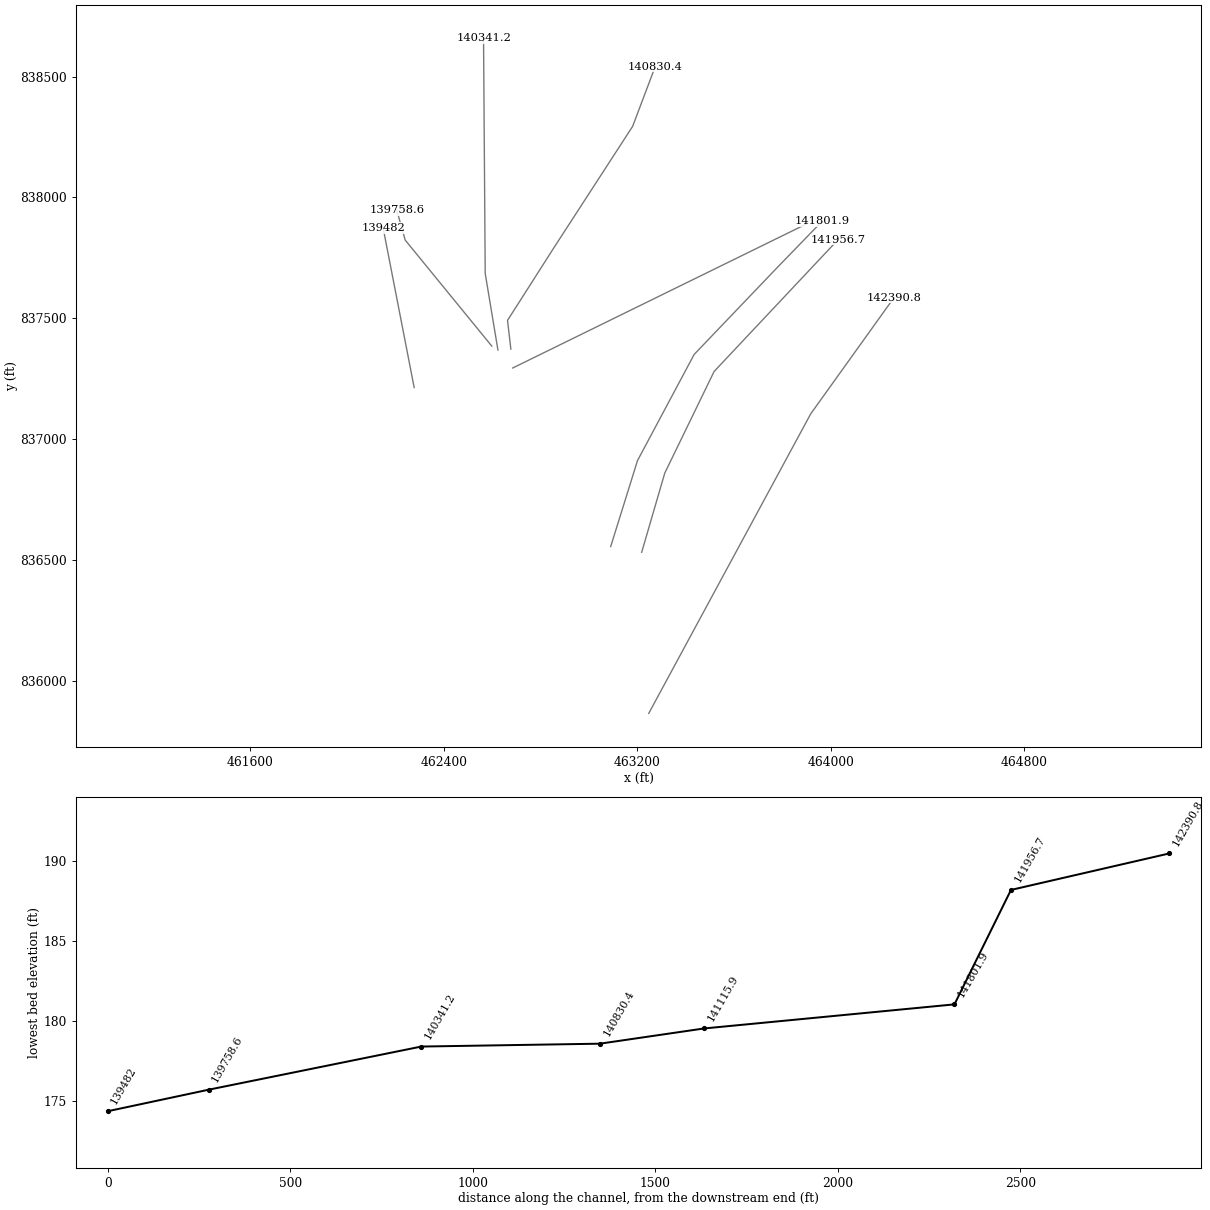
HEC-RAS study 7132_ras.prj: 7132

--- 7132_ras.g01 (geometry) --- (continued)

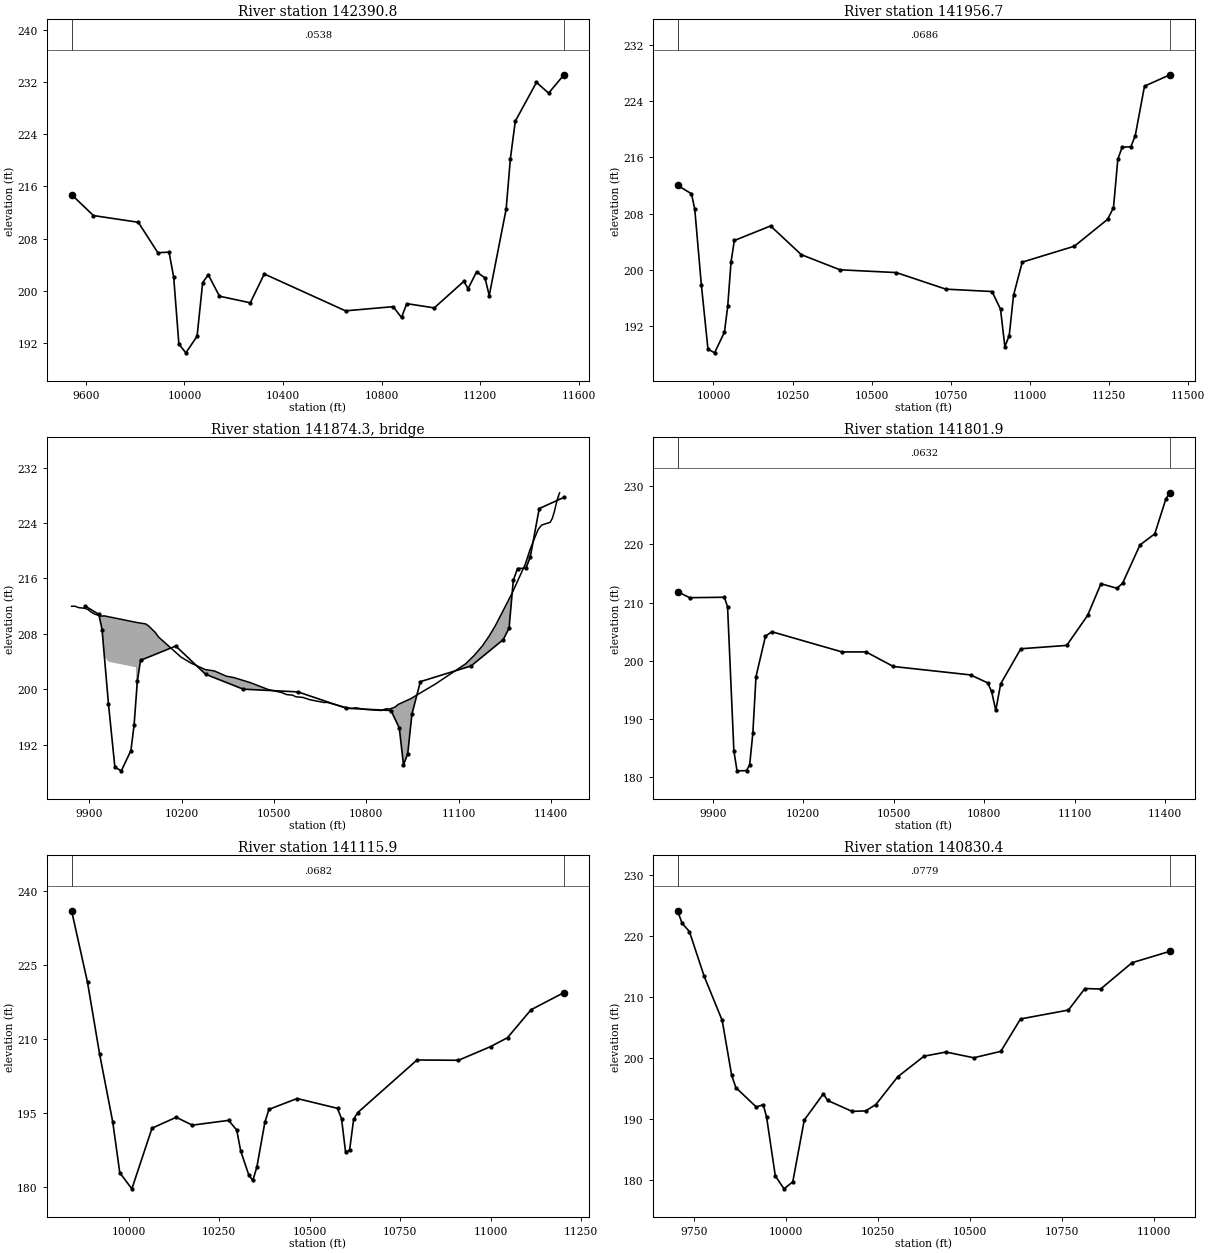
Type RM Length L Ch R = 1 ,142390.8,434.180400,434.180400,434.180400
XS GIS Cut Line= 3
463247.841514528835866.914965183463917.661056906837105.536239177
464261.730403364837585.664965168
#Sta/Elev= 30
9541.735214.72099630.506211.52399812.403210.49389891.983205.83029937.457205.9175
9956.213202.05929977.235 191.82110005.67 190.48710051.14193.033210073.88201.2606
10096.62202.453510142.09199.165710267.15198.155110323.99202.571610653.68196.9234
10846.94197.562110881.05195.905110902.23198.026611013.97197.374511134.14201.4482
11151.31200.314811185.65202.893611219.87201.974111237.15 199.26311305.82212.5081
11322.99220.215211342.89225.979411429.01231.936411478.22230.280511540.55233.0957
#Mann= 3 , 0 , 0
9541.735  0.0538       09541.735  0.0538       011540.55  0.0538       0
#XS Ineff= 2 , 0
       0                11048.76       0
Bank Sta=9541.735,11540.55
Exp/Cntr=0.3,0.1

Type RM Length L Ch R = 1 ,141956.7,154.781300,154.781300,154.781300
XS GIS Cut Line= 4
463218.610130933836532.882882695463314.096242044836860.356841028
463518.089297599837280.495729917464030.078555554837824.941236213
#Sta/Elev= 30
9886.792 211.9999930.663210.8092 9941.08208.60279961.912197.85279982.745188.7356
10003.58188.200110034.83191.128610045.24194.838510055.66201.115310066.08204.1659
10180.66206.234410277.53202.153210399.81200.001710577.67199.607810734.23197.2526
 10880.2196.914810907.04194.404810920.76189.066410934.49190.655910948.22196.4026
10975.67201.0907 11140.4203.355811245.13207.164211263.94208.823611277.67215.7256
11291.39217.432811318.85217.482711332.72219.081511361.91226.100111442.31227.7167
#Mann= 3 , 0 , 0
9886.792  0.0686       09886.792  0.0686       011442.31  0.0686       0
#XS Ineff= 2 , 0
       0                 11036.9       0
Bank Sta=9886.792,11442.31
Exp/Cntr=0.3,0.1

Type RM Length L Ch R = 3 ,141874.3,,,
BEGIN DESCRIPTION:
END DESCRIPTION:
Bridge Culvert--1,0,-1,-1, 0
Deck Dist Width WeirC Skew NumUp NumDn MinLoCord MaxHiCord MaxSubmerge Is_Ogee
56.393300,41.994700,2.6,0, 60, 60, , , 0.95, 0, 0,0,,
 9842.07 9853.50 9863.93 9884.78 9895.21 9905.64 9917.60 9936.92 9948.65 9948.65
10051.3510051.3510082.9010093.3210114.1810124.6010197.5910231.5410276.8110305.89
10344.7110369.9710423.9310480.5110525.7810540.8610559.7310571.0410593.6810616.31
10661.5810672.8910738.5510752.2810766.0110793.4610848.3710864.4310875.8310893.62
10903.2910944.4711024.9911122.9311150.3911177.8511200.1411219.0311273.9411316.91
11331.5111356.3111360.7011370.0411397.4911404.4911411.2211419.0911424.9511428.11
  211.98  211.99  211.79  211.69  211.52  211.14  210.84  210.56  210.59  210.59
  209.66  209.66  209.43  209.10  208.19  207.54  204.64  203.74  202.83  202.64
  201.88  201.67  200.93  199.96  199.50  199.22  199.14  198.90  198.81  198.48
  198.08  198.09  197.29  197.22  197.31  197.09  196.92  197.17  197.13  197.42
  197.79  198.63  200.76  203.67  204.87  206.29  207.75  209.15  213.89  218.10
  220.11  222.86  223.22  223.72  224.11  224.68  225.69  227.17  228.03  228.38
 -788.02 -788.01 -788.21 -788.31 -788.48 -788.86 -789.16 -789.44 -789.41  204.09
  203.16 -790.34 -790.57 -790.90 -791.81 -792.46 -795.36 -796.26 -797.17 -797.36
 -798.12 -798.33 -799.07 -800.04 -800.50 -800.78 -800.86 -801.10 -801.19 -801.52
 -801.92 -801.91 -802.71 -802.78 -802.69 -802.91 -803.08 -802.83 -802.87 -802.58
 -802.21 -801.37 -799.24 -796.33 -795.13 -793.71 -792.25 -790.85 -786.11 -781.90
 -779.89 -777.14 -776.78 -776.28 -775.89 -775.32 -774.31 -772.83 -771.97 -771.62
 9842.07 9853.50 9863.93 9884.78 9895.21 9905.64 9917.60 9936.92 9948.65 9948.65
10051.3510051.3510082.9010093.3210114.1810124.6010197.5910231.5410276.8110305.89
10344.7110369.9710423.9310480.5110525.7810540.8610559.7310571.0410593.6810616.31
10661.5810672.8910738.5510752.2810766.0110793.4610848.3710864.4310875.8310893.62
10903.2910944.4711024.9911122.9311150.3911177.8511200.1411219.0311273.9411316.91
11331.5111356.3111360.7011370.0411397.4911404.4911411.2211419.0911424.9511428.11
  211.98  211.99  211.79  211.69  211.52  211.14  210.84  210.56  210.59  210.59
  209.66  209.66  209.43  209.10  208.19  207.54  204.64  203.74  202.83  202.64
  201.88  201.67  200.93  199.96  199.50  199.22  199.14  198.90  198.81  198.48
  198.08  198.09  197.29  197.22  197.31  197.09  196.92  197.17  197.13  197.42
  197.79  198.63  200.76  203.67  204.87  206.29  207.75  209.15  213.89  218.10
  220.11  222.86  223.22  223.72  224.11  224.68  225.69  227.17  228.03  228.38
 -788.02 -788.01 -788.21 -788.31 -788.48 -788.86 -789.16 -789.44 -789.41  204.09
  203.16 -790.34 -790.57 -790.90 -791.81 -792.46 -795.36 -796.26 -797.17 -797.36
 -798.12 -798.33 -799.07 -800.04 -800.50 -800.78 -800.86 -801.10 -801.19 -801.52
 -801.92 -801.91 -802.71 -802.78 -802.69 -802.91 -803.08 -802.83 -802.87 -802.58
 -802.21 -801.37 -799.24 -796.33 -795.13 -793.71 -792.25 -790.85 -786.11 -781.90
 -779.89 -777.14 -776.78 -776.28 -775.89 -775.32 -774.31 -772.83 -771.97 -771.62
BR Coef=-1 , 0 , 0 ,, 0 ,,,0.8,0,1,0,
WSPro=,,,, 1 ,,,, 0 ,,,, 0 ,,,,-1 ,-1 ,-1 , 0 , 0 , 0 , 0 , 0
BC Design=,, 0 ,, 0 ,,,,,,

Type RM Length L Ch R = 1 ,141801.9,685.931500,685.931500,685.931500
XS GIS Cut Line= 5
463090.571936488836556.754410473463201.249019821836911.789132695
463435.624019822837351.025243806463776.769853155837707.796077139
463964.269853155837901.155452139
#Sta/Elev= 30
9783.448 211.8679823.509 210.831 9938.73210.90529949.205209.24049970.154184.4563
9980.628181.036610012.05181.071310022.53182.0737   10033187.518210043.48197.2501
 10074.9204.209210095.85204.974610328.99201.492410408.33201.500510499.01198.9923
10755.54 197.53910811.45 196.17510824.72   194.710838.56191.446810854.86196.0138
10921.57202.043311073.77202.619611142.95207.767711187.37213.230911240.43212.4553
11259.19  213.3311316.65219.899511365.79221.819411402.84227.851311416.15228.8843
#Mann= 3 , 0 , 0
9783.448  0.0632       09783.448  0.0632       011416.15  0.0632       0
#XS Ineff= 2 , 0
       0                10992.56       0
Bank Sta=9783.448,11416.15
Exp/Cntr=0.3,0.1

Type RM Length L Ch R = 1 ,141115.9,285.528900,285.528900,285.528900
XS GIS Cut Line= 2
462685.537214279837294.948854938463906.637810767837893.654693186
#Sta/Elev= 30
9842.064235.96769886.015221.44659919.427206.87999955.757193.08179975.113182.8038
10008.53 179.52810064.21191.841910131.04194.052610175.58192.456110275.82193.4263
10298.09 191.46410309.23187.207810331.51182.325110342.64181.233110353.78183.9464
10376.06193.086910387.19195.662910465.15197.862510576.53195.865610587.66193.7697
 10598.8187.003310609.94 187.39210621.08193.650910632.21194.997410796.22205.6833
10910.65205.622710999.74208.411311046.09 210.20811111.12215.884811202.04219.3662
#Mann= 3 , 0 , 0
9842.064  0.0682       09842.064  0.0682       011202.04  0.0682       0
#XS Ineff= 2 , 0
       0                               0
Bank Sta=9842.064,11202.04
Exp/Cntr=0.3,0.1

Type RM Length L Ch R = 1 ,140830.4,489.188100,489.188100,489.188100
XS GIS Cut Line= 5
462677.724714279837373.073854938462664.016283005837491.744970948
462856.464199662837793.307470948463181.246033698838293.937579453
463274.709916413838541.354126737
#Sta/Elev= 30
9705.332224.17219717.337222.1549 9737.47220.75869777.736213.41339826.621206.1945
9852.379197.17129863.799195.16879919.565191.98369938.154192.38489947.282190.3345
9971.007180.68099994.733178.574910018.46179.720410049.69189.8561 10101.5194.1494
10113.36193.062610179.81191.275510216.59191.355710244.15192.390110303.75196.9471
10375.27200.326710434.87201.008510510.57200.066210584.07201.123910637.51206.4323
10767.81207.892610812.49211.417410855.25211.340910940.76215.656711043.76 217.524
#Mann= 3 , 0 , 0
9705.332  0.0779       09705.332  0.0779       011043.76  0.0779       0
#XS Ineff= 2 , 0
       0 9849.53                       0
Bank Sta=9705.332,11043.76
Exp/Cntr=0.3,0.1

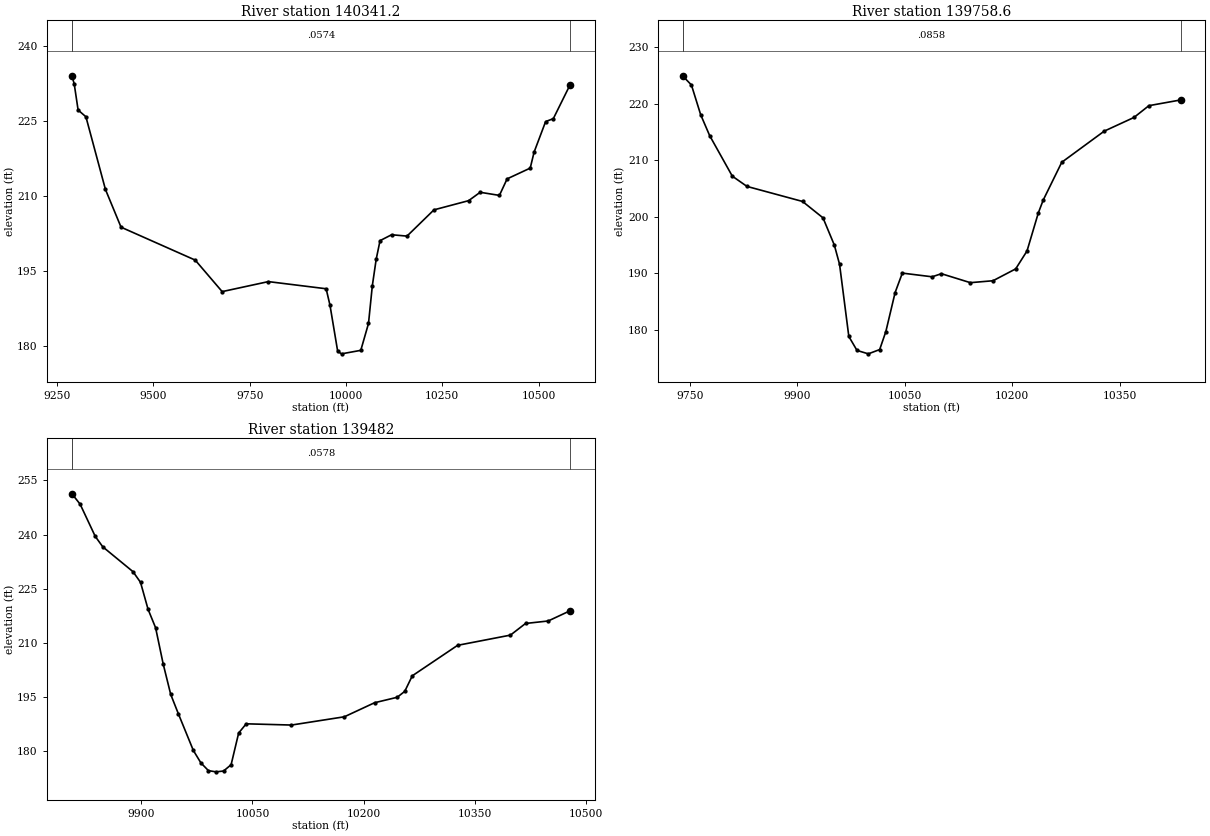
Type RM Length L Ch R = 1 ,140341.2,582.597400,582.597400,582.597400
XS GIS Cut Line= 3
462624.339297593837369.037396595462571.741977453837685.668582067
462564.797533035838657.890804306
#Sta/Elev= 30
9288.118234.08929294.162232.48019304.299 227.2299324.573225.87619375.259211.3245
9415.807203.7627 9608.41197.17139678.421190.85789798.424192.86279948.428191.4306
9958.428 188.1349978.429178.89539988.429 178.39510038.43179.094210058.43184.4722
10068.43192.053610078.43197.348810088.43201.067810118.43 202.24910158.43201.9769
10228.44 207.23410318.44209.074210348.44 210.75510398.44210.129110418.44213.4418
10478.44215.594810488.44218.783510518.44224.917110538.44225.502510581.34232.1856
#Mann= 3 , 0 , 0
9288.118  0.0574       09288.118  0.0574       010581.34  0.0574       0
#XS Ineff= 2 , 0
       09596.832                       0
Bank Sta=9288.118,10581.34
Exp/Cntr=0.3,0.1

Type RM Length L Ch R = 1 ,139758.6,276.649900,276.649900,276.649900
XS GIS Cut Line= 3
462598.912116319837385.408165395462240.839199662837823.776220962
462206.116977453837947.474137634
#Sta/Elev= 30
9740.114224.91129752.499223.27879765.411218.01279777.913214.32069809.528207.1413
9829.971205.32869907.444202.66639935.988199.76469951.796194.94859959.092191.5436
9972.004178.77239983.411176.29689999.218175.693810015.03176.449410023.65179.6391
10036.56 186.53710046.64189.983910088.21189.330710101.12189.877310141.49188.2908
 10173.1188.631710204.72190.729410220.52193.895710236.33 200.64610243.16202.9189
10268.98209.597910328.18215.107810369.73217.5359 10390.5219.619310434.62220.6291
#Mann= 3 , 0 , 0
9740.114  0.0858       09740.114  0.0858       010434.62  0.0858       0
#XS Ineff= 2 , 0
       0 9914.39                       0
Bank Sta=9740.114,10434.62
Exp/Cntr=0.3,0.1

Type RM Length L Ch R = 1 ,  139482,375.775800,375.775800,375.775800
XS GIS Cut Line= 2
462277.985130936837214.089479923462149.693366319837873.689415395
#Sta/Elev= 30
9806.303251.29399817.418  248.429837.792239.5206 9847.98236.61569888.729229.7493
9898.917226.79369909.104  219.339919.291214.21389929.479204.22699939.666195.7788
9949.854 190.4819970.228180.26049980.416176.81869990.603174.675510000.79174.3458
10010.98174.570410021.17176.317110031.35185.084910041.54187.636410102.66187.2939
10173.98  189.5810214.73193.467110245.29194.977410255.48196.615610265.66200.9215
10326.79209.3548 10398.1212.181910418.47215.404110449.04216.091710478.26218.8915
#Mann= 3 , 0 , 0
9806.303  0.0578       09806.303  0.0578       010478.26  0.0578       0
#XS Ineff= 2 , 0
       0                               0
Bank Sta=9806.303,10478.26
Exp/Cntr=0.3,0.1