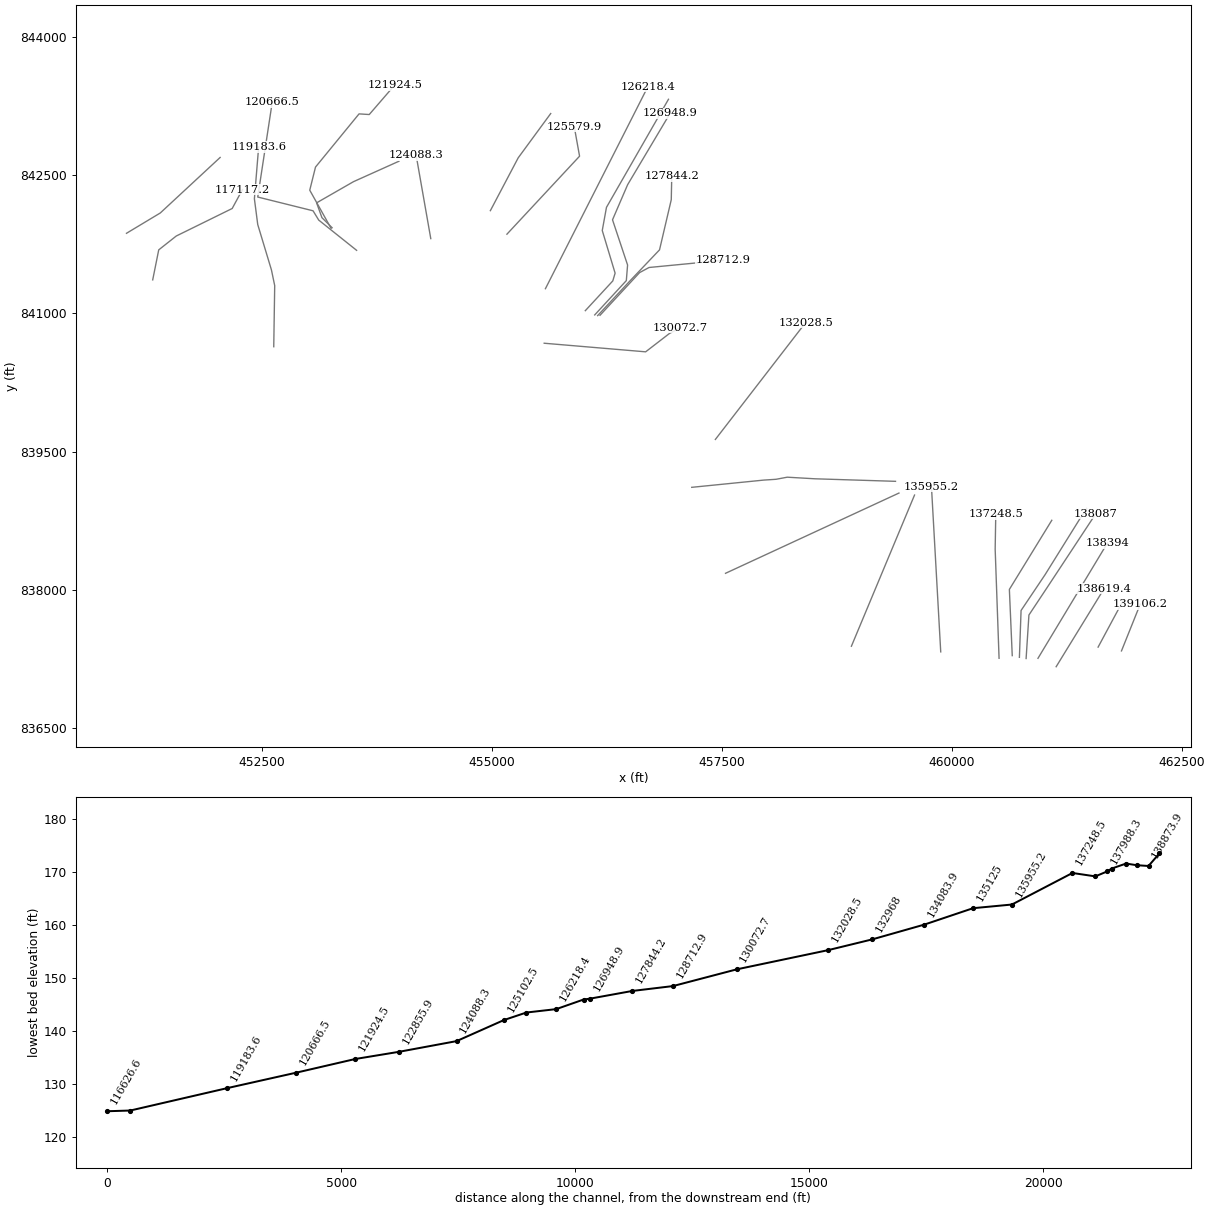
HEC-RAS study 7132_ras.prj: 7132

--- 7132_ras.g01 (geometry) --- (continued)

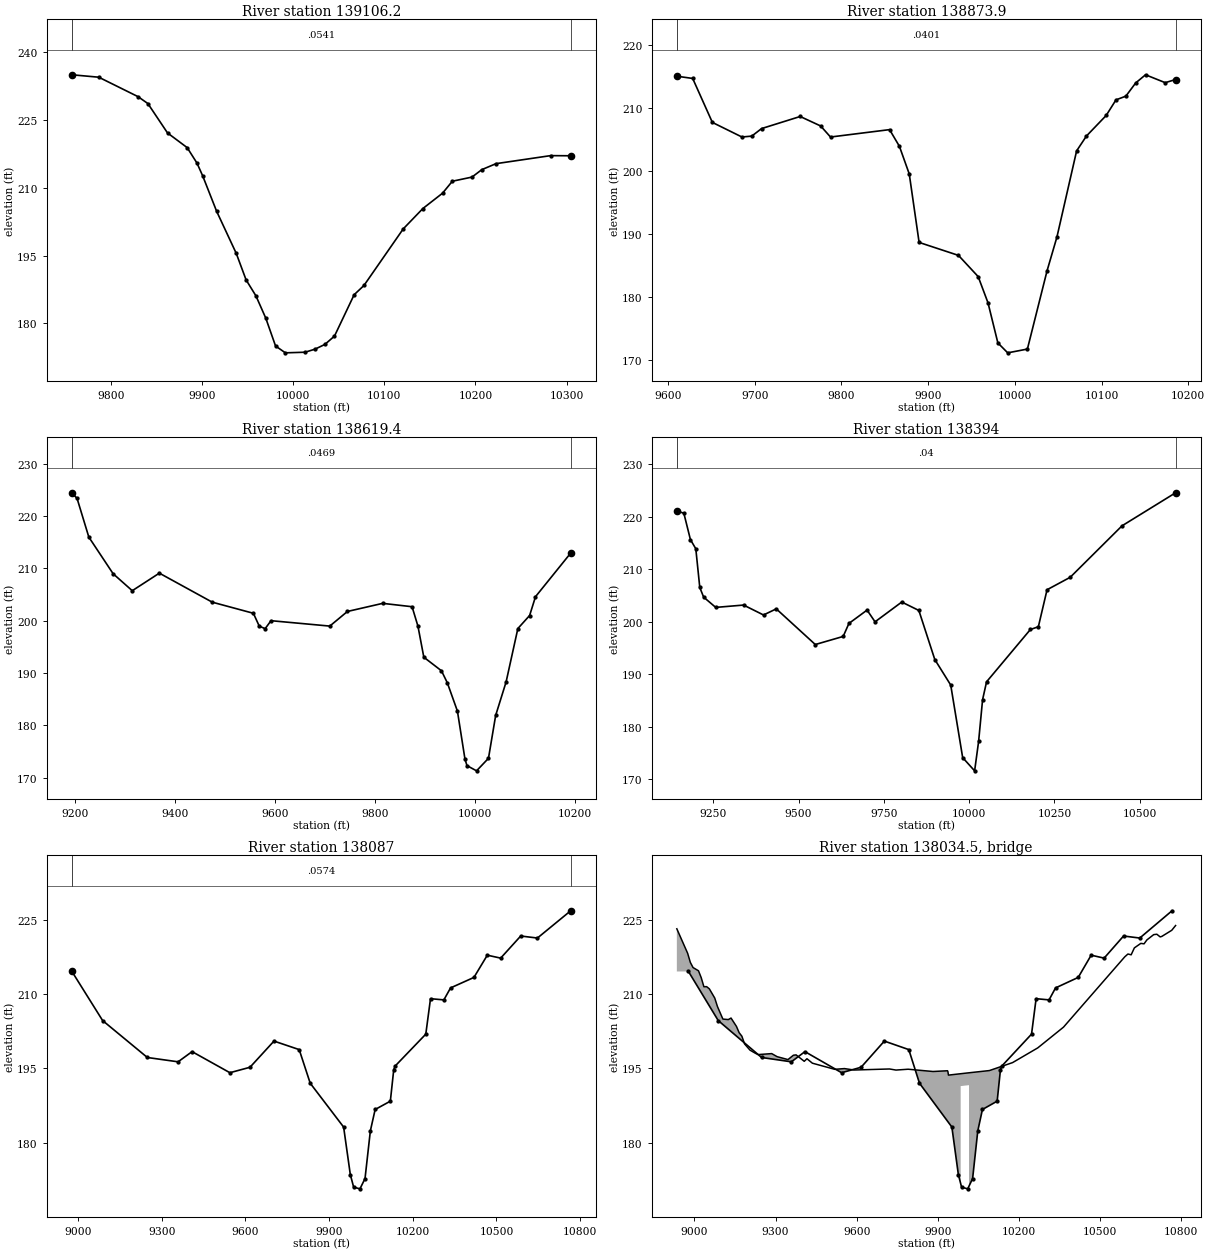
Type RM Length L Ch R = 1 ,139106.2,232.344000,232.344000,232.344000
XS GIS Cut Line= 2
 461841.53364411837337.665109843462045.526699692837845.477609858
#Sta/Elev= 30
9757.193234.94529786.651234.40849829.758230.11169840.535228.58839862.088222.0969
9883.642218.85539894.418215.43489900.628212.63959915.972204.79269937.525195.4797
9948.302189.63499959.078 186.1139969.855181.20569980.632175.03349991.408173.5181
10012.96173.654110023.74174.315110034.76175.376310045.29177.217210066.85186.3537
10077.62188.396610120.73200.900710142.28205.398410163.84 208.78410174.61 211.428
10196.17212.345110206.94 213.98910222.55 215.31110282.38217.083110304.45217.0539
#Mann= 3 , 0 , 0
9757.193  0.0541       09757.193  0.0541       010304.45  0.0541       0
#XS Ineff= 2 , 0
       0                               0
Bank Sta=9757.193,10304.45
Exp/Cntr=0.3,0.1

Type RM Length L Ch R = 1 ,138873.9,254.466700,254.466700,254.466700
XS GIS Cut Line= 2
 461587.62739414837378.897748739461860.016380936837885.530452132
#Sta/Elev= 30
9610.214215.06199628.496214.70739651.203207.72569685.264205.41149696.618205.5505
9707.972206.74889752.488208.66619776.094207.16129787.448 205.406 9855.57206.5809
9866.924203.92989878.277199.54079889.631188.67279935.046186.61349957.753 183.245
9969.107179.0771 9980.46172.71949991.814171.143410014.52171.742110037.23184.1845
10048.58189.527610071.29203.207510082.64205.568810105.35208.8246 10116.7211.3062
10128.06211.894410139.41213.991410150.77215.288610173.47214.034710185.43214.5364
#Mann= 3 , 0 , 0
9610.214  0.0401       09610.214  0.0401       010185.43  0.0401       0
#XS Ineff= 2 , 0
       09829.586                       0
Bank Sta=9610.214,10185.43
Exp/Cntr=0.3,0.1

Type RM Length L Ch R = 1 ,138619.4,225.427000,225.427000,225.427000
XS GIS Cut Line= 2
461131.898227483837166.224137619461653.419158697838014.870729938
#Sta/Elev= 30
9194.715224.46259205.016 223.379 9228.49215.98639277.038208.98019315.237205.7369
9369.338 209.0959474.974203.54549557.136201.42049568.873198.9609 9580.61198.4807
9592.348200.00469709.721 198.9729744.933201.76839815.357203.31919874.044202.6751
9885.781198.95729897.518193.0206 9932.73190.42619944.468188.12339964.624182.7142
 9979.68173.54219983.724172.290910002.82171.295210026.63173.693710041.02181.9025
10061.84188.295910085.32198.506610108.79200.995210120.53204.5911 10190.8 212.929
#Mann= 3 , 0 , 0
9194.715  0.0469       09194.715  0.0469       0 10190.8  0.0469       0
#XS Ineff= 2 , 0
       09843.931                       0
Bank Sta=9194.715,10190.8
Exp/Cntr=0.3,0.1

Type RM Length L Ch R = 1 ,  138394,306.956800,306.956800,306.956800
XS GIS Cut Line= 2
460934.415588558837257.369970948461689.623921871838509.540109843
#Sta/Elev= 30
9143.169221.11929163.758220.67199183.026215.64519198.792 213.906 9210.47206.5287
9221.751204.69389257.182202.73399338.927203.17949397.317201.2903 9434.74202.4559
9549.131195.66189630.877197.20259647.729199.68039700.945202.22299724.301199.9847
9802.631203.75529852.759 202.1529899.471192.80869946.183187.94289981.217174.1189
10016.25171.601810027.93177.196210039.61185.167110051.28188.560410179.74198.5258
 10203.1199.048810228.61206.098210296.52208.470710448.34218.270610605.45224.5676
#Mann= 3 , 0 , 0
9143.169    0.04       09143.169    0.04       010605.45    0.04       0
#XS Ineff= 2 , 0
       09826.881        10155.44       0
Bank Sta=9143.169,10605.45
Exp/Cntr=0.3,0.1

Type RM Length L Ch R = 1 ,  138087,98.671000,98.671000,98.671000
XS GIS Cut Line= 4
460805.511689037837255.084818631460836.067244589837727.307040855
461033.289466828838024.529263064461561.067244589838824.529263079
#Sta/Elev= 30
8977.815214.6199 9087.96204.68999248.294 197.2229358.524196.34799408.629198.4083
9544.266194.14399616.273195.24389702.304200.53949792.736198.81739832.253192.0166
9952.054183.14899976.014173.54459987.994170.993910010.59170.658510028.75172.7341
10047.89182.383810065.07186.706210119.54188.388510131.76194.7856 10137.7195.5492
10246.66201.944710263.54209.113510311.46208.873810335.42 211.29210419.28213.4172
 10467.2217.913310515.12217.3192   10587221.7897 10646.9221.380510766.14226.8939
#Mann= 3 , 0 , 0
8977.815  0.0574       08977.815  0.0574       010766.14  0.0574       0
#XS Ineff= 2 , 0
       09941.534        10084.24       0
Bank Sta=8977.815,10766.14
Exp/Cntr=0.3,0.1

Type RM Length L Ch R = 3 ,138034.5,,,
BEGIN DESCRIPTION:
END DESCRIPTION:
Bridge Culvert--1,0,-1,-1, 0
Deck Dist Width WeirC Skew NumUp NumDn MinLoCord MaxHiCord MaxSubmerge Is_Ogee
33.423450,31.824100,2.6,0, 60, 60, , , 0.95, 0, 0,0,,
 8934.85 8974.83 8984.85 8994.88 9014.94 9024.97 9035.00 9045.03 9055.06 9075.11
 9085.14 9105.20 9125.26 9135.29 9155.34 9165.37 9175.40 9185.42 9205.49 9225.55
 9235.57 9285.72 9305.78 9345.89 9365.95 9375.98 9406.06 9416.09 9436.15 9518.94
 9554.68 9590.42 9721.48 9745.31 9790.34 9882.31 9935.94 9937.49 9939.33 9984.58
 9984.5810015.4210015.4210090.8310176.6210269.5510364.8710591.2410603.1610615.07
10626.9810650.8110662.7310673.2610698.4710710.0510722.3010728.4410765.2310779.40
  223.25  218.30  216.45  215.41  214.76  213.38  211.53  211.55  211.11  209.24
  207.52  204.99  204.89  205.20  203.51  202.23  201.53  199.96  198.71  198.07
  197.81  198.01  197.39  196.80  197.68  197.75  196.45  196.97  196.07  194.83
  194.98  194.69  194.90  194.68  194.85  194.39  194.54  194.34  193.66  193.94
  193.94  194.13  194.13  194.58  196.19  199.16  203.36  217.57  218.15  217.99
  219.39  220.30  220.21  221.00  222.07  222.15  221.61  221.71  222.95  223.91
 -776.75 -781.70 -783.55 -784.59 -785.24 -786.62 -788.47 -788.45 -788.89 -790.76
 -792.48 -795.01 -795.11 -794.80 -796.49 -797.77 -798.47 -800.04 -801.29 -801.93
 -802.19 -801.99 -802.61 -803.20 -802.32 -802.25 -803.55 -803.03 -803.93 -805.17
 -805.02 -805.31 -805.10 -805.32 -805.15 -805.61 -805.46 -805.66 -806.34 -806.06
  191.44  191.63 -805.87 -805.42 -803.81 -800.84 -796.64 -782.43 -781.85 -782.01
 -780.61 -779.70 -779.79 -779.00 -777.93 -777.85 -778.39 -778.29 -777.05 -776.09
 8934.85 8974.83 8984.85 8994.88 9014.94 9024.97 9035.00 9045.03 9055.06 9075.11
 9085.14 9105.20 9125.26 9135.29 9155.34 9165.37 9175.40 9185.42 9205.49 9225.55
 9235.57 9285.72 9305.78 9345.89 9365.95 9375.98 9406.06 9416.09 9436.15 9518.94
 9554.68 9590.42 9721.48 9745.31 9790.34 9882.31 9935.94 9937.49 9939.33 9984.58
 9984.5810015.4210015.4210090.8310176.6210269.5510364.8710591.2410603.1610615.07
10626.9810650.8110662.7310673.2610698.4710710.0510722.3010728.4410765.2310779.40
  223.25  218.30  216.45  215.41  214.76  213.38  211.53  211.55  211.11  209.24
  207.52  204.99  204.89  205.20  203.51  202.23  201.53  199.96  198.71  198.07
  197.81  198.01  197.39  196.80  197.68  197.75  196.45  196.97  196.07  194.83
  194.98  194.69  194.90  194.68  194.85  194.39  194.54  194.34  193.66  193.94
  193.94  194.13  194.13  194.58  196.19  199.16  203.36  217.57  218.15  217.99
  219.39  220.30  220.21  221.00  222.07  222.15  221.61  221.71  222.95  223.91
 -776.75 -781.70 -783.55 -784.59 -785.24 -786.62 -788.47 -788.45 -788.89 -790.76
 -792.48 -795.01 -795.11 -794.80 -796.49 -797.77 -798.47 -800.04 -801.29 -801.93
 -802.19 -801.99 -802.61 -803.20 -802.32 -802.25 -803.55 -803.03 -803.93 -805.17
 -805.02 -805.31 -805.10 -805.32 -805.15 -805.61 -805.46 -805.66 -806.34 -806.06
  191.44  191.63 -805.87 -805.42 -803.81 -800.84 -796.64 -782.43 -781.85 -782.01
 -780.61 -779.70 -779.79 -779.00 -777.93 -777.85 -778.39 -778.29 -777.05 -776.09
BR Coef=-1 , 0 , 0 ,, 0 ,,,0.8,0,1,0,
WSPro=,,,, 1 ,,,, 0 ,,,, 0 ,,,,-1 ,-1 ,-1 , 0 , 0 , 0 , 0 , 0
BC Design=,, 0 ,, 0 ,,,,,,

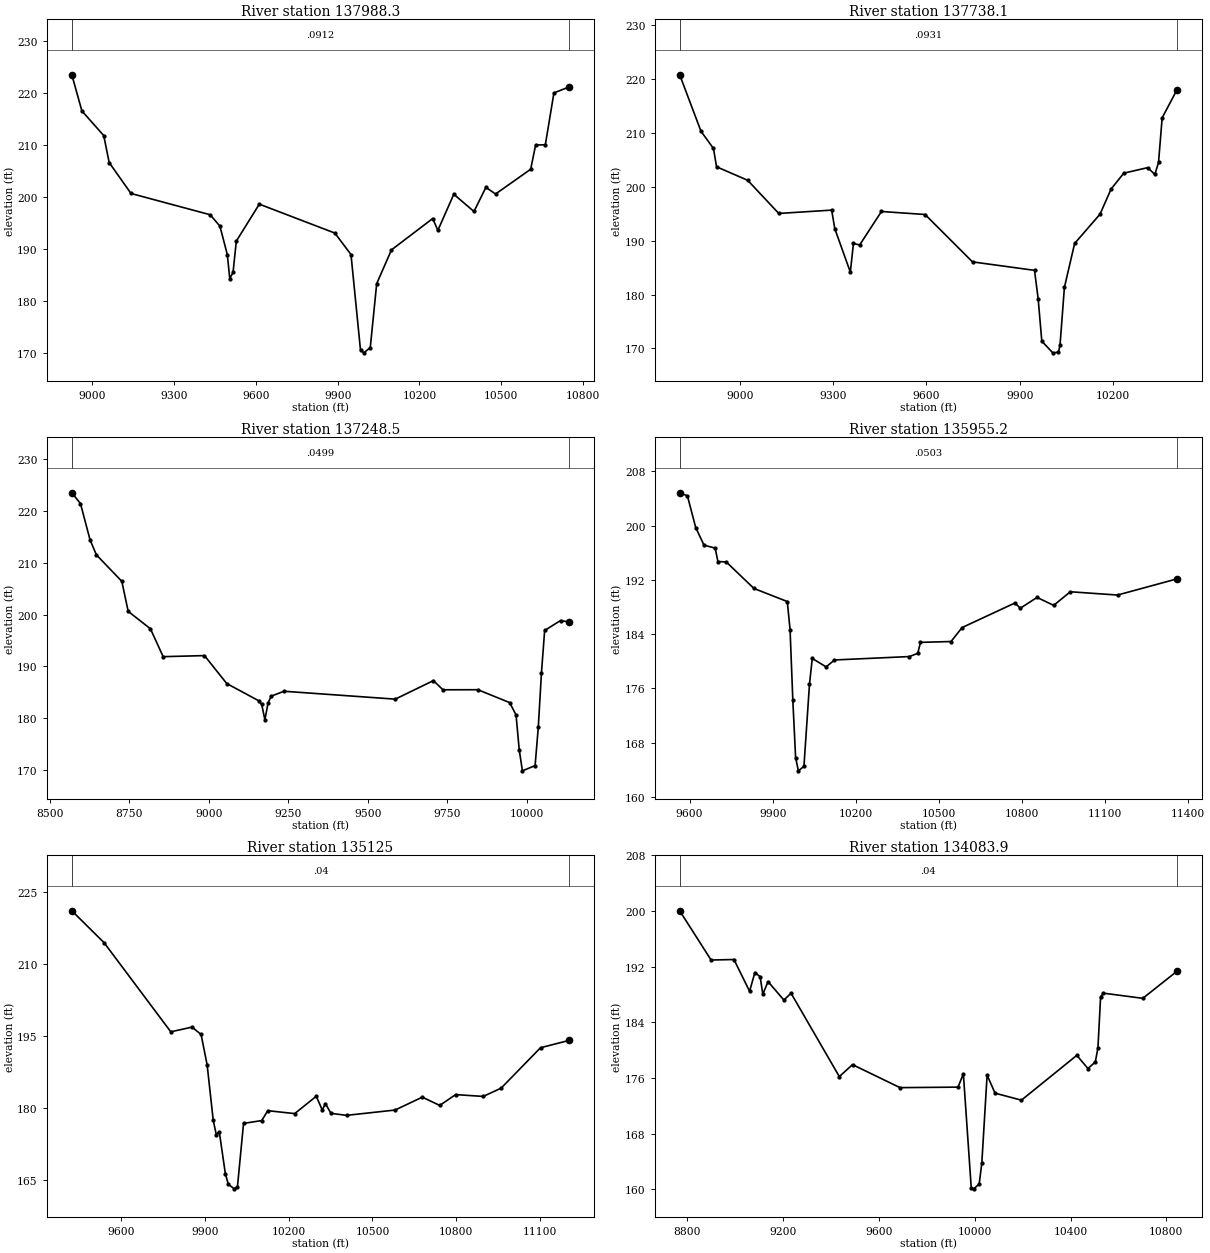
Type RM Length L Ch R = 1 ,137988.3,250.275700,250.275700,250.275700
XS GIS Cut Line= 5
460732.648000002837268.124106571460750.703555554837776.457439899
461011.814666629838165.346328765461387.509111106838768.355588034
461463.666518509838880.901884347
#Sta/Elev= 30
8924.994223.49588961.893216.54869041.944211.82949061.956206.63899142.007200.7045
 9432.19196.62429468.027194.44079495.174188.98819504.162184.36829516.207185.5437
9528.252 191.5679612.567198.65599889.602193.10319948.784188.98259983.731170.6017
9995.912170.109510019.48171.119610043.04 183.388 10097.2189.874810248.48195.8988
10267.39193.623710325.81200.559410399.77197.246310443.63201.881210478.98200.6033
10607.79205.3604 10625.9210.002510661.59 210.064   10693220.014610748.43221.1512
#Mann= 3 , 0 , 0
8924.994  0.0912       08924.994  0.0912       010748.43  0.0912       0
#XS Ineff= 2 , 0
       09929.815        10065.16       0
Bank Sta=8924.994,10748.43
Exp/Cntr=0.3,0.1

Type RM Length L Ch R = 1 ,137738.1,489.543400,489.543400,489.543400
XS GIS Cut Line= 3
460654.901699692837286.449832067460623.651699662838005.199832067
 461084.40874204838755.322118804
#Sta/Elev= 30
8806.206220.76738874.821210.27838914.859207.09898924.868203.69579024.963 201.194
9125.057195.03999295.218195.65859305.227192.22669355.274184.15469365.284 189.471
9385.303189.19299455.369195.40579595.815194.84569748.381186.0562 9947.89184.4873
9959.626179.20989971.362171.355810006.57169.182210024.97169.290710030.04170.6682
10044.08181.326210076.98189.471810158.71194.906210194.34199.574910235.14202.5124
 10311.7203.537410335.17202.286410346.91204.501810358.64212.789310405.96217.9459
#Mann= 3 , 0 , 0
8806.206  0.0931       08806.206  0.0931       010405.96  0.0931       0
#XS Ineff= 2 , 0
       09772.751        10117.92       0
Bank Sta=8806.206,10405.96
Exp/Cntr=0.3,0.1

Type RM Length L Ch R = 1 ,137248.5,1293.266000,1293.266000,1293.266000
XS GIS Cut Line= 3
460511.672533035837257.803998724460469.391380966838441.954063267
460475.901797593838821.728368819
#Sta/Elev= 30
 8568.75  223.568595.963221.46868625.982214.47828645.995211.56298726.046206.4477
8746.059200.64548816.103197.27388856.129 191.8888986.212192.09169056.256186.6939
 9156.32183.38299166.326182.64419176.333179.69039186.339182.96439196.346  184.26
9236.371185.20249586.594183.67899706.671187.2606 9736.69185.48499846.714185.4993
9946.729183.00579966.732180.62339976.733173.89549986.735169.822210026.74170.8395
10036.74178.266110046.74188.784610056.74196.944910106.75 198.87110133.48198.5876
#Mann= 3 , 0 , 0
 8568.75  0.0499       0 8568.75  0.0499       010133.48  0.0499       0
#XS Ineff= 2 , 0
       09478.531                       0
Bank Sta=8568.75,10133.48
Exp/Cntr=0.3,0.1

Type RM Length L Ch R = 1 ,135955.2,830.238800,830.238800,830.238800
XS GIS Cut Line= 2
459877.991977453837327.248443186459777.297533005839118.915109858
#Sta/Elev= 30
9564.541204.84019592.336204.39749622.383199.71879652.431 197.1189692.494196.6897
 9702.51194.70959732.557194.64729832.715190.73589952.904188.8152 9962.92184.6828
9972.936174.23499982.952165.80769992.967163.8658   10013164.530610033.03176.6287
10043.05180.429710093.13179.182310123.17180.2025 10393.6180.706310423.65181.1757
10433.66 182.79910543.84182.9219 10583.9184.9803 10774.2188.594710794.23187.8344
10854.32189.418810914.42188.252310974.51190.253211144.78189.770511359.03192.1494
#Mann= 3 , 0 , 0
9564.541  0.0503       09564.541  0.0503       011359.03  0.0503       0
#XS Ineff= 2 , 0
       09892.775        10598.63       0
Bank Sta=9564.541,11359.03
Exp/Cntr=0.3,0.1

Type RM Length L Ch R = 1 ,  135125,1041.116900,1041.116900,1041.116900
XS GIS Cut Line= 2
458907.575310767837388.457933933459593.339199692839029.082933918
#Sta/Elev= 30
9424.836221.11469540.311214.45299778.756195.89449854.625196.8717 9887.14195.3346
9908.817188.96799930.494177.47029941.332174.47869952.171 175.0599973.848166.3321
9984.686164.094510006.36163.1734 10017.2163.627910038.88176.808110103.91177.4002
10125.59179.460210221.99178.8509   10299182.463910320.68179.571510331.52 180.944
10351.63178.906610407.38178.4864 10580.8179.593810678.35182.278510740.58180.5558
10797.57182.811110896.16182.428810960.14184.156111101.04192.575311203.02194.1007
#Mann= 3 , 0 , 0
9424.836    0.04       09424.836    0.04       011203.02    0.04       0
#XS Ineff= 2 , 0
       0                10633.62       0
Bank Sta=9424.836,11203.02
Exp/Cntr=0.3,0.1

Type RM Length L Ch R = 1 ,134083.9,1115.904000,1115.904000,1115.904000
XS GIS Cut Line= 2
457540.098458946838179.979924664459424.068366319839050.784322798
#Sta/Elev= 30
  8768.5 200.0288899.635192.95188994.972193.0271 9060.33188.46269082.363191.1562
9104.396190.56329115.413188.04599137.446189.85159203.545187.19599233.313 188.184
9434.893176.20559489.976177.92199688.274174.61679930.638174.69029952.671176.6198
9985.721160.15099996.005160.076610018.77160.765110029.79163.811210051.82176.4188
10084.87173.822810195.04 172.81610426.38179.259910472.69177.3612 10503.5178.3036
10514.52180.349410525.53187.640310536.55188.1938 10701.8187.448510843.99191.3266
#Mann= 3 , 0 , 0
  8768.5    0.04       0  8768.5    0.04       010843.99    0.04       0
#XS Ineff= 2 , 0
       0 9508.87        10444.67       0
Bank Sta=8768.5,10843.99
Exp/Cntr=0.3,0.1

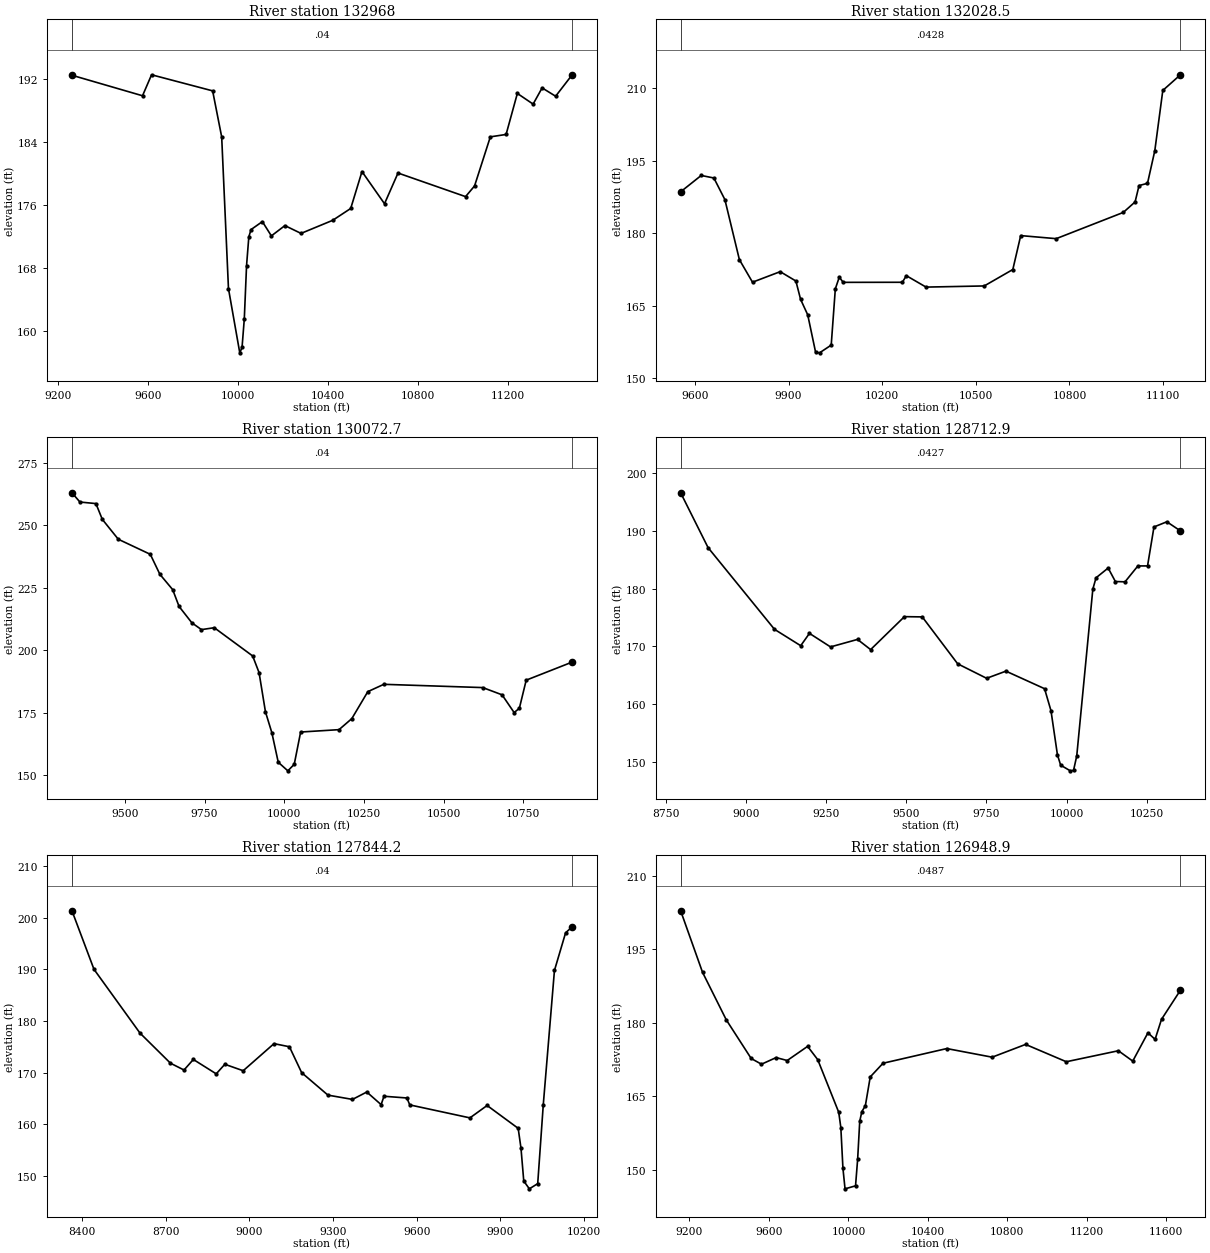
Type RM Length L Ch R = 1 ,  132968,939.477300,939.477300,939.477300
XS GIS Cut Line= 6
457173.055634856839112.994970962 457955.50249204839191.520035475
458088.966033697839200.200591043458210.493811488839222.987049356
 458512.14311704839205.625938267459386.597301543839178.099137634
#Sta/Elev= 30
9262.908192.48359576.419189.8832 9616.62192.54449887.976190.50429928.177184.6652
9958.328165.424110008.58157.278810018.63157.957310028.68161.583610038.73168.3551
10048.78171.9954 10058.8172.916210108.91173.921710148.99172.111710209.07173.4166
10280.74172.426810421.37174.0848 10501.5175.589510551.59 180.269 10651.7176.1891
10711.73180.084211011.88177.0915 11051.9 178.44811121.94184.671611191.97184.9765
11241.99190.178411312.03188.823911352.05190.881911412.08 189.82311483.71192.4717
#Mann= 3 , 0 , 0
9262.908    0.04       09262.908    0.04       011483.71    0.04       0
#XS Ineff= 2 , 0
       09859.215        10749.32       0
Bank Sta=9262.908,11483.71
Exp/Cntr=0.3,0.1

Type RM Length L Ch R = 1 ,132028.5,1955.764300,1955.764300,1955.764300
XS GIS Cut Line= 2
457429.851450413839632.830799356  458409.5494138840899.948095962
#Sta/Elev= 30
9553.984188.58989619.928191.97699660.494191.44879695.771186.97359742.238174.5445
9784.253169.87699873.028172.05939923.297170.12329938.423166.31859961.219163.1239
9986.499155.3687 9999.14155.254110036.52156.8542 10049.7168.504110062.34170.9192
10074.98169.846710264.59169.861710277.23171.231110340.43168.863910526.98169.1026
10618.52172.5024 10643.8 179.52510757.56178.890810972.45184.319611010.37186.4943
11023.01189.884311050.14190.347711073.57197.105211099.19 209.57411155.67212.8184
#Mann= 3 , 0 , 0
9553.984  0.0428       09553.984  0.0428       011155.67  0.0428       0
#XS Ineff= 2 , 0
       0                               0
Bank Sta=9553.984,11155.67
Exp/Cntr=0.3,0.1

Type RM Length L Ch R = 1 ,130072.7,1359.869000,1359.869000,1359.869000
XS GIS Cut Line= 4
455570.143833131840676.755230725456672.318525374840583.466037542
456931.157486796840782.844508007457050.949153364840845.344508007
#Sta/Elev= 30
9334.106263.08249359.051259.3726 9409.23 258.7519429.302252.4249 9479.48244.4528
9579.838238.41899609.945230.39799650.088224.2593 9670.16217.50569710.303210.9522
 9740.41208.22879780.553208.99369900.982197.67149921.054 191.0119941.125 175.279
9961.197 166.9089981.268155.063610011.38151.621910031.45154.243410051.52167.1796
10171.95168.130810212.09172.557110262.27183.363110312.45186.303210622.99184.9943
10683.44182.095610721.32174.981210737.71176.701210759.17187.971710902.06195.1504
#Mann= 3 , 0 , 0
9334.106    0.04       09334.106    0.04       010902.06    0.04       0
#XS Ineff= 2 , 0
       0                10399.02       0
Bank Sta=9334.106,10902.06
Exp/Cntr=0.3,0.1

Type RM Length L Ch R = 1 ,128712.9,868.679700,868.679700,868.679700
XS GIS Cut Line= 4
456176.775640219840980.246887341 456606.46314019841443.354526222
456709.629708916841498.787795022457517.181792259841576.652378365
#Sta/Elev= 30
8795.293196.58088880.897 187.0919088.246172.95359170.095170.11969197.377172.2539
9263.159 169.9119347.433171.20839388.357169.44559493.895175.14779549.548175.1046
9660.058166.98899750.475164.48129810.754165.7185 9931.31162.68259951.403158.8653
9971.496 151.2439981.542149.452410011.68148.468610021.73148.529810031.77151.0448
10082.01179.912310092.05181.873210129.85183.560610152.33181.227610182.47181.1708
10222.66183.924210252.79183.924310272.89190.668510313.07191.562310355.45189.9865
#Mann= 3 , 0 , 0
8795.293  0.0427       08795.293  0.0427       010355.45  0.0427       0
#XS Ineff= 2 , 0
       09535.584        10085.57       0
Bank Sta=8795.293,10355.45
Exp/Cntr=0.3,0.1

Type RM Length L Ch R = 1 ,127844.2,895.328600,895.328600,895.328600
XS GIS Cut Line= 5
456151.205617044840976.580799361 456505.37228371841356.789132695
456823.080617044841690.122466028 456950.68478371842234.393299361
456955.893117044842486.997466028
#Sta/Elev= 30
8364.262201.31878443.185189.99888608.097177.66778717.428 171.8418765.953170.5239
8799.426172.56468881.425169.78378912.318171.63448978.101170.38549088.618175.6257
9143.877175.02199187.705170.01539282.023165.6677 9369.91164.83999421.266166.2699
9472.622163.82759482.893165.45099565.062 165.1169575.333163.77949791.028161.2689
9852.655163.66539964.007159.24719974.009155.43269984.011149.060710004.02147.5461
10034.02148.550410054.03163.845110094.03189.775610134.04197.064810156.05198.1389
#Mann= 3 , 0 , 0
8364.262    0.04       08364.262    0.04       010156.05    0.04       0
#XS Ineff= 2 , 0
       09133.408        10103.15       0
Bank Sta=8364.262,10156.05
Exp/Cntr=0.3,0.1

Type RM Length L Ch R = 1 ,126948.9,147.578100,147.578100,147.578100
XS GIS Cut Line= 6
456119.109262884840984.002674356456462.425235152841356.235747293
456476.053707331841525.669341028456312.425235093 842016.30519174
456476.730403364842397.427841321456937.667903364843171.299369112
#Sta/Elev= 30
9155.511202.82729265.699190.27379385.446180.56349510.569172.69929562.443171.5304
9636.191172.88229691.898172.28429794.687175.17129845.583172.45889951.312161.7248
9961.884158.61229972.457150.3027 9983.03146.107610035.89146.720510046.47152.1222
10057.04159.900510067.61161.852810085.36163.0719 10109.9168.937710174.23171.7262
10495.14174.722310723.61172.962310891.96175.568711096.94172.0328   11359174.2771
11431.37172.162611507.84177.932911543.84 176.59911576.11180.679411671.39186.6243
#Mann= 3 , 0 , 0
9155.511  0.0487       09155.511  0.0487       011671.39  0.0487       0
#XS Ineff= 2 , 0
       0 9865.39        10131.25       0
Bank Sta=9155.511,11671.39
Exp/Cntr=0.3,0.1

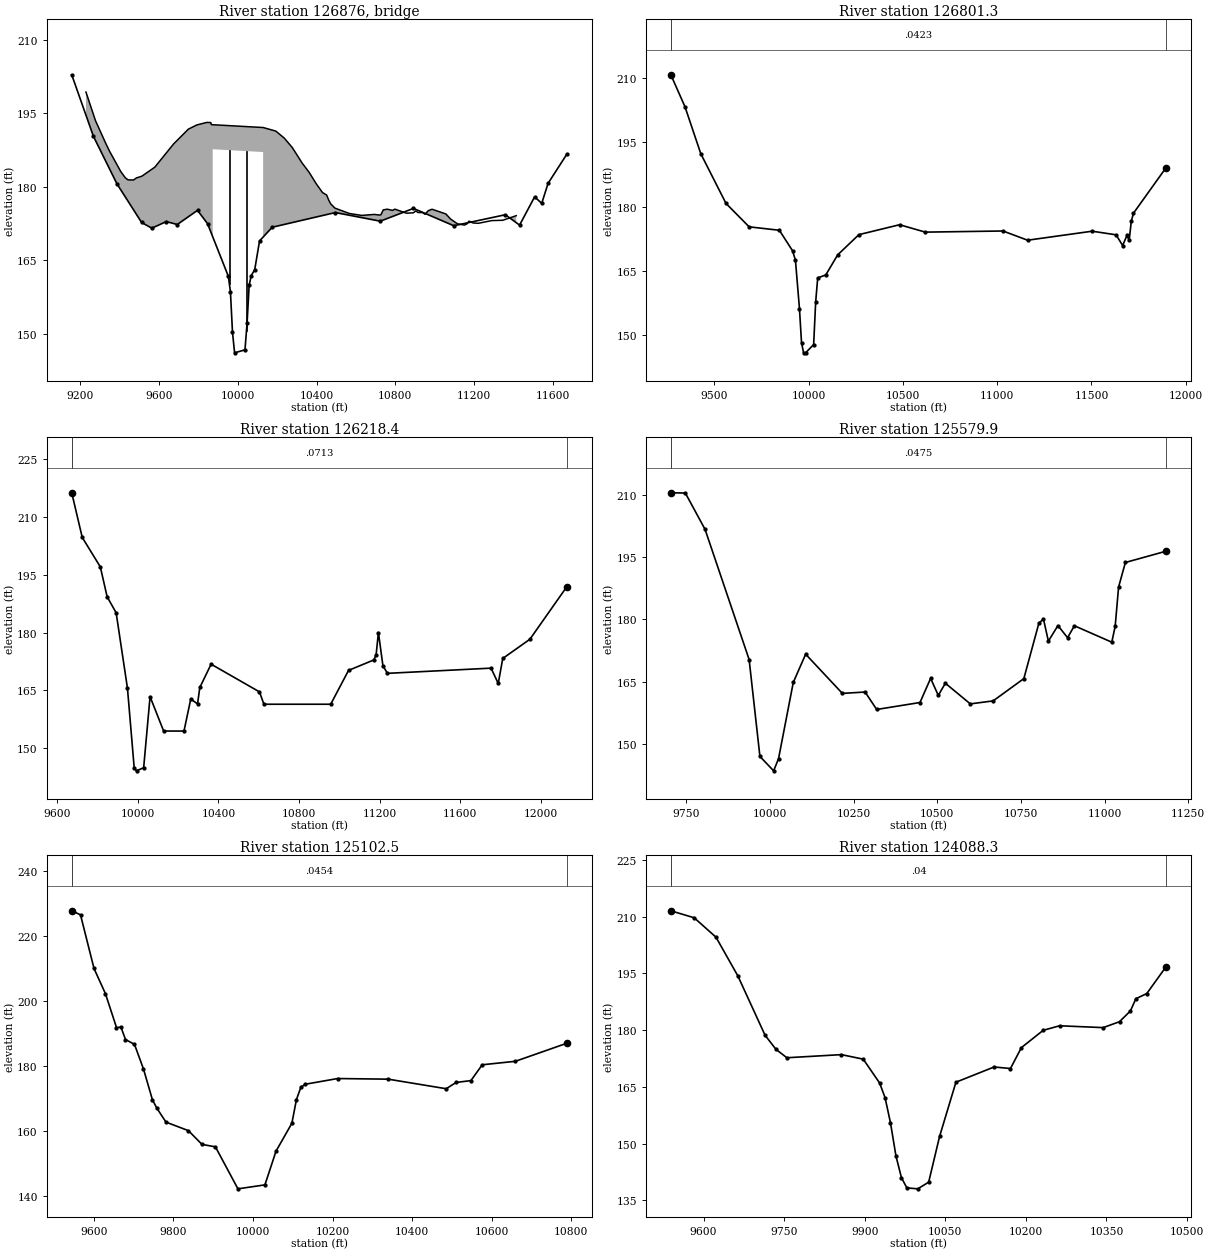
Type RM Length L Ch R = 3 ,  126876,,,
BEGIN DESCRIPTION:
END DESCRIPTION:
Bridge Culvert--1,0,-1,-1, 0
Deck Dist Width WeirC Skew NumUp NumDn MinLoCord MaxHiCord MaxSubmerge Is_Ogee
58.697200,30.183700,2.6,0, 60, 60, , , 0.95, 0, 0,0,,
 9227.87 9276.21 9329.38 9347.49 9404.51 9427.60 9441.64 9469.70 9483.73 9511.79
 9577.64 9673.16 9748.58 9791.64 9841.97 9862.38 9864.77 9871.88 9871.8810128.12
10128.1210192.5810235.1910276.0110326.4110361.5710398.3510429.9210450.9410461.44
10471.9510492.9610566.4510629.4210692.3910721.5010726.8410738.6210759.3510785.73
10797.5110856.4010891.8410903.5110915.2910938.8510950.6310967.5410986.4711056.63
11081.1011115.5211150.8611162.6311174.4111194.6611221.5311289.2911346.0711414.31
  199.30  193.47  188.75  187.25  183.10  181.82  181.39  181.37  181.78  182.14
  183.98  188.72  191.75  192.60  193.11  193.08  192.65  192.64  192.64  192.07
  192.07  191.34  189.92  188.00  184.82  182.95  180.57  178.80  178.30  177.26
  176.48  175.63  174.53  174.14  174.34  174.21  174.30  175.27  175.41  175.16
  175.42  174.59  174.68  175.05  174.73  174.72  174.37  175.11  175.40  174.44
  173.39  172.43  172.17  172.38  172.97  172.60  172.53  173.08  173.15  174.09
 -800.70 -806.53 -811.25 -812.75 -816.90 -818.18 -818.61 -818.63 -818.22 -817.86
 -816.02 -811.28 -808.25 -807.40 -806.89 -806.92 -807.35 -807.36  187.64  187.07
 -807.93 -808.66 -810.08 -812.00 -815.18 -817.05 -819.43 -821.20 -821.70 -822.74
 -823.52 -824.37 -825.47 -825.86 -825.66 -825.79 -825.70 -824.73 -824.59 -824.84
 -824.58 -825.41 -825.32 -824.95 -825.27 -825.28 -825.63 -824.89 -824.60 -825.56
 -826.61 -827.57 -827.83 -827.62 -827.03 -827.40 -827.47 -826.92 -826.85 -825.91
 9227.87 9276.21 9329.38 9347.49 9404.51 9427.60 9441.64 9469.70 9483.73 9511.79
 9577.64 9673.16 9748.58 9791.64 9841.97 9862.38 9864.77 9871.88 9871.8810128.12
10128.1210192.5810235.1910276.0110326.4110361.5710398.3510429.9210450.9410461.44
10471.9510492.9610566.4510629.4210692.3910721.5010726.8410738.6210759.3510785.73
10797.5110856.4010891.8410903.5110915.2910938.8510950.6310967.5410986.4711056.63
11081.1011115.5211150.8611162.6311174.4111194.6611221.5311289.2911346.0711414.31
  199.30  193.47  188.75  187.25  183.10  181.82  181.39  181.37  181.78  182.14
  183.98  188.72  191.75  192.60  193.11  193.08  192.65  192.64  192.64  192.07
  192.07  191.34  189.92  188.00  184.82  182.95  180.57  178.80  178.30  177.26
  176.48  175.63  174.53  174.14  174.34  174.21  174.30  175.27  175.41  175.16
  175.42  174.59  174.68  175.05  174.73  174.72  174.37  175.11  175.40  174.44
  173.39  172.43  172.17  172.38  172.97  172.60  172.53  173.08  173.15  174.09
 -800.70 -806.53 -811.25 -812.75 -816.90 -818.18 -818.61 -818.63 -818.22 -817.86
 -816.02 -811.28 -808.25 -807.40 -806.89 -806.92 -807.35 -807.36  187.64  187.07
 -807.93 -808.66 -810.08 -812.00 -815.18 -817.05 -819.43 -821.20 -821.70 -822.74
 -823.52 -824.37 -825.47 -825.86 -825.66 -825.79 -825.70 -824.73 -824.59 -824.84
 -824.58 -825.41 -825.32 -824.95 -825.27 -825.28 -825.63 -824.89 -824.60 -825.56
 -826.61 -827.57 -827.83 -827.62 -827.03 -827.40 -827.47 -826.92 -826.85 -825.91
Pier Skew, UpSta & Num, DnSta & Num=  ,9956.63, 2 ,9956.63, 2 , 0 , 0 , 0 ,,
    4.00    4.00
 -807.55  192.45
    4.00    4.00
 -807.55  192.45
Pier Skew, UpSta & Num, DnSta & Num=  ,10043.37, 2 ,10043.37, 2 , 0 , 0 , 0 ,,
    4.00    4.00
 -807.74  192.26
    4.00    4.00
 -807.74  192.26
BR Coef=-1 , 0 , 0 ,, 0 ,,,0.8,0,1,0,
WSPro=,,,, 1 ,,,, 0 ,,,, 0 ,,,,-1 ,-1 ,-1 , 0 , 0 , 0 , 0 , 0
BC Design=,, 0 ,, 0 ,,,,,,

Type RM Length L Ch R = 1 ,126801.3,582.908200,582.908200,582.908200
XS GIS Cut Line= 6
456016.939124018841030.194080606456315.550235093841353.110747293
456340.562174022841437.361488953456200.966901779841899.985747278
456246.695681155842151.334091321456920.306792259843324.077146888
#Sta/Elev= 30
9270.065210.72179344.712203.31179429.227192.29169562.637180.7404 9685.22175.2859
9845.491 174.4879915.445169.70429930.709 167.4939952.158156.14189962.882148.2974
9973.607145.96839984.331145.924110027.23147.848410037.95157.763410048.68163.3805
10091.58164.082210154.57168.749710267.03173.466510482.89175.778410619.27174.0538
11030.95174.319511161.36172.170511503.77174.269611630.63173.425811665.22170.9313
11688.29173.281611699.82172.120211711.35176.615111722.88178.4709 11894.8189.0327
#Mann= 3 , 0 , 0
9270.065  0.0423       09270.065  0.0423       0 11894.8  0.0423       0
#XS Ineff= 2 , 0
       0 9863.43        10133.49       0
Bank Sta=9270.065,11894.8
Exp/Cntr=0.3,0.1

Type RM Length L Ch R = 1 ,126218.4,638.447800,638.447800,638.447800
XS GIS Cut Line= 2
455583.501236707841268.521591336456695.139691591843458.368234873
#Sta/Elev= 30
9672.827 216.3419724.951204.74529814.669197.09479848.313189.33969893.171185.1629
9949.245165.58039982.889144.76729994.104144.117410029.61144.931110061.39163.3814
10128.68154.457310229.61  154.4510263.26 162.769 10296.9 161.50510308.11165.7648
10364.19 171.81810604.01164.6266 10626.1 161.41710957.48 161.41711045.85170.2052
11171.65172.928111182.86174.320611194.07180.0487 11216.5171.398511238.93169.4422
 11752.8170.790411788.45166.805611810.88173.304211945.46178.294412128.67191.9374
#Mann= 3 , 0 , 0
9672.827  0.0713       09672.827  0.0713       012128.67  0.0713       0
#XS Ineff= 2 , 0
       0                10394.79       0
Bank Sta=9672.827,12128.67
Exp/Cntr=0.3,0.1

Type RM Length L Ch R = 1 ,125579.9,477.475900,477.475900,477.475900
XS GIS Cut Line= 3
 455165.40878877841860.234554306  455954.4712888842706.588720948
455897.179622114843024.297054306
#Sta/Elev= 30
9703.197210.52049746.591210.45689805.416201.7125 9937.23170.31319969.478146.9512
10010.49143.472310025.22146.424710069.21164.7916 10106.2 171.60110215.86162.1493
10283.93162.473210318.51158.270310447.99159.948810479.82165.774510502.68161.6612
10523.81164.592610598.38159.616410666.74160.339410758.44165.711710803.46179.0933
 10817.1180.068910831.77174.746210860.32178.499310889.19175.575610909.51178.4562
11021.29174.492911031.45178.312611041.61187.772711061.93193.711811183.15196.4244
#Mann= 3 , 0 , 0
9703.197  0.0475       09703.197  0.0475       011183.15  0.0475       0
#XS Ineff= 2 , 0
       0                10427.09       0
Bank Sta=9703.197,11183.15
Exp/Cntr=0.3,0.1

Type RM Length L Ch R = 1 ,125102.5,1014.117000,1014.117000,1014.117000
XS GIS Cut Line= 3
454985.504274935842115.486290395455287.587608218842688.402957082
455640.886219352843169.305734858
#Sta/Elev= 30
 9544.24227.6524  9566.3226.40949600.215209.8958 9628.92 202.1479656.739191.7155
9668.044191.83429679.349188.02289701.959186.52859724.569178.96239747.179169.4235
9758.484166.83299781.094162.59419837.618159.96699871.533155.74749905.448154.9801
9961.973142.0585 10029.8143.279310057.73153.667510097.63162.255310108.94169.4929
10120.24173.351810131.55174.262310212.51176.011810339.56175.8205 10485.5172.8737
10510.32 174.81110547.54175.373510576.02180.249810659.22181.314910788.65186.8717
#Mann= 3 , 0 , 0
 9544.24  0.0454       0 9544.24  0.0454       010788.65  0.0454       0
#XS Ineff= 2 , 0
       0                10153.52       0
Bank Sta=9544.24,10788.65
Exp/Cntr=0.3,0.1

Type RM Length L Ch R = 1 ,124088.3,1232.446700,1232.446700,1232.446700
XS GIS Cut Line= 2
454338.083647937841812.171897426454178.431953281842720.102272421
#Sta/Elev= 30
9538.962211.53789582.447209.68969623.061204.55859663.675 194.3519714.442178.6492
9734.749174.92629755.055 172.709 9856.59173.53139897.203172.33659927.664166.0508
9937.817162.1859 9947.97155.50289958.124146.77299968.277141.05339978.431138.3252
9998.738138.073710019.04 139.83410039.35151.910110069.81166.247110140.89170.2696
10171.35169.859110191.65175.377210232.27179.951110262.73181.155310343.95180.6689
10374.41182.232110394.72185.081510404.87188.304910425.18189.669210460.82196.7101
#Mann= 3 , 0 , 0
9538.962    0.04       09538.962    0.04       010460.82    0.04       0
#XS Ineff= 2 , 0
       0                10142.08       0
Bank Sta=9538.962,10460.82
Exp/Cntr=0.3,0.1

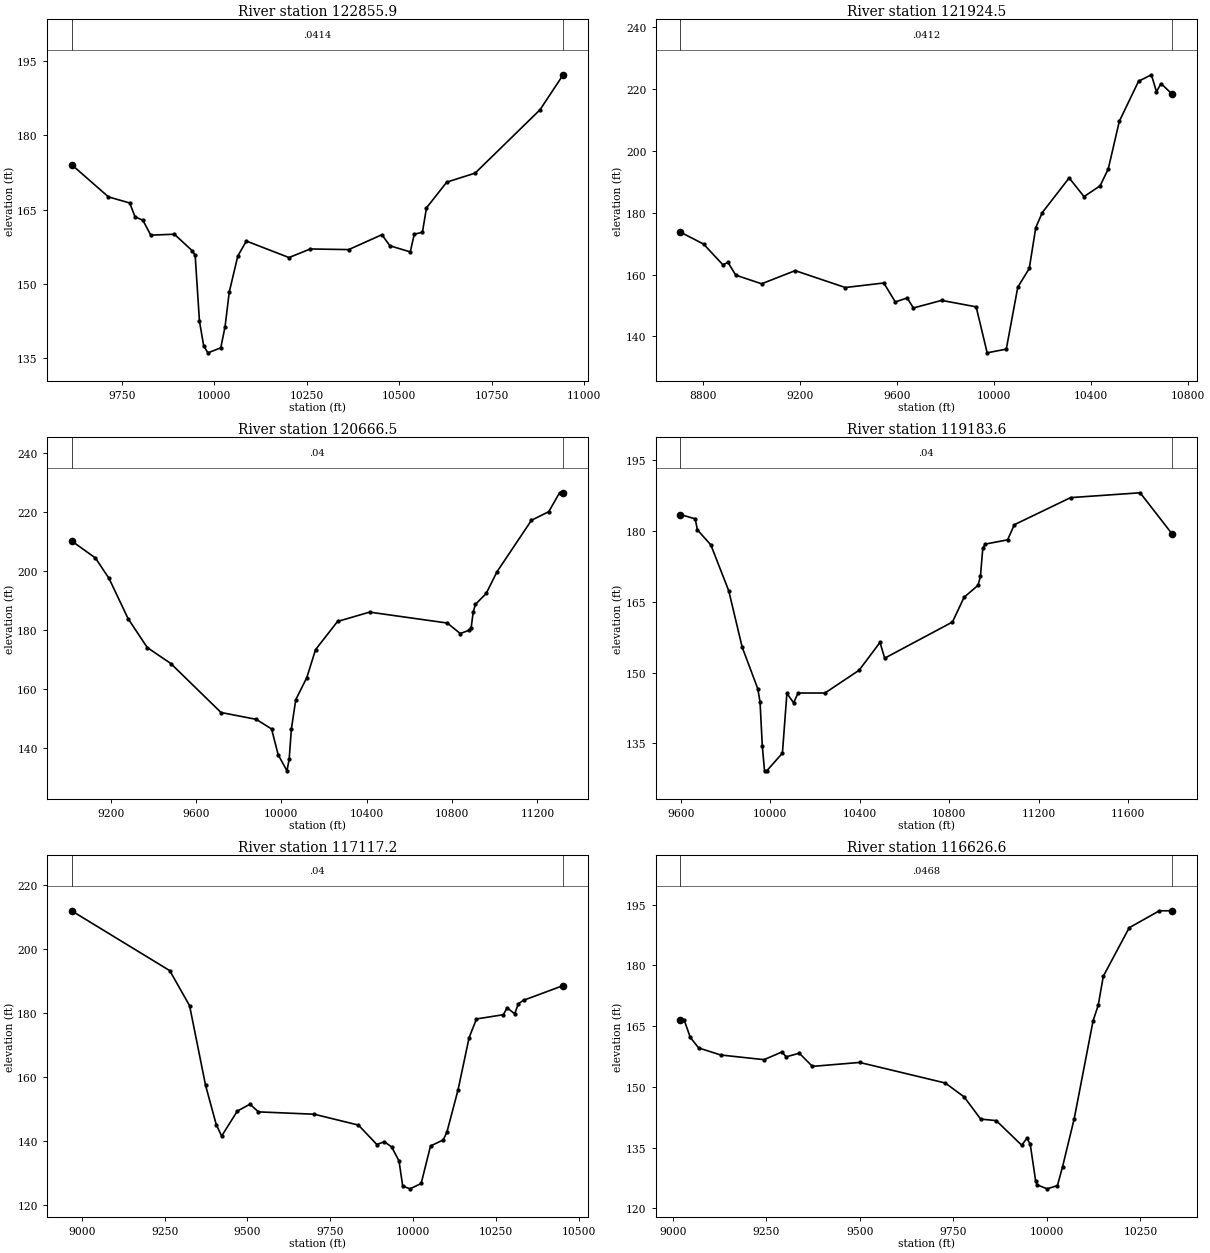
Type RM Length L Ch R = 1 ,122855.9,931.435200,931.435200,931.435200
XS GIS Cut Line= 5
453265.984262884841930.454497293453155.741207331842039.467807457
453097.917469352842200.295318171453498.623151779842430.092807457
453992.014691561842651.684207067
#Sta/Elev= 30
9614.602174.08389714.431167.55459771.833166.32939786.148163.52869807.401162.8468
9828.655 159.8289892.415160.01759940.549156.69259948.713155.75029960.241142.4863
9971.769137.43249983.296136.052110017.88137.060210029.41141.294910040.94148.3749
10063.99155.619710087.05158.635510202.32155.300810259.96157.037310363.71156.9107
10453.31159.913310475.23157.678610530.05156.444210541.01 160.04110562.93160.3861
10573.89165.337710628.71170.539910705.44172.362810880.84185.164810943.34192.2291
#Mann= 3 , 0 , 0
9614.602  0.0414       09614.602  0.0414       010943.34  0.0414       0
#XS Ineff= 2 , 0
       0                               0
Bank Sta=9614.602,10943.34
Exp/Cntr=0.3,0.1

Type RM Length L Ch R = 1 ,121924.5,1257.959300,1257.959300,1257.959300
XS GIS Cut Line= 6
453255.133568435841923.553455645453023.362735124842337.615955616
453085.862735122842588.484011164453558.953012882843165.740955582
453669.553583742843158.656221522453946.867845918843479.198006105
#Sta/Elev= 30
8707.001 173.7368802.708169.8651    8882163.18648903.298163.92158935.244159.8227
9041.731157.02959180.164 161.287 9386.71155.8208 9545.43157.28789592.759151.1575
9641.569152.44169667.428149.21689783.791151.65749926.013149.57229971.385 134.699
10050.26135.912810097.59 155.94410144.92161.983610171.67175.184610198.49180.0481
10309.31191.266810370.59185.223810436.71188.698210470.48194.163910516.05 209.584
10595.38 222.53210648.28224.620210669.17219.143110687.95221.784710733.16218.4063
#Mann= 3 , 0 , 0
8707.001  0.0412       08707.001  0.0412       010733.16  0.0412       0
#XS Ineff= 2 , 0
       0                               0
Bank Sta=8707.001,10733.16
Exp/Cntr=0.3,0.1

Type RM Length L Ch R = 1 ,120666.5,1482.929400,1482.929400,1482.929400
XS GIS Cut Line= 5
453532.379274905841684.930734858453120.920941681842013.055734858
 453059.15878877842114.010595962452458.464344352  842263.3161515
452615.712608218843291.701568186
#Sta/Elev= 30
9016.679210.14569128.441204.34349192.393197.39979281.926183.7222 9371.46173.9574
9481.916168.52979717.108151.91829881.977149.60429954.106 146.3349985.019 137.568
10026.24132.126310036.54136.082310046.84146.289210067.45156.273810118.97163.7151
10160.19173.247510263.23182.808710413.49185.976610777.67182.271110838.37178.7127
10878.83179.809710888.95180.432410899.07185.980210909.18188.584410959.76192.2983
11010.35199.6347 11172.2217.150511253.13220.053811303.72226.467711320.61226.3975
#Mann= 3 , 0 , 0
9016.679    0.04       09016.679    0.04       011320.61    0.04       0
#XS Ineff= 2 , 0
       0                               0
Bank Sta=9016.679,11320.61
Exp/Cntr=0.3,0.1

Type RM Length L Ch R = 1 ,119183.6,2066.325800,2066.325800,2066.325800
XS GIS Cut Line= 6
 452632.20566377 840638.92379041452642.622330546841302.118234843
452607.293177575841471.698169038452458.285871238841964.911118135
452422.001875192842244.539458707 452468.29198131842806.963564053
#Sta/Elev= 30
9598.127183.49459664.236182.58369674.241180.24799734.271177.0644 9814.31 167.344
 9874.34  155.419944.375146.5685 9954.38143.78029964.385134.5077 9974.39129.1969
9984.394129.190310054.43132.941410074.44145.612810104.45143.601610124.46145.6777
10244.79145.676910397.42150.505310490.88156.401910511.78153.058710814.72160.7144
10866.95 165.96710929.63168.513510940.08170.451310950.52176.300110960.61177.2238
11061.44 178.131 11091.7181.338911343.24187.079811654.29188.105211796.73179.4108
#Mann= 3 , 0 , 0
9598.127    0.04       09598.127    0.04       011796.73    0.04       0
#XS Ineff= 2 , 0
       0                               0
Bank Sta=9598.127,11796.73
Exp/Cntr=0.3,0.1

Type RM Length L Ch R = 1 ,117117.2,490.661000,490.661000,490.661000
XS GIS Cut Line= 5
451317.250314623 841364.25523074451382.723837644841690.003586844
451573.177886009841840.312679306452180.816774905842138.923790395
452291.927886069842343.784901515
#Sta/Elev= 30
8968.566211.96229265.126193.23739325.036182.2911 9373.46157.31349405.642145.0679
9421.885141.47489469.338149.30499507.555151.44969533.034149.04929701.474148.3139
9835.181 144.9119890.892138.82749913.177139.71869935.461138.07379957.746133.6803
9968.888  125.829991.173 124.969 10024.6126.640510052.89138.384210091.45140.2745
 10102.6142.796210136.02155.926310169.45172.278610191.73178.118910272.92179.4461
10284.29181.613810307.04179.730610318.42182.891510334.15183.974110453.55188.5599
#Mann= 3 , 0 , 0
8968.566    0.04       08968.566    0.04       010453.55    0.04       0
#XS Ineff= 2 , 0
       09571.276                       0
Bank Sta=8968.566,10453.55
Exp/Cntr=0.3,0.1

Type RM Length L Ch R = 1 ,116626.6,561.611400,561.611400,561.611400
XS GIS Cut Line= 3
451032.379274905841869.826568186451399.566774905842090.312679306
452049.740386009842692.743234873
#Sta/Elev= 30
9019.995 166.6079030.045166.54369046.381162.24979068.895159.63019128.031157.8898
9243.723156.74059291.332158.62889302.996157.44629337.989158.33359372.982155.0785
9499.331156.05499728.358150.97539778.882147.53029823.022142.05859864.686141.6823
 9932.85135.60039946.483137.31689955.441135.91659970.154126.72369973.748125.8281
10001.01 124.83510028.28125.641610041.91130.258410073.15142.153610123.71 166.365
10137.34170.161710150.97177.341410220.28189.330110300.94193.511910334.66193.5088
#Mann= 3 , 0 , 0
9019.995  0.0468       09019.995  0.0468       010334.66  0.0468       0
#XS Ineff= 2 , 0
       09596.948        10152.78       0
Bank Sta=9019.995,10334.66
Exp/Cntr=0.3,0.1