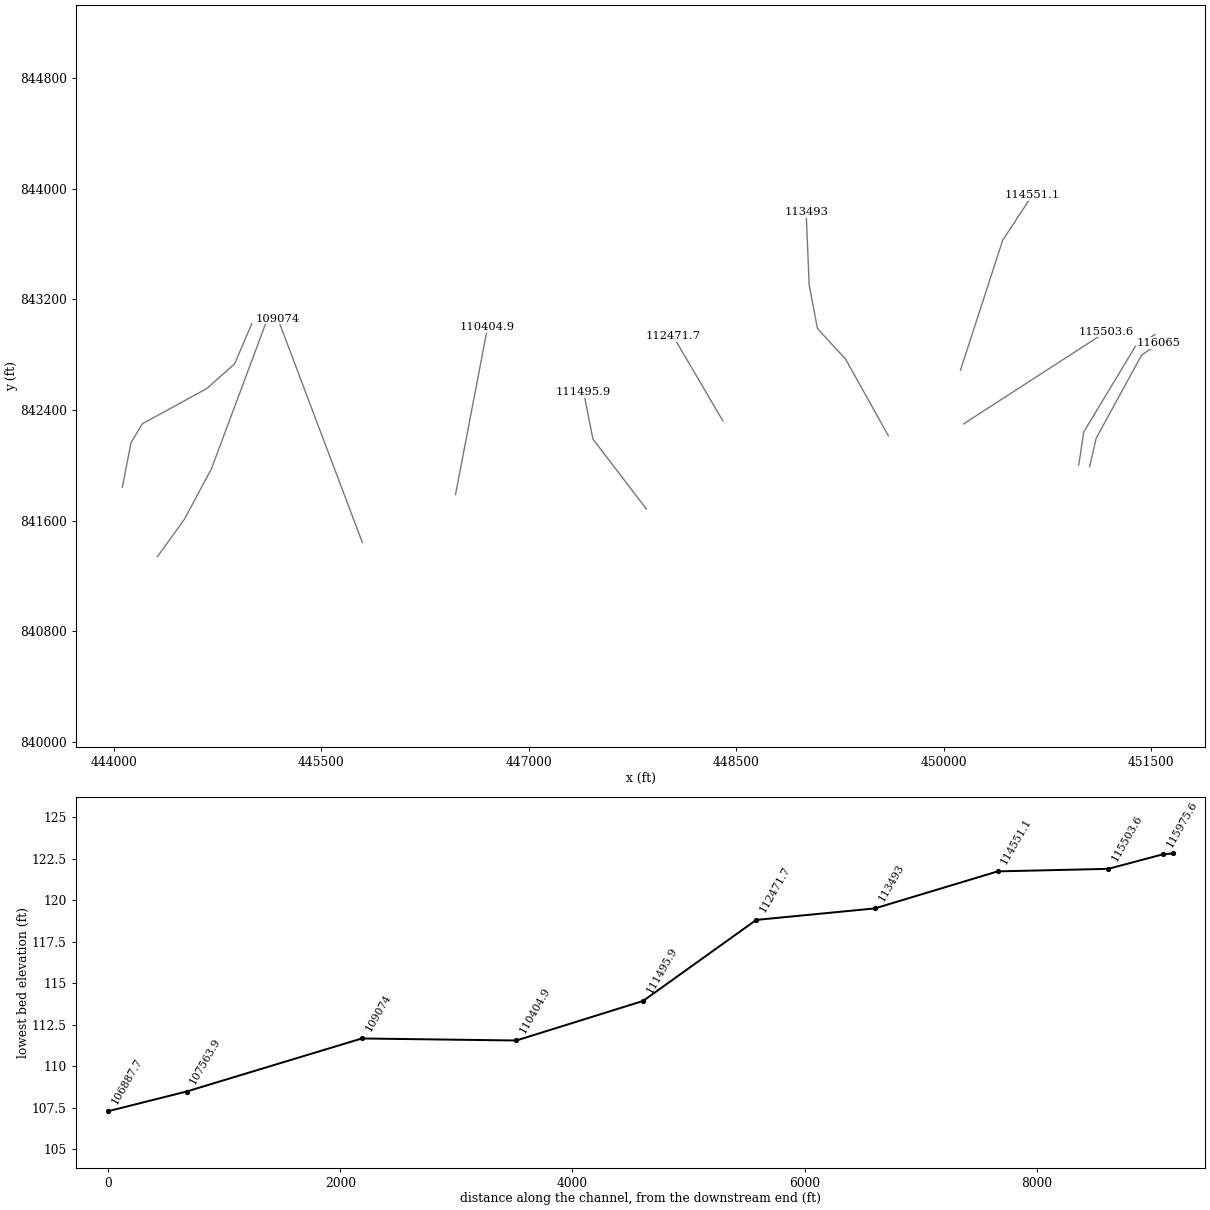
HEC-RAS study 7132_ras.prj: 7132

--- 7132_ras.g01 (geometry) --- (continued)

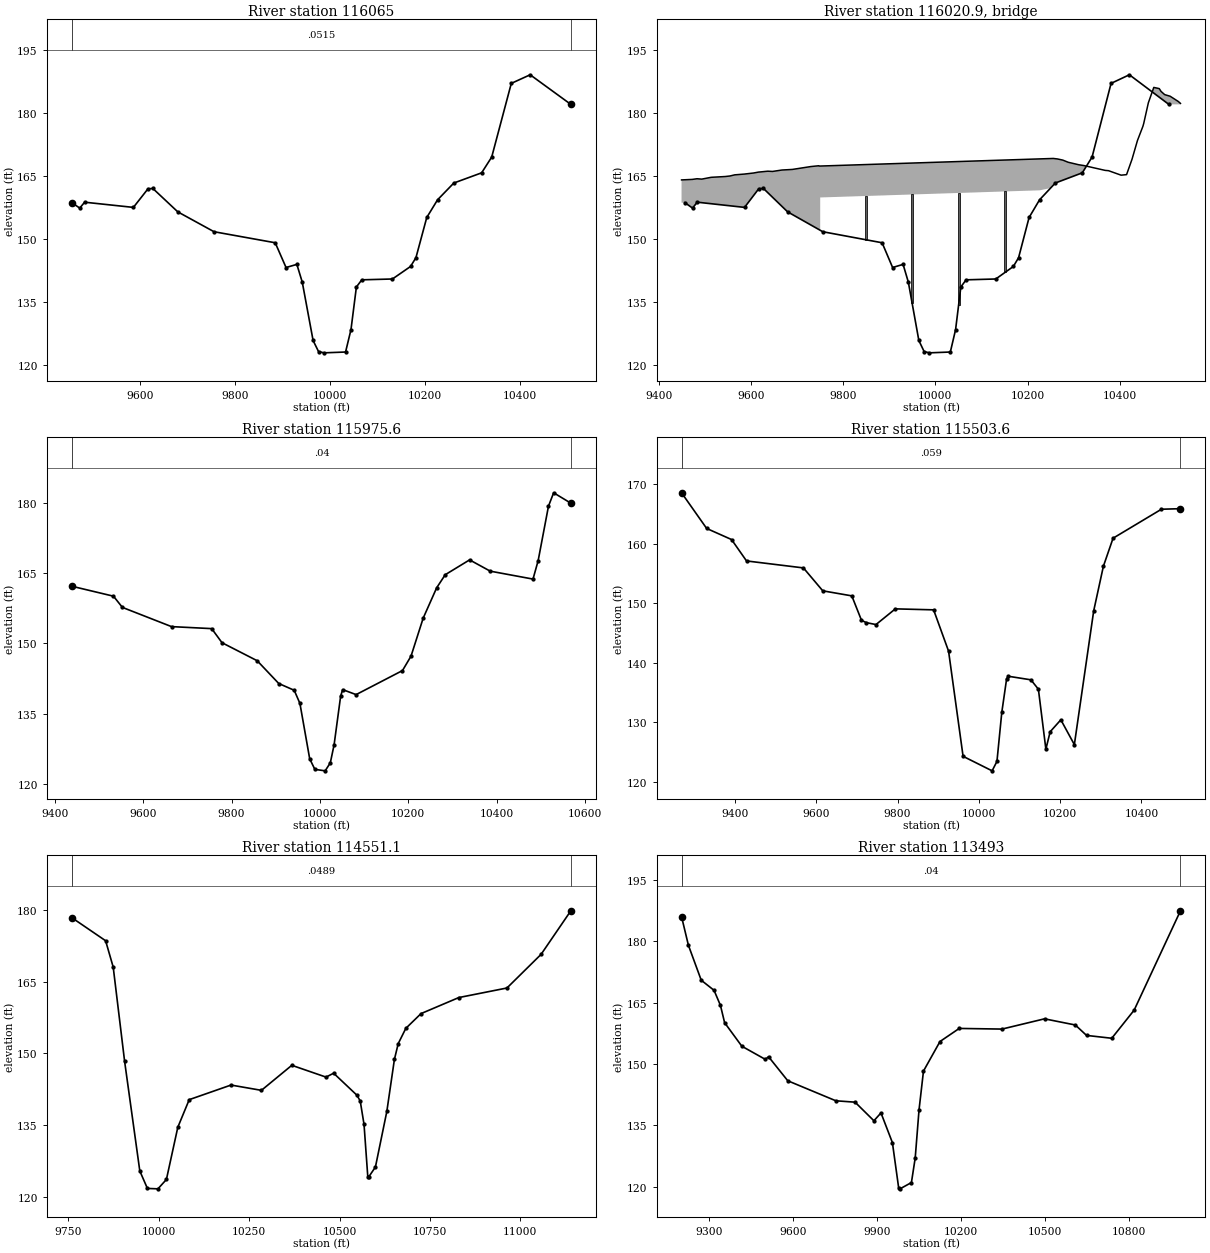
Type RM Length L Ch R = 1 ,  116065,89.366100,89.366100,89.366100
XS GIS Cut Line= 4
451055.278244358841988.961441724451103.021299914842195.124636168
451430.712272136842795.168038946451557.665397136 842884.14373339
#Sta/Elev= 30
9456.409158.63799472.872157.35239483.136158.76139585.783157.52169616.577161.9632
9626.841162.0307 9679.28156.45639755.612 151.7149884.372149.0828 9907.16143.1784
9929.948143.92229941.342139.6782 9964.13125.76029975.524123.13019986.919122.8153
10032.49123.009610043.89128.364710055.28138.534210066.68140.237110131.16140.4375
10169.22143.420510180.62145.516610203.41155.112810226.19159.338910260.38163.3356
10318.94165.770810340.13169.528610381.38187.115710421.12189.166210506.75 182.101
#Mann= 3 , 0 , 0
9456.409  0.0515       09456.409  0.0515       010506.75  0.0515       0
#XS Ineff= 2 , 0
       0 9740.29         10236.2       0
Bank Sta=9456.409,10506.75
Exp/Cntr=0.3,0.1

Type RM Length L Ch R = 3 ,116020.9,,,
BEGIN DESCRIPTION:
END DESCRIPTION:
Bridge Culvert--1,0,-1,-1, 0
Deck Dist Width WeirC Skew NumUp NumDn MinLoCord MaxHiCord MaxSubmerge Is_Ogee
28.683050,32.000000,2.6,0, 44, 44, , , 0.95, 0, 0,0,,
 9449.03 9472.34 9482.59 9492.83 9513.31 9544.04 9554.28 9564.52 9585.00 9605.48
 9615.73 9636.21 9646.45 9666.93 9689.46 9729.91 9747.02 9747.87 9750.00 9750.00
10250.0010250.0010256.0210265.0610276.5710288.0910311.1110322.6210368.6710375.84
10403.1910415.0110426.8310438.6510450.4710452.3210462.2810474.1010485.9210489.85
10497.7410509.5610527.3810532.02
  164.08  164.20  164.36  164.27  164.70  164.89  165.02  165.29  165.47  165.73
  165.94  166.16  166.10  166.44  166.58  167.27  167.46  167.39  167.39  167.39
  169.18  169.18  169.20  169.08  168.81  168.30  167.70  167.50  166.35  166.28
  165.21  165.34  169.00  173.48  176.86  177.58  182.47  186.15  185.87  185.20
  184.43  184.05  182.79  182.34
 -835.92 -835.80 -835.64 -835.73 -835.30 -835.11 -834.98 -834.71 -834.53 -834.27
 -834.06 -833.84 -833.90 -833.56 -833.42 -832.73 -832.54 -832.61 -832.61  159.89
  161.68 -830.82 -830.80 -830.92 -831.19 -831.70 -832.30 -832.50 -833.65 -833.72
 -834.79 -834.66 -831.00 -826.52 -823.14 -822.42 -817.53 -813.85 -814.13 -814.80
 -815.57 -815.95 -817.21 -817.66
 9449.03 9472.34 9482.59 9492.83 9513.31 9544.04 9554.28 9564.52 9585.00 9605.48
 9615.73 9636.21 9646.45 9666.93 9689.46 9729.91 9747.02 9747.87 9750.00 9750.00
10250.0010250.0010256.0210265.0610276.5710288.0910311.1110322.6210368.6710375.84
10403.1910415.0110426.8310438.6510450.4710452.3210462.2810474.1010485.9210489.85
10497.7410509.5610527.3810532.02
  164.08  164.20  164.36  164.27  164.70  164.89  165.02  165.29  165.47  165.73
  165.94  166.16  166.10  166.44  166.58  167.27  167.46  167.39  167.39  167.39
  169.18  169.18  169.20  169.08  168.81  168.30  167.70  167.50  166.35  166.28
  165.21  165.34  169.00  173.48  176.86  177.58  182.47  186.15  185.87  185.20
  184.43  184.05  182.79  182.34
 -835.92 -835.80 -835.64 -835.73 -835.30 -835.11 -834.98 -834.71 -834.53 -834.27
 -834.06 -833.84 -833.90 -833.56 -833.42 -832.73 -832.54 -832.61 -832.61  159.89
  161.68 -830.82 -830.80 -830.92 -831.19 -831.70 -832.30 -832.50 -833.65 -833.72
 -834.79 -834.66 -831.00 -826.52 -823.14 -822.42 -817.53 -813.85 -814.13 -814.80
 -815.57 -815.95 -817.21 -817.66
Pier Skew, UpSta & Num, DnSta & Num=  ,9848.80, 2 ,9848.80, 2 , 0 , 0 , 0 ,,
    4.00    4.00
 -832.25  167.75
    4.00    4.00
 -832.25  167.75
Pier Skew, UpSta & Num, DnSta & Num=  ,9949.60, 2 ,9949.60, 2 , 0 , 0 , 0 ,,
    4.00    4.00
 -831.89  168.11
    4.00    4.00
 -831.89  168.11
Pier Skew, UpSta & Num, DnSta & Num=  ,10050.40, 2 ,10050.40, 2 , 0 , 0 , 0 ,,
    4.00    4.00
 -831.53  168.47
    4.00    4.00
 -831.53  168.47
Pier Skew, UpSta & Num, DnSta & Num=  ,10151.20, 2 ,10151.20, 2 , 0 , 0 , 0 ,,
    4.00    4.00
 -831.17  168.83
    4.00    4.00
 -831.17  168.83
BR Coef=-1 , 0 , 0 ,, 0 ,,,0.8,0,1,0,
WSPro=,,,, 1 ,,,, 0 ,,,, 0 ,,,,-1 ,-1 ,-1 , 0 , 0 , 0 , 0 , 0
BC Design=,, 0 ,, 0 ,,,,,,

Type RM Length L Ch R = 1 ,115975.6,472.033100,472.033100,472.033100
XS GIS Cut Line= 4
450977.153244358842001.982275057451012.960536025842240.697552835
451386.224424914842859.187136168451528.368522136842944.907622279
#Sta/Elev= 30
9438.427162.21759532.485160.09469552.709157.7011 9663.94153.59189754.918153.1621
9778.278150.14939857.941146.29829906.758141.43179941.798139.98219954.709137.1729
9976.838125.33629988.518 123.07810011.88122.763510023.56124.483210032.12128.3434
10046.92138.738210051.48 140.12410081.96139.057710186.95144.1971 10206.3147.2842
 10233.8155.397910264.36161.888310283.72164.682210338.92167.857810385.64165.4458
10482.52163.7507 10494.2167.710510517.56179.343710529.23182.1993 10568.2 179.977
#Mann= 3 , 0 , 0
9438.427    0.04       09438.427    0.04       0 10568.2    0.04       0
#XS Ineff= 2 , 0
       09741.531        10262.16       0
Bank Sta=9438.427,10568.2
Exp/Cntr=0.3,0.1

Type RM Length L Ch R = 1 ,115503.6,952.465300,952.465300,952.465300
XS GIS Cut Line= 2
450143.085293442842298.183049649451174.335293442842964.849716336
#Sta/Elev= 30
9268.239168.51699330.057162.53429391.313160.67399428.153157.0866 9568.21155.9164
 9615.84152.07419687.286151.22819711.101147.13329722.867 146.7429746.824146.4153
9794.455149.04879888.643148.88439925.439141.95939961.162124.321510032.61121.8847
10044.52 123.46810056.42131.679310068.33137.326610072.84137.7427 10128.1137.1486
10146.52135.574610164.94125.5217 10175.5128.441810201.78130.443310235.04126.2821
10282.67148.727410306.48156.1896 10330.3160.898210449.37165.757810496.21165.8496
#Mann= 3 , 0 , 0
9268.239   0.059       09268.239   0.059       010496.21   0.059       0
#XS Ineff= 2 , 0
       0                10368.08       0
Bank Sta=9268.239,10496.21
Exp/Cntr=0.3,0.1

Type RM Length L Ch R = 1 ,114551.1,1058.159100,1058.159100,1058.159100
XS GIS Cut Line= 3
450121.499645263842686.377494097450427.055200815843627.349716321
450642.332978606843953.738605216
#Sta/Elev= 30
9759.582178.3145 9852.76173.51799873.788168.0191 9905.33148.34669947.386125.4613
9968.414121.81819997.564121.733210020.98 123.68810052.53134.586410084.07140.3489
10199.72 143.39710283.83 142.29210367.95 147.51810462.57145.0554 10483.6145.8682
   10548141.2805 10557.2140.064310567.71 135.19410578.23124.150210580.38124.1832
10599.25126.2881 10630.8137.891410651.82 148.77310662.34152.045210683.37155.2309
10725.42158.310210829.96161.658210963.13163.653811057.57170.679611139.91179.7715
#Mann= 3 , 0 , 0
9759.582  0.0489       09759.582  0.0489       011139.91  0.0489       0
#XS Ineff= 2 , 0
       0                10682.86       0
Bank Sta=9759.582,11139.91
Exp/Cntr=0.3,0.1

Type RM Length L Ch R = 1 ,  113493,1021.269600,1021.269600,1021.269600
XS GIS Cut Line= 5
449599.983105481 842213.57081674 449290.95532769842767.390261173
 449087.83032769842987.876372293449027.624307424843303.926889986
449005.932515651843830.301105216
#Sta/Elev= 30
9200.499 185.9849225.039178.98699270.844170.4518 9316.65167.98159339.553164.2929
9354.383160.07739415.951154.33059499.873151.11799511.325151.76999580.033145.8952
9751.805 141.0079820.514140.66779887.769136.12669913.033138.04629953.823130.7989
9976.322119.68419981.017119.502110021.81121.035810035.36127.0533   10049138.7972
10064.88148.266410123.91 155.48510192.64158.676910345.34158.518910497.33161.0229
10607.43159.516110647.46156.972710737.54156.274510817.61163.150910983.05 187.411
#Mann= 3 , 0 , 0
9200.499    0.04       09200.499    0.04       010983.05    0.04       0
#XS Ineff= 2 , 0
       09787.077        10109.62       0
Bank Sta=9200.499,10983.05
Exp/Cntr=0.3,0.1

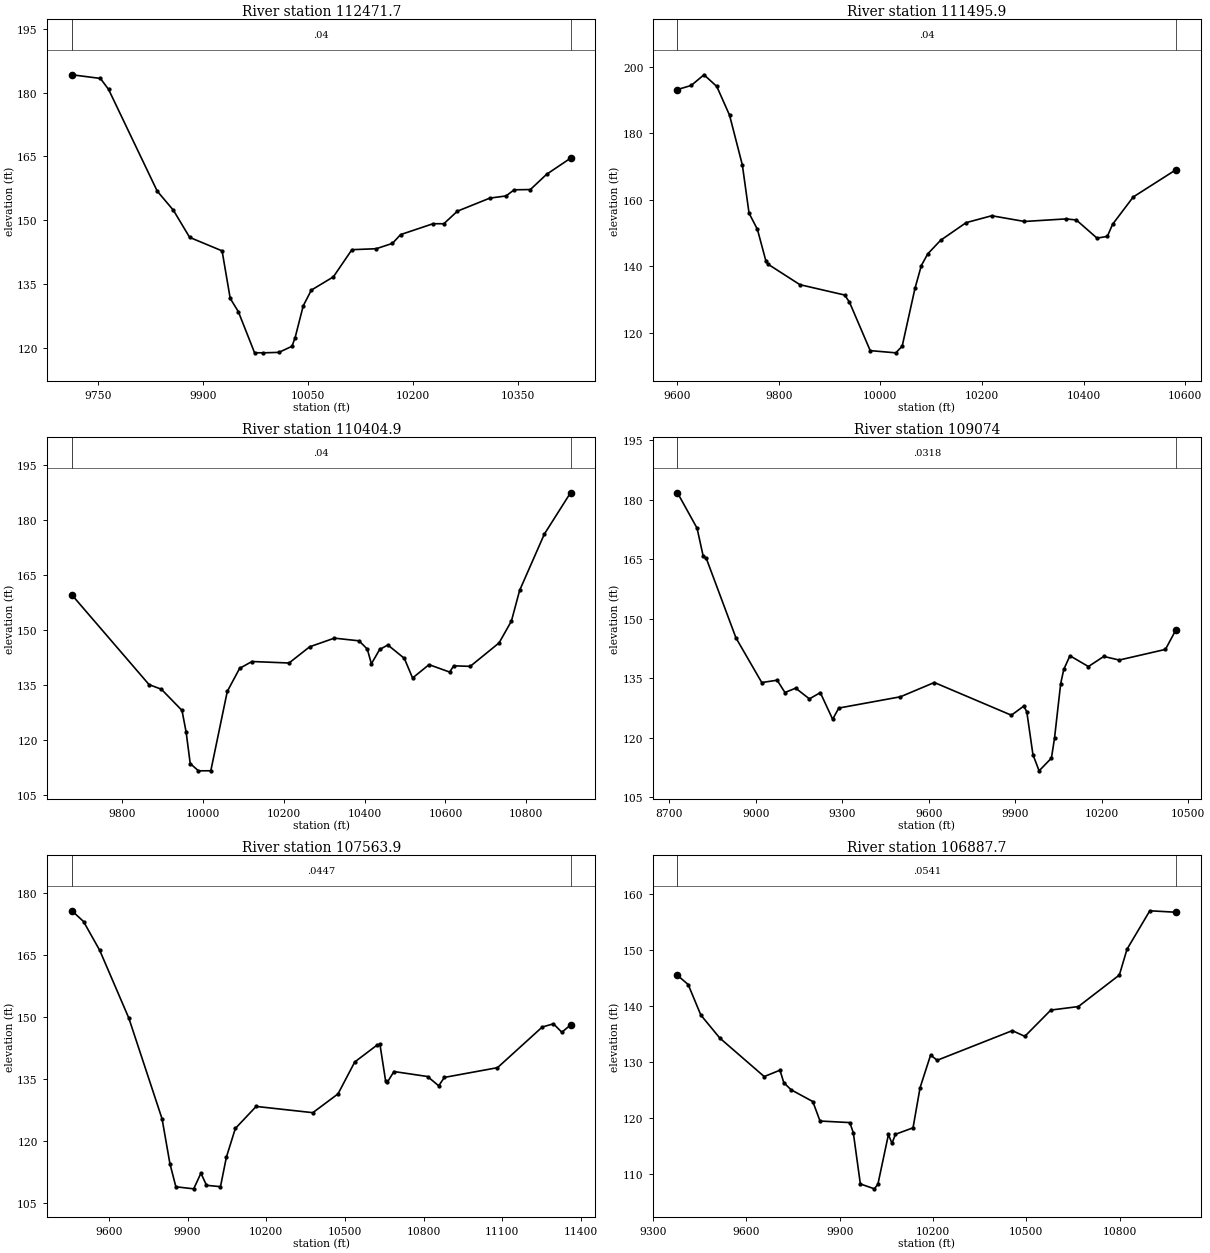
Type RM Length L Ch R = 1 ,112471.7,975.736800,975.736800,975.736800
XS GIS Cut Line= 2
448404.370015621842319.884438559448043.258904517842934.467771873
#Sta/Elev= 30
9712.607184.17339753.335183.31439764.934180.76479834.524156.83839857.721152.3229
9880.918145.95369927.312142.7774 9938.91131.60469950.509128.50499973.706118.8432
9985.304118.8109 10008.5118.9195 10027.2120.3503 10031.7122.3703 10043.3129.8641
10054.89 133.55410086.42 136.67610112.89 143.05810147.68143.287110170.88 144.545
10182.48146.600110228.87149.160510244.33149.157110263.67152.109810310.06155.1794
10333.26155.692210344.86157.132510368.05157.197210391.25160.781610425.43 164.559
#Mann= 3 , 0 , 0
9712.607    0.04       09712.607    0.04       010425.43    0.04       0
#XS Ineff= 2 , 0
       0                               0
Bank Sta=9712.607,10425.43
Exp/Cntr=0.3,0.1

Type RM Length L Ch R = 1 ,111495.9,1091.080800,1091.080800,1091.080800
XS GIS Cut Line= 3
447850.547341581841683.492691724447464.262619359842189.135052836
447396.988313803842527.676719502
#Sta/Elev= 30
 9600.55193.09729627.616194.32819652.784197.53829677.952194.03289703.121185.3732
9728.289170.41359741.469155.91979757.941151.05769774.414141.67719778.626140.6028
9841.547134.42579929.636131.31159939.139 129.1689979.973114.596210030.31113.9272
10042.89 115.91710068.06133.296910080.65140.186210093.23143.6864 10118.4147.7521
10168.74153.072710219.17155.147510283.62153.429210365.19154.198710385.58153.8892
10426.36148.424710446.75148.936210456.95152.552510497.73 160.79610582.02169.0082
#Mann= 3 , 0 , 0
 9600.55    0.04       0 9600.55    0.04       010582.02    0.04       0
#XS Ineff= 2 , 0
       0                10212.49       0
Bank Sta=9600.55,10582.02
Exp/Cntr=0.3,0.1

Type RM Length L Ch R = 1 ,110404.9,1330.849300,1330.849300,1330.849300
XS GIS Cut Line= 2
446470.339008248841787.659358391446702.543869359842998.596858391
#Sta/Elev= 30
9676.259159.50859867.012135.06049897.559133.7869 9948.47128.01679958.652122.1577
9968.834113.53469989.199111.548210019.75111.573210060.47133.203710091.02 139.488
10121.57141.352810213.21140.944410264.12145.360310325.21147.7241 10386.3146.9928
10406.67144.742710416.85140.728110437.22144.629610457.58145.860310498.31142.2089
10518.67136.8575 10559.4140.500210610.31138.478510620.49140.182810661.22 140.032
 10732.5146.416410763.05152.368910783.41160.7432 10844.5176.080810909.26187.3549
#Mann= 3 , 0 , 0
9676.259    0.04       09676.259    0.04       010909.26    0.04       0
#XS Ineff= 2 , 0
       0                10154.51       0
Bank Sta=9676.259,10909.26
Exp/Cntr=0.3,0.1

Type RM Length L Ch R = 1 ,  109074,1510.165000,1510.165000,1510.165000
XS GIS Cut Line= 2
445796.731126755841441.412216336445185.620015621843059.467771873
#Sta/Elev= 30
8728.449181.79718796.421172.8751  8817.8165.78938828.489165.25858931.468145.1891
9020.899133.94049074.347134.52869101.284131.42279138.483132.51789186.193129.8162
9223.999131.39459266.757124.67659288.136127.50489501.925130.34649619.509133.9484
9886.745125.69939929.503127.98529940.192126.59479961.571115.7604 9982.95111.6699
10025.71114.8807 10036.4119.888710057.78133.654810068.47137.240610089.84140.6934
10153.98137.974910207.43140.522110260.88139.612810421.22142.295810458.06147.2965
#Mann= 3 , 0 , 0
8728.449  0.0318       08728.449  0.0318       010458.06  0.0318       0
#XS Ineff= 2 , 0
       09262.003        10106.17       0
Bank Sta=8728.449,10458.06
Exp/Cntr=0.3,0.1

Type RM Length L Ch R = 1 ,107563.9,676.113700,676.113700,676.113700
XS GIS Cut Line= 4
444314.960293472841338.981660768444510.272793412841609.814994097
444705.585293412841974.398327425445109.231126785843055.995549664
#Sta/Elev= 30
9458.732175.7236 9503.14173.12239564.785166.15579675.747149.78179802.656125.4001
9832.561114.5789 9855.25  108.979923.317108.47429950.891112.26419972.068109.3312
10025.42108.996410048.11 116.16210082.14123.071710161.55128.406410377.67126.8938
10473.73 131.43210537.77139.167110623.16143.263510633.84143.396210655.19134.6503
10662.19 134.28410687.21 136.84310815.29135.640510857.99133.388510879.33135.4206
11082.13137.777511252.91147.611111295.61148.385211327.63 146.34211360.71148.1019
#Mann= 3 , 0 , 0
9458.732  0.0447       09458.732  0.0447       011360.71  0.0447       0
#XS Ineff= 2 , 0
       09879.289        10558.41       0
Bank Sta=9458.732,11360.71
Exp/Cntr=0.3,0.1

Type RM Length L Ch R = 1 ,106887.7,98.178600,98.178600,98.178600
XS GIS Cut Line= 6
444061.745258247 841841.21838617444123.663361907842162.108481556
444205.260584146842299.261259347444672.595952692842555.020469503
444873.550813803842733.839913948444996.954712927843022.539037123
#Sta/Elev= 30
9378.753145.41669413.158143.77969453.896138.32559515.003134.20619657.585127.3393
9708.177128.47649720.563126.23919743.835124.9831 9813.65122.87899836.922119.3984
 9932.59119.12089943.879117.30219966.456108.163210011.61107.2876 10022.9108.1175
10056.77116.995510068.05115.408110079.34117.030510135.79118.186710158.36125.3463
10192.23131.176310213.39130.250310454.82135.541910494.98134.522310578.55139.2152
10667.06139.842610798.82145.4773 10823.4150.0865 10896.7156.949210981.03156.6882
#Mann= 3 , 0 , 0
9378.753  0.0541       09378.753  0.0541       010981.03  0.0541       0
#XS Ineff= 2 , 0
       09859.476         10212.8       0
Bank Sta=9378.753,10981.03
Exp/Cntr=0.3,0.1