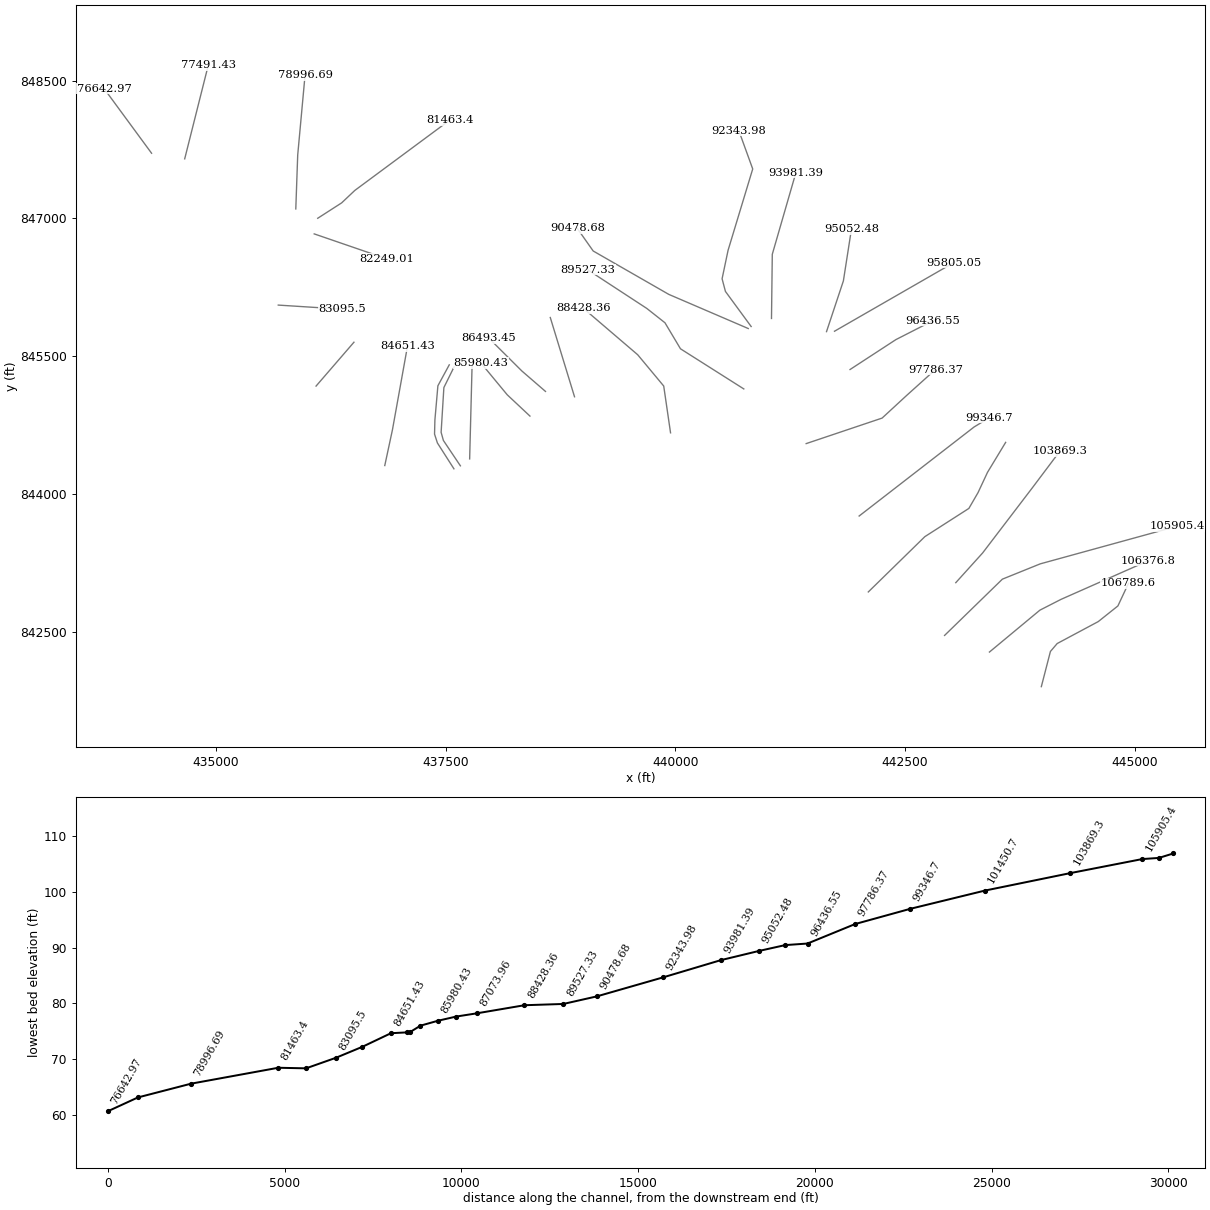
HEC-RAS study 7132_ras.prj: 7132

--- 7132_ras.g01 (geometry) --- (continued)

Type RM Length L Ch R = 3 ,106843.5,,,
BEGIN DESCRIPTION:
END DESCRIPTION:
Bridge Culvert--1,0,-1,-1, 0
Deck Dist Width WeirC Skew NumUp NumDn MinLoCord MaxHiCord MaxSubmerge Is_Ogee
29.404300,39.370000,2.6,0, 60, 60, , , 0.95, 0, 0,0,,
 9335.81 9349.84 9370.20 9380.38 9410.92 9441.46 9482.18 9522.91 9533.09 9563.63
 9614.53 9667.12 9678.23 9699.38 9722.36 9755.97 9758.97 9765.16 9795.21 9831.56
 9835.53 9849.08 9849.0810150.9210150.9210189.0110195.8710207.3910253.4610264.97
10288.0110311.0410322.5610334.0710359.1210410.6010435.9710449.2010474.9410531.30
10590.7510629.3610650.7410683.6010705.5010716.4610727.4110738.3610747.9810771.22
10782.1710793.1310804.0810815.0310825.9910836.9410847.8910869.8010902.6610915.61
  144.51  143.61  142.03  141.09  138.58  136.60  134.74  133.67  133.57  133.75
  134.33  135.38  135.40  136.03  136.31  137.37  137.32  137.61  138.12  139.17
  139.25  139.18  139.18  137.78  137.78  137.60  137.69  137.30  136.64  136.62
  136.31  136.26  136.07  136.16  136.09  136.51  136.95  137.34  137.80  139.05
  141.08  142.20  142.74  143.31  144.99  146.50  147.81  149.72  150.72  152.31
  152.78  153.90  154.57  155.42  157.44  158.36  159.02  159.11  158.41  158.32
 -855.49 -856.39 -857.97 -858.91 -861.42 -863.40 -865.26 -866.33 -866.43 -866.25
 -865.67 -864.62 -864.60 -863.97 -863.69 -862.63 -862.68 -862.39 -861.88 -860.83
 -860.75 -860.82  132.68  131.28 -862.22 -862.40 -862.31 -862.70 -863.36 -863.38
 -863.69 -863.74 -863.93 -863.84 -863.91 -863.49 -863.05 -862.66 -862.20 -860.95
 -858.92 -857.80 -857.26 -856.69 -855.01 -853.50 -852.19 -850.28 -849.28 -847.69
 -847.22 -846.10 -845.43 -844.58 -842.56 -841.64 -840.98 -840.89 -841.59 -841.68
 9335.81 9349.84 9370.20 9380.38 9410.92 9441.46 9482.18 9522.91 9533.09 9563.63
 9614.53 9667.12 9678.23 9699.38 9722.36 9755.97 9758.97 9765.16 9795.21 9831.56
 9835.53 9849.08 9849.0810150.9210150.9210189.0110195.8710207.3910253.4610264.97
10288.0110311.0410322.5610334.0710359.1210410.6010435.9710449.2010474.9410531.30
10590.7510629.3610650.7410683.6010705.5010716.4610727.4110738.3610747.9810771.22
10782.1710793.1310804.0810815.0310825.9910836.9410847.8910869.8010902.6610915.61
  144.51  143.61  142.03  141.09  138.58  136.60  134.74  133.67  133.57  133.75
  134.33  135.38  135.40  136.03  136.31  137.37  137.32  137.61  138.12  139.17
  139.25  139.18  139.18  137.78  137.78  137.60  137.69  137.30  136.64  136.62
  136.31  136.26  136.07  136.16  136.09  136.51  136.95  137.34  137.80  139.05
  141.08  142.20  142.74  143.31  144.99  146.50  147.81  149.72  150.72  152.31
  152.78  153.90  154.57  155.42  157.44  158.36  159.02  159.11  158.41  158.32
 -855.49 -856.39 -857.97 -858.91 -861.42 -863.40 -865.26 -866.33 -866.43 -866.25
 -865.67 -864.62 -864.60 -863.97 -863.69 -862.63 -862.68 -862.39 -861.88 -860.83
 -860.75 -860.82  132.68  131.28 -862.22 -862.40 -862.31 -862.70 -863.36 -863.38
 -863.69 -863.74 -863.93 -863.84 -863.91 -863.49 -863.05 -862.66 -862.20 -860.95
 -858.92 -857.80 -857.26 -856.69 -855.01 -853.50 -852.19 -850.28 -849.28 -847.69
 -847.22 -846.10 -845.43 -844.58 -842.56 -841.64 -840.98 -840.89 -841.59 -841.68
Pier Skew, UpSta & Num, DnSta & Num=  ,9949.03, 2 ,9949.03, 2 , 0 , 0 , 0 ,,
    4.00    4.00
 -861.28  138.72
    4.00    4.00
 -861.28  138.72
Pier Skew, UpSta & Num, DnSta & Num=  ,10050.97, 2 ,10050.97, 2 , 0 , 0 , 0 ,,
    4.00    4.00
 -861.75  138.25
    4.00    4.00
 -861.75  138.25
BR Coef=-1 , 0 , 0 ,, 0 ,,,0.8,0,1,0,
WSPro=,,,, 1 ,,,, 0 ,,,, 0 ,,,,-1 ,-1 ,-1 , 0 , 0 , 0 , 0 , 0
BC Design=,, 0 ,, 0 ,,,,,,

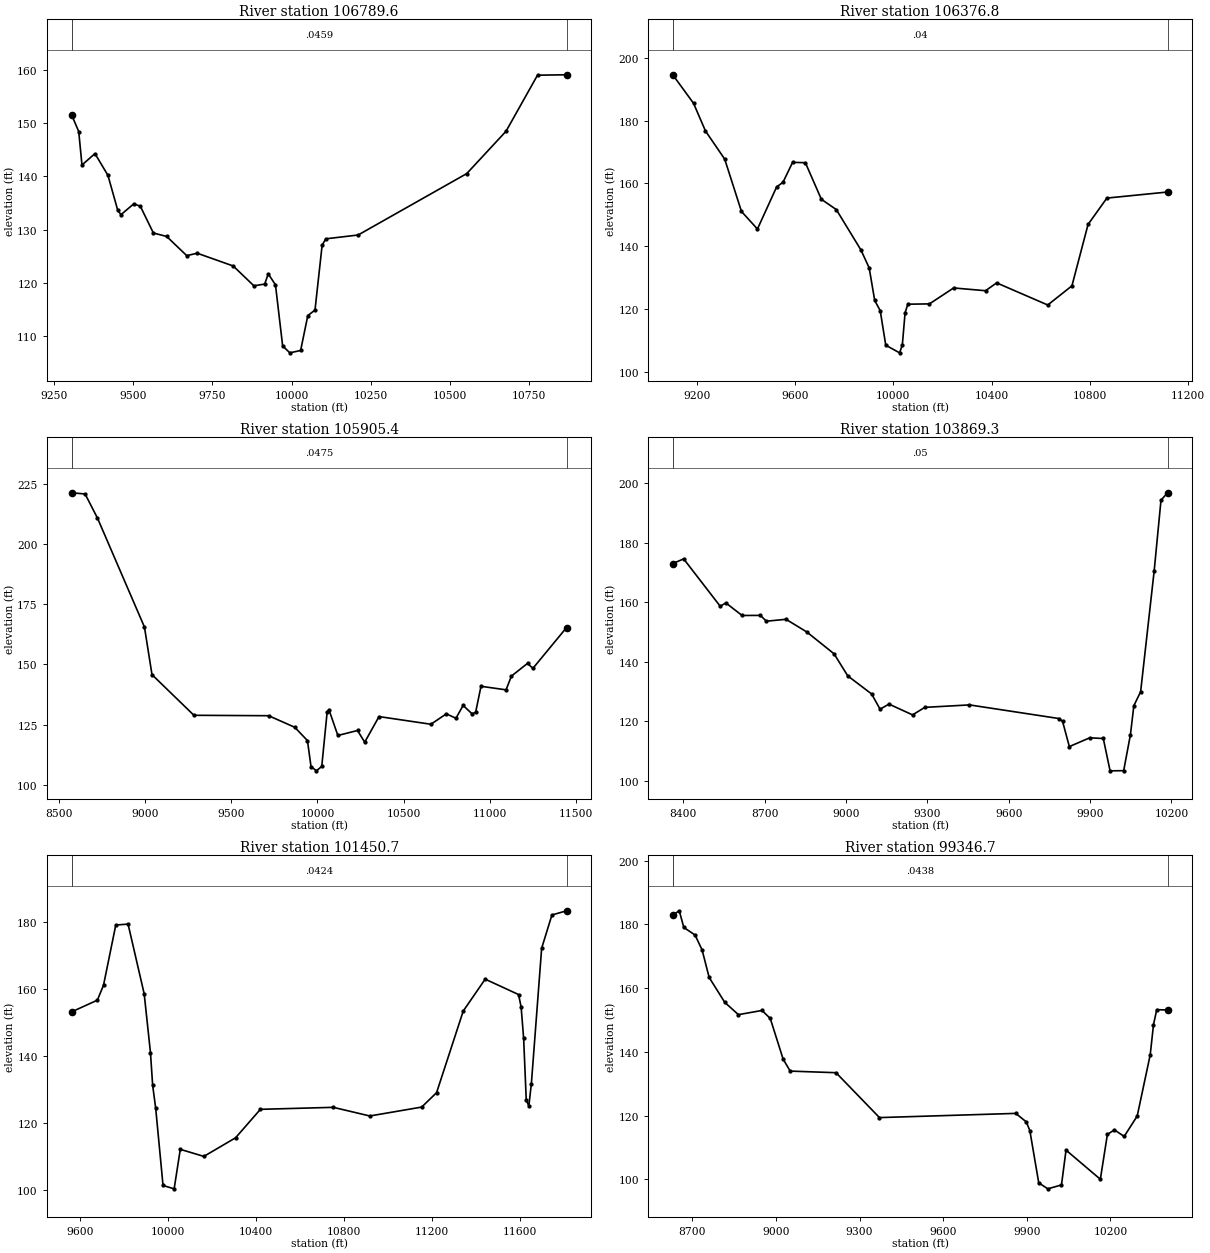
Type RM Length L Ch R = 1 ,106789.6,412.797900,412.797900,412.797900
XS GIS Cut Line= 6
443984.774473041841903.427925989444083.620258247842286.357275059
 444157.40498047842372.728802837444604.566139728842611.761259332
444818.107806355842781.900148213444933.446647136843028.110747281
#Sta/Elev= 30
9306.265 151.4759328.356148.40129338.596142.12229379.559144.26419420.521140.1913
9451.243 133.6839461.484132.81219502.446134.86049522.928134.3769 9563.89129.3834
9606.007128.72969669.189125.13519702.209125.59359815.806123.20019881.113119.4811
9915.131 119.809 9926.47121.72249949.148119.66669971.826108.21639994.504106.9221
10028.52107.3648 10051.2113.906610073.88114.936810096.38127.0869 10107.9128.2879
10209.95 129.00610552.71140.5168 10676.6148.446510775.99158.959610867.77159.0349
#Mann= 3 , 0 , 0
9306.265  0.0459       09306.265  0.0459       010867.77  0.0459       0
#XS Ineff= 2 , 0
       09813.948        10175.99       0
Bank Sta=9306.265,10867.77
Exp/Cntr=0.3,0.1

Type RM Length L Ch R = 1 ,106376.8,471.331600,471.331600,471.331600
XS GIS Cut Line= 4
443419.923401475842280.031339467443969.107503921842735.977629378
444198.381542981842853.200446367445150.897793412843274.745549664
#Sta/Elev= 30
 9103.07194.57539187.651 185.5059236.089176.70689314.364167.75019382.609151.0908
9447.595145.50019525.579158.89219551.573160.38219590.565166.71579642.554 166.602
 9707.54154.9684 9768.36151.68829868.399138.85989902.092133.13379924.555 122.764
9947.017119.5224 9969.48108.539610025.64106.110410036.87108.5714 10048.1118.8637
10059.33121.586110147.21 121.68410245.63126.755310375.32125.8737 10420.6128.3662
10628.37121.330710726.79127.424410792.41146.971710868.95155.347511115.99157.2772
#Mann= 3 , 0 , 0
 9103.07    0.04       0 9103.07    0.04       011115.99    0.04       0
#XS Ineff= 2 , 0
       09818.302        10331.28       0
Bank Sta=9103.07,11115.99
Exp/Cntr=0.3,0.1

Type RM Length L Ch R = 1 ,105905.4,2036.113500,2036.113500,2036.113500
XS GIS Cut Line= 4
442931.620037317842460.929609507443560.786703974843073.429609522
443973.286704034843240.096276179445463.397793442843649.745549649
#Sta/Elev= 30
8575.624221.19418653.138220.69698724.818 210.7078997.198165.51129040.892145.7907
9283.915128.93469717.088128.75859868.083123.97439941.853118.45859962.595107.6963
9993.708 105.90310024.82107.746310055.93130.1566 10066.3131.292910118.16120.5636
10232.24122.632110273.72117.768510356.69128.398310657.45125.223710747.04129.5361
10802.65127.699910844.13133.028810895.98129.553210916.73130.167110947.84140.9606
11093.03139.487911124.15145.182511217.49150.4608 11248.6148.385911443.99165.3306
#Mann= 3 , 0 , 0
8575.624  0.0475       08575.624  0.0475       011443.99  0.0475       0
#XS Ineff= 2 , 0
       09591.368        10540.34       0
Bank Sta=8575.624,11443.99
Exp/Cntr=0.3,0.1

Type RM Length L Ch R = 1 ,103869.3,2418.567900,2418.567900,2418.567900
XS GIS Cut Line= 4
443053.675571233843035.162216336 443345.34223789843358.078882992
443885.809205025844066.308085263444185.288371682844464.528571367
#Sta/Elev= 30
8361.728172.95468401.935174.53648536.688158.63638557.651159.74728617.327155.5326
8684.915155.56198706.841153.61428779.242154.25078855.889149.99968956.522142.6537
9006.839135.25959094.893129.18319125.978124.08169158.945125.77879245.843122.1596
9290.815124.68439455.653125.51299786.222120.92479798.734119.97339823.759111.5206
9898.832114.46659948.881114.23649973.906103.378110023.95103.433310048.98115.5347
10061.49125.233310086.52129.938810136.57  170.6110161.59194.264110186.02196.7269
#Mann= 3 , 0 , 0
8361.728    0.05       08361.728    0.05       010186.02    0.05       0
#XS Ineff= 2 , 0
       09432.442                       0
Bank Sta=8361.728,10186.02
Exp/Cntr=0.3,0.1

Type RM Length L Ch R = 1 ,101450.7,2104.042600,2104.042600,2104.042600
XS GIS Cut Line= 6
442101.527133703842934.286926985442716.870015621843536.030271888
443196.036682308843843.321938559443295.599390864844015.000000015
443399.161682308844236.551105216 443596.31880039844562.180445492
#Sta/Elev= 30
9560.306153.12769677.057156.6106 9705.03161.05919760.977179.06579816.924179.3416
9890.291158.50939918.896140.94799928.818131.19049942.805124.24259976.108101.2461
10026.73100.2348 10054.7112.037510162.04109.926510306.46115.4893 10419.5123.9948
10751.38124.589510917.69 122.00611153.98124.665411221.78128.9674 11343.2153.3625
 11443.1162.888511595.07158.293411606.76154.605711618.27145.181711630.14126.7855
11641.83124.981211653.52131.688711700.28172.118111747.04182.064911813.89183.3228
#Mann= 3 , 0 , 0
9560.306  0.0424       09560.306  0.0424       011813.89  0.0424       0
#XS Ineff= 2 , 0
       0                11441.39       0
Bank Sta=9560.306,11813.89
Exp/Cntr=0.3,0.1

Type RM Length L Ch R = 1 , 99346.7,1560.335900,1560.335900,1560.335900
XS GIS Cut Line= 3
442001.700744808843760.675815865443253.242654085844730.023363024
443418.367411464844830.120260298
#Sta/Elev= 30
8629.463182.94318652.856184.29758669.187179.05618709.528176.68638734.826171.9967
8760.123163.35948816.165 155.5348865.158151.67318949.853152.99138979.474150.4738
9025.745137.68789051.042 133.9449215.475133.44169371.416119.34429860.556120.6624
9898.502117.98499911.151115.23459942.99898.852449975.65996.9678210024.6598.19471
10040.98109.124510164.1299.9751610189.42114.053310214.55115.493410249.63113.4225
10296.41119.822910343.18139.086710354.88148.512710366.57153.245610405.59153.1387
#Mann= 3 , 0 , 0
8629.463  0.0438       08629.463  0.0438       010405.59  0.0438       0
#XS Ineff= 2 , 0
       0                10372.21       0
Bank Sta=8629.463,10405.59
Exp/Cntr=0.3,0.1

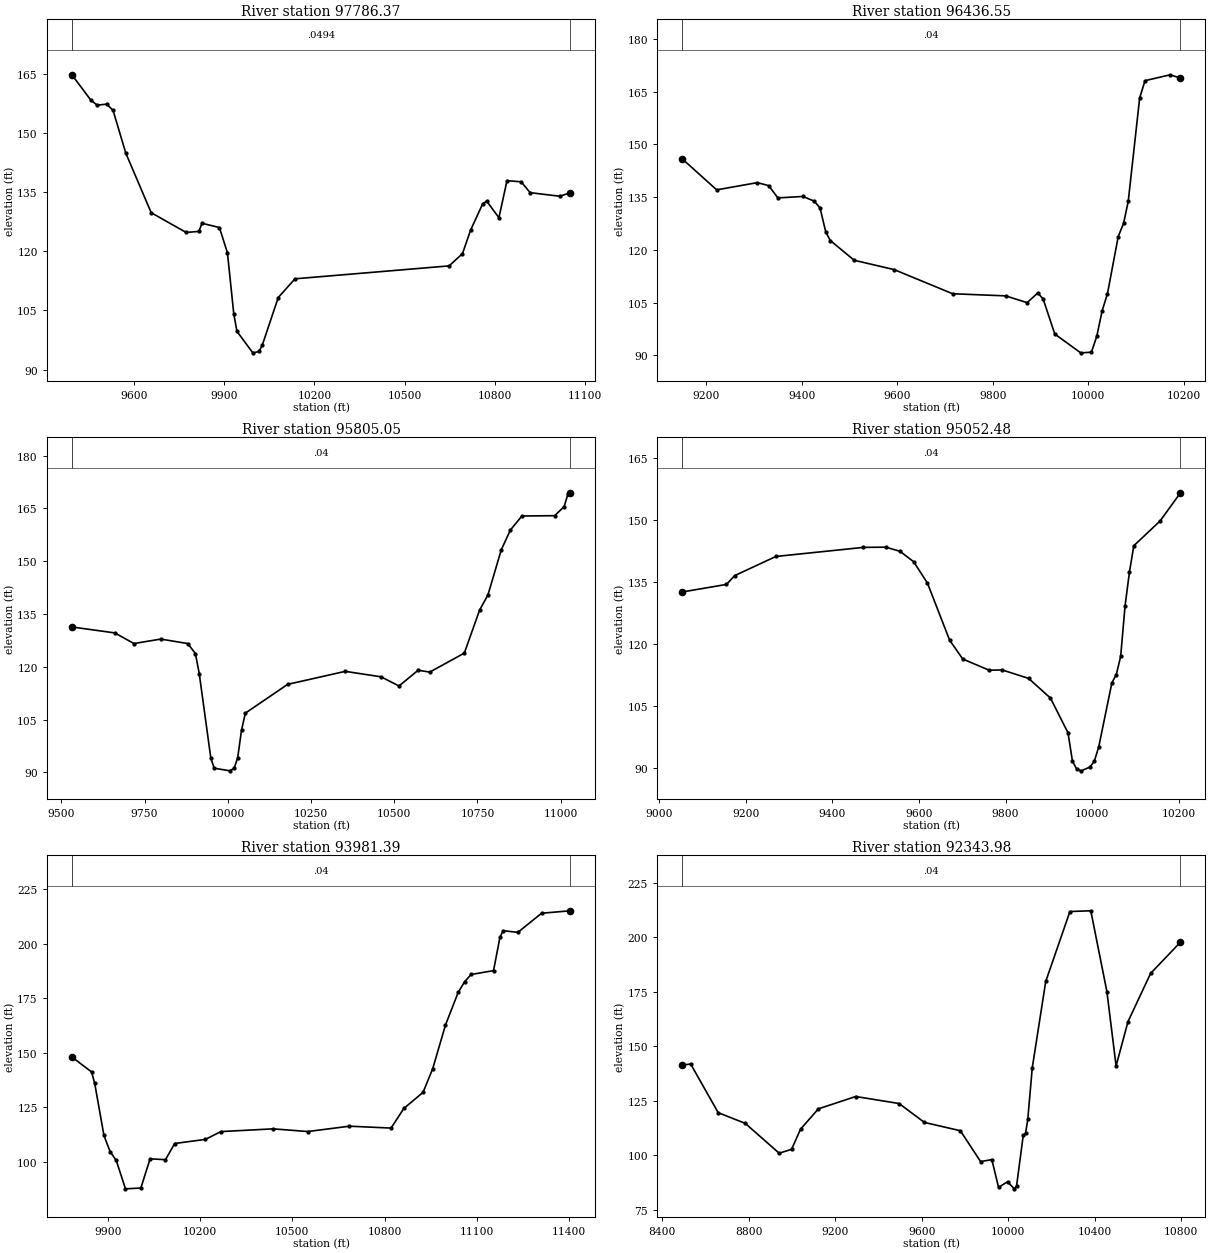
Type RM Length L Ch R = 1 ,97786.37,1349.821300,1349.821300,1349.821300
XS GIS Cut Line= 4
441425.311855912844548.870260298442251.700744808844826.648038074
442521.471820742845075.509474143442831.561855912 845354.42581585
#Sta/Elev= 30
9394.347164.75159457.317158.31829478.417157.04489510.066157.30919531.166155.7037
9573.365144.87849657.764129.76929773.812124.77119816.011  125.039826.561127.0959
9884.371126.00949910.959 119.6159932.059104.14299942.60999.677379995.358 94.2344
10016.4694.5771110027.01 96.243910079.76108.257910135.46113.007910647.39116.2866
10691.74119.382610718.64125.328910758.99132.052310772.44132.6878 10812.8 128.502
 10839.7137.894410886.64 137.61510916.55134.857611014.55133.949611050.27134.8285
#Mann= 3 , 0 , 0
9394.347  0.0494       09394.347  0.0494       011050.27  0.0494       0
#XS Ineff= 2 , 0
       0                               0
Bank Sta=9394.347,11050.27
Exp/Cntr=0.3,0.1

Type RM Length L Ch R = 1 ,96436.55,631.493200,631.493200,631.493200
XS GIS Cut Line= 3
441902.742411494845355.293871433442401.874355912845680.814704761
442801.179911494845884.807760298
#Sta/Elev= 30
9149.218145.91529221.904137.05059307.117139.10479330.994138.23839350.046134.7644
9402.626 135.1749426.504133.81739438.443131.87129450.381125.08819459.883122.6492
9510.075117.03359593.646114.38549716.167 107.5249827.233106.91919872.151104.9906
9894.609107.75369905.839106.00689930.16596.070649984.44490.72558 10006.990.90154
10018.0995.4110210029.36102.662110040.59107.577810063.05123.760410074.28127.5476
10084.03133.755210107.97163.1839 10119.2 168.08310171.95 169.75910193.51168.8076
#Mann= 3 , 0 , 0
9149.218    0.04       09149.218    0.04       010193.51    0.04       0
#XS Ineff= 2 , 0
       0                               0
Bank Sta=9149.218,10193.51
Exp/Cntr=0.3,0.1

Type RM Length L Ch R = 1 ,95805.05,752.576600,752.576600,752.576600
XS GIS Cut Line= 2
441733.471578121845771.960538089443031.214633733 846518.48831585
#Sta/Elev= 30
 9531.94131.30519660.605129.62599718.288126.60089798.747127.87049879.799126.5984
9902.872123.76479914.408118.04339949.01894.160669959.18691.19095 10006.790.44466
10019.3591.2202910029.7794.1385510041.31101.964610052.85106.834110179.79115.0045
 10352.8118.700810460.55 117.15110514.31114.543910571.99119.0278 10606.6118.4888
10710.43123.877310756.57136.142310781.43 140.40410821.54153.240810848.87158.8406
10883.48162.829410981.98162.916511010.38165.511311022.09 169.20211029.08169.4239
#Mann= 3 , 0 , 0
 9531.94    0.04       0 9531.94    0.04       011029.08    0.04       0
#XS Ineff= 2 , 0
       0                               0
Bank Sta=9531.94,11029.08
Exp/Cntr=0.3,0.1

Type RM Length L Ch R = 1 ,95052.48,1071.088200,1071.088200,1071.088200
XS GIS Cut Line= 3
441646.666022569845767.620260298441830.241953552846319.987858832
441917.710246712846881.412251905
#Sta/Elev= 30
9053.311132.58979155.927134.42759174.858136.55439269.981141.18489472.061143.3784
9523.641143.42839556.364142.43429587.977139.89689619.591134.76959670.819120.9624
9701.181116.39559761.905113.70189792.267113.75639852.991111.72089903.594106.9522
9944.07698.553469954.197 91.75269964.31889.746299974.43889.377559994.67990.29862
 10004.891.7160210014.9295.1670910045.28110.6641 10055.4112.626210065.52117.0221
10075.64129.198710085.77137.406810095.89143.779710156.61149.772210203.58156.5743
#Mann= 3 , 0 , 0
9053.311    0.04       09053.311    0.04       010203.58    0.04       0
#XS Ineff= 2 , 0
       0                               0
Bank Sta=9053.311,10203.58
Exp/Cntr=0.3,0.1

Type RM Length L Ch R = 1 ,93981.39,1637.410200,1637.410200,1637.410200
XS GIS Cut Line= 3
441047.707689255845910.849426985441056.388244808846609.634149224
441312.464633703847495.050815865
#Sta/Elev= 30
 9783.31148.08099847.466141.23219857.467135.98979887.469 112.166 9907.47104.7801
9927.472100.72699957.474 87.734610007.4888.1129310037.48101.487510087.48101.0736
10117.49108.491110217.49110.3826 10267.5113.943210437.51115.198410550.19113.9671
10685.52116.416510820.85115.548110862.49124.553210924.95131.924810956.18142.7165
10997.82162.754811039.46177.814911060.28182.5992 11081.1185.863911153.96187.6402
11174.78202.861411185.19205.930511233.01205.144711310.11213.909811403.85215.0338
#Mann= 3 , 0 , 0
 9783.31    0.04       0 9783.31    0.04       011403.85    0.04       0
#XS Ineff= 2 , 0
       0                               0
Bank Sta=9783.31,11403.85
Exp/Cntr=0.3,0.1

Type RM Length L Ch R = 1 ,92343.98,1865.294300,1865.294300,1865.294300
XS GIS Cut Line= 6
440826.353522569 845823.17581588440546.437476218846204.930237487
440509.979142874846342.951070815440575.083309531846652.846904144
440843.312476307847538.263570815440692.270809531847954.930237472
#Sta/Elev= 30
8491.379141.39698531.395141.92818658.891119.5663 8783.75114.68618940.754100.9746
8998.003102.76399039.375111.98299121.909121.33379294.769127.00049495.036123.7838
9612.467115.09769778.598111.28729872.04697.137059923.96298.039599955.112  85.321
9996.64487.8745110027.7984.6314710038.1885.8432410069.33109.271210079.71110.0267
10090.09116.464110110.86 140.12410173.16179.780310285.02211.8863 10381.5212.2238
10455.96175.1637 10498.5141.050810553.51161.362410658.05183.480810796.26197.8412
#Mann= 3 , 0 , 0
8491.379    0.04       08491.379    0.04       010796.26    0.04       0
#XS Ineff= 2 , 0
       0                               0
Bank Sta=8491.379,10796.26
Exp/Cntr=0.3,0.1

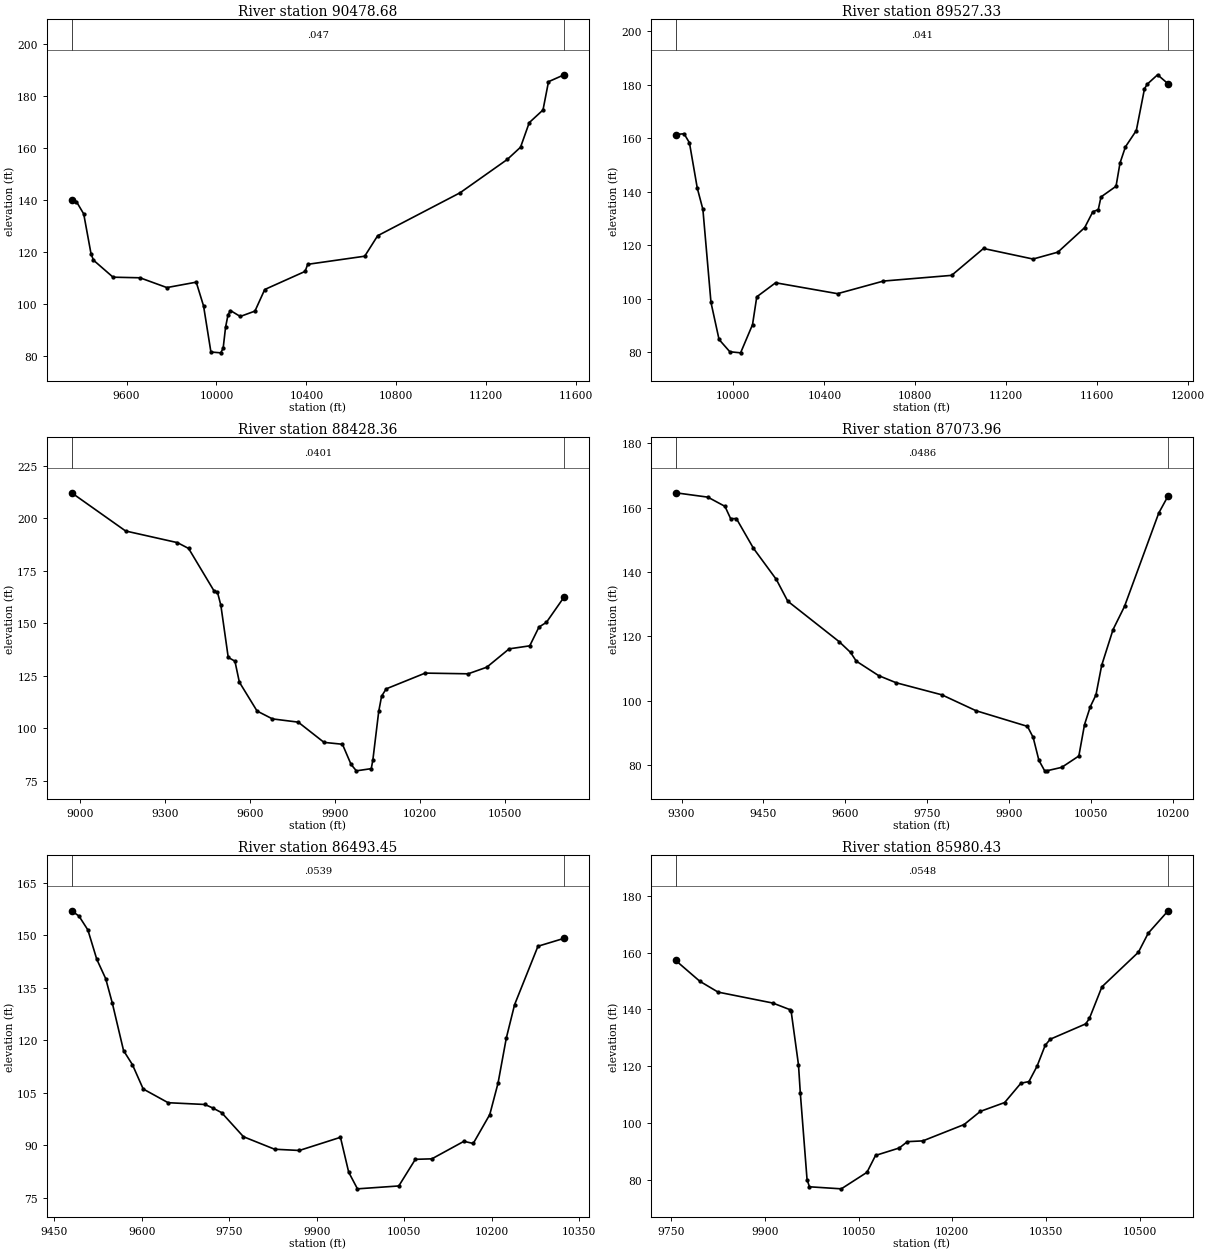
Type RM Length L Ch R = 1 ,90478.68,951.356500,951.356500,951.356500
XS GIS Cut Line= 4
440794.484351218845801.501418024439929.901017874  846173.0291958
439106.984351218846645.251418024438933.373240113846891.779195815
#Sta/Elev= 30
9355.401139.82459376.609 139.3589409.261134.61759441.914119.25219452.798 116.825
9539.872110.29529659.598110.06789779.324106.30759909.934108.38689942.58799.22198
 9975.2481.5505310018.7881.2319910029.66 82.972710040.54 91.133610051.4395.85036
10062.3197.4776410105.8595.2080210171.1697.2682810214.69105.564610394.32112.5184
10405.85115.2409 10659.5118.359410717.14 126.22211083.97142.732911293.83 155.531
11352.87160.233211391.67169.678611452.83174.543111477.29185.406311546.74188.0633
#Mann= 3 , 0 , 0
9355.401   0.047       09355.401   0.047       011546.74   0.047       0
#XS Ineff= 2 , 0
       0                 10427.5       0
Bank Sta=9355.401,11546.74
Exp/Cntr=0.3,0.1

Type RM Length L Ch R = 1 ,89527.33,1098.968300,1098.968300,1098.968300
XS GIS Cut Line= 5
440746.269274443845143.999057487440057.133753151845580.795876116
439888.234351218845864.001418024439690.317684531846020.251418039
439047.956573427846440.390306905
#Sta/Elev= 30
9746.038161.4565 9783.06161.76949806.739158.38899841.304141.40959865.936133.4802
9901.45598.718479936.97384.856549984.33280.2748710031.6979.8656710084.1390.40882
10102.81100.8098 10185.6106.053710457.91101.981410659.98106.697410959.51108.8236
11099.66118.873811317.49114.924911426.56117.497211544.52126.673311580.37132.6028
11604.27133.402611616.21138.134311682.33142.121411699.86150.817411723.76156.8747
11771.55162.9658 11807.4178.536411819.35180.274711865.02183.799511911.41180.4144
#Mann= 3 , 0 , 0
9746.038   0.041       09746.038   0.041       011911.41   0.041       0
#XS Ineff= 2 , 0
       0                11451.35       0
Bank Sta=9746.038,11911.41
Exp/Cntr=0.3,0.1

Type RM Length L Ch R = 1 ,88428.36,1354.401000,1354.401000,1354.401000
XS GIS Cut Line= 4
439948.922967017844666.231371418439874.642155737845175.513317794
439591.523904085845515.874057472438997.534078121846023.870260298
#Sta/Elev= 30
 8970.26212.01629161.026193.82159343.877188.28349383.354185.51419474.306165.0412
9484.931164.86079497.271 158.4369523.285133.6362 9546.92131.85519562.558121.8763
9625.107108.11079679.374104.36829770.426102.82139861.47793.192729926.514 92.2953
9957.07882.677289975.71179.6383710028.3480.6785210034.0184.8432510054.66107.9155
10064.78115.167410080.98118.664510218.64126.166110370.46125.833410436.25 128.978
 10515.2137.713410587.89139.151410620.47148.087710646.78150.328910709.24162.3927
#Mann= 3 , 0 , 0
 8970.26  0.0401       0 8970.26  0.0401       010709.24  0.0401       0
#XS Ineff= 2 , 0
       0                               0
Bank Sta=8970.26,10709.24
Exp/Cntr=0.3,0.1

Type RM Length L Ch R = 1 ,87073.96,580.512400,580.512400,580.512400
XS GIS Cut Line= 2
438903.784078121845058.592482522438639.895189255845921.439704746
#Sta/Elev= 30
9289.102164.63979348.088163.2836 9379.46 160.4249389.917156.57979400.375 156.632
9431.746147.36399473.575137.6968 9494.49130.93599588.605118.35869609.519115.0097
9619.976112.2976 9661.06 107.7879693.177 105.5639776.835101.81369839.57896.86159
9933.69392.00376 9944.1588.560819954.60781.469779965.06578.226459968.79278.17612
9996.43679.2616510027.8182.7887910038.2792.5818910048.7298.0858410059.18 101.787
10069.64110.973810090.55 122.12410111.47   129.310174.21158.3383 10191.4163.6807
#Mann= 3 , 0 , 0
9289.102  0.0486       09289.102  0.0486       0 10191.4  0.0486       0
#XS Ineff= 2 , 0
       0                               0
Bank Sta=9289.102,10191.4
Exp/Cntr=0.3,0.1

Type RM Length L Ch R = 1 ,86493.45,513.020400,513.020400,513.020400
XS GIS Cut Line= 3
438587.811855942845116.752204746438331.107237428845338.790724143
437973.228522569845694.877204761
#Sta/Elev= 30
9479.715157.02459492.322155.51789507.608 151.5499522.894 143.159 9538.18137.6262
9549.541130.62819568.752 117.0959584.038113.04719602.428106.12119645.183102.1994
9708.202101.69199721.424100.71499736.89999.356969774.31192.484579827.73988.91133
9870.05988.557459940.59392.31549  9954.782.347569969.70477.5972510040.5978.42209
10068.9586.02849 10097.386.1686310152.1991.1702610168.1990.5579710196.5598.81732
10210.73107.7987 10224.9120.676210239.08130.200510279.16146.894410323.97149.1565
#Mann= 3 , 0 , 0
9479.715  0.0539       09479.715  0.0539       010323.97  0.0539       0
#XS Ineff= 2 , 0
       0                               0
Bank Sta=9479.715,10323.97
Exp/Cntr=0.3,0.1

Type RM Length L Ch R = 1 ,85980.43,493.457600,493.457600,493.457600
XS GIS Cut Line= 3
438418.541022569844848.523038074 438171.38501519845080.110168576
437884.686855912845426.648038089
#Sta/Elev= 30
9757.035157.22689795.758149.88379825.009146.06719912.631142.22059940.039139.8974
9942.011139.27649953.743120.46249956.636110.59479967.44780.103599971.26177.56937
10022.2676.8476810063.3782.6567910077.0888.6044410115.0691.2199310128.0493.45207
10152.82  93.72110218.8999.4704710244.85104.101510283.78 107.21210309.74113.9969
10322.72 114.602 10335.7120.020510348.68127.351410356.75129.493610413.57134.8929
10419.51136.824710439.53147.931710497.94160.108710513.63 166.802 10545.5 174.686
#Mann= 3 , 0 , 0
9757.035  0.0548       09757.035  0.0548       0 10545.5  0.0548       0
#XS Ineff= 2 , 0
       0                               0
Bank Sta=9757.035,10545.5
Exp/Cntr=0.3,0.1

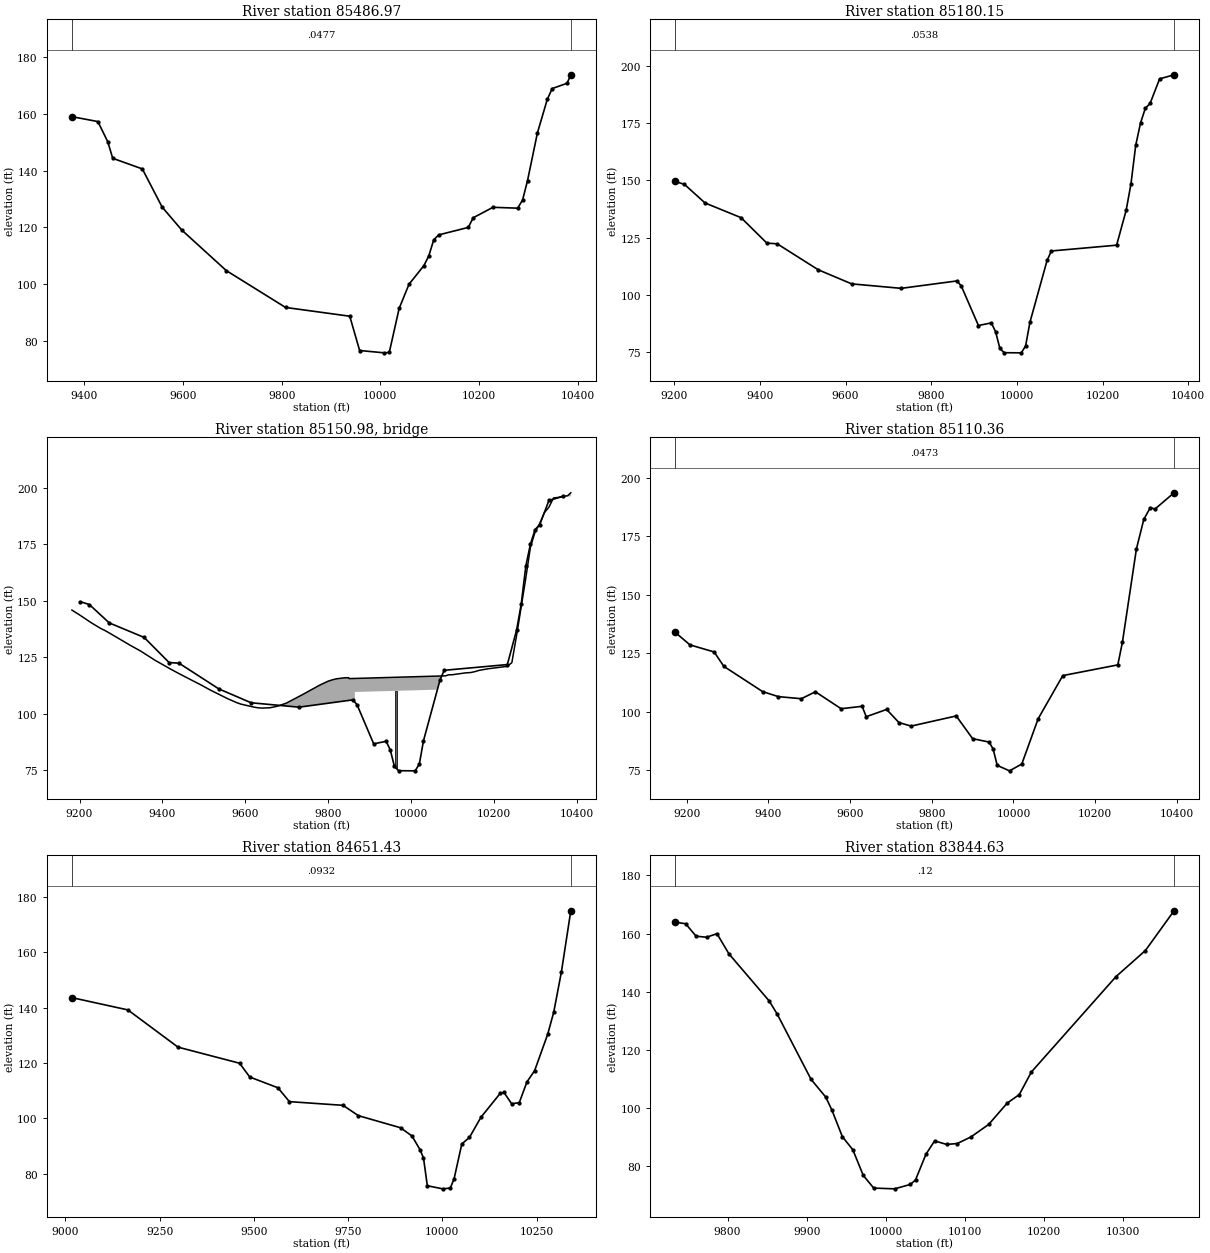
Type RM Length L Ch R = 1 ,85486.97,306.823200,306.823200,306.823200
XS GIS Cut Line= 2
437762.291022579844382.377204761  437788.5725152845392.610168576
#Sta/Elev= 30
9375.203158.92979427.844157.1973 9447.85150.08669457.854144.29659517.874140.5636
9557.888127.17669597.901119.05869687.932104.85439807.97291.909699938.01688.82987
9958.02376.7860510008.0475.9653210018.0476.0934310038.0591.5535410058.06100.0715
10088.07106.564310098.07109.989210108.07115.643110118.08 117.388 10178.1120.0211
 10188.1123.406310228.11127.086310278.13126.781310288.13129.645710298.14 136.476
10318.14153.200810338.15165.007710348.15168.799110378.17170.642510385.78173.6355
#Mann= 3 , 0 , 0
9375.203  0.0477       09375.203  0.0477       010385.78  0.0477       0
#XS Ineff= 2 , 0
       09809.847                       0
Bank Sta=9375.203,10385.78
Exp/Cntr=0.3,0.1

Type RM Length L Ch R = 1 ,85180.15,69.783600,69.783600,69.783600
XS GIS Cut Line= 5
437661.402376303844307.106696355 437476.50654297844583.148363022
437451.766959636844671.690029688437481.714876303845158.669196355
 437593.69404297845385.231696355
#Sta/Elev= 30
9202.089149.54359223.625148.29889271.769140.16619356.021133.74439416.201122.6498
9440.273122.34499536.254110.99659614.251104.8605 9729.77102.91199860.015  106.15
9870.034103.9527 9910.1186.693749940.16787.838689950.18583.995459960.20476.70439
9970.22374.82469 10010.374.7668110020.3277.8119910030.3488.0796210070.41115.0768
10080.43119.217310232.77121.748610255.08136.990210266.24148.444710277.39  165.34
10288.55175.0351 10299.7181.425410310.86183.581610333.17194.313810366.89196.1055
#Mann= 3 , 0 , 0
9202.089  0.0538       09202.089  0.0538       010366.89  0.0538       0
#XS Ineff= 2 , 0
       09610.588        10077.54       0
Bank Sta=9202.089,10366.89
Exp/Cntr=0.3,0.1

Type RM Length L Ch R = 3 ,85150.98,,,
BEGIN DESCRIPTION:
END DESCRIPTION:
Bridge Culvert--1,0,-1,-1, 0
Deck Dist Width WeirC Skew NumUp NumDn MinLoCord MaxHiCord MaxSubmerge Is_Ogee
21.276350,27.230900,2.6,0, 60, 60, , , 0.95, 0, 0,0,,
 9181.63 9202.60 9226.67 9238.70 9250.74 9260.43 9274.81 9322.95 9347.02 9383.12
 9419.23 9443.30 9494.06 9515.51 9558.29 9578.74 9588.97 9619.27 9629.27 9639.27
 9659.27 9669.27 9679.28 9699.28 9739.40 9779.53 9799.60 9809.63 9819.66 9839.73
 9849.76 9850.82 9864.75 9864.7510063.5710063.5710083.5710090.5410100.5810131.52
10144.4910153.9410165.1610187.5910232.4410243.6510254.8710266.0810277.0910288.51
10299.7210310.9410322.1510333.3610343.3910344.5810355.7910367.0010378.2210385.94
  145.84  143.40  140.43  139.08  137.75  136.90  135.41  130.21  127.78  123.56
  119.81  117.44  112.66  110.50  106.61  104.97  104.29  103.01  102.68  102.51
  102.65  103.00  103.42  104.71  108.58  112.64  114.37  114.97  115.44  115.91
  115.95  115.55  115.62  115.62  116.66  116.66  116.76  117.20  117.27  118.07
  118.23  118.61  119.21  119.92  120.97  122.61  134.44  147.13  159.75  173.69
  180.35  184.09  188.88  191.42  195.12  195.42  195.64  196.13  196.37  197.70
 -854.16 -856.60 -859.57 -860.92 -862.25 -863.10 -864.59 -869.79 -872.22 -876.44
 -880.19 -882.56 -887.34 -889.50 -893.39 -895.03 -895.71 -896.99 -897.32 -897.49
 -897.35 -897.00 -896.58 -895.29 -891.42 -887.36 -885.63 -885.03 -884.56 -884.09
 -884.05 -884.45 -884.38  109.62  110.66 -883.34 -883.24 -882.80 -882.73 -881.93
 -881.77 -881.39 -880.79 -880.08 -879.03 -877.39 -865.56 -852.87 -840.25 -826.31
 -819.65 -815.91 -811.12 -808.58 -804.88 -804.58 -804.36 -803.87 -803.63 -802.30
 9181.63 9202.60 9226.67 9238.70 9250.74 9260.43 9274.81 9322.95 9347.02 9383.12
 9419.23 9443.30 9494.06 9515.51 9558.29 9578.74 9588.97 9619.27 9629.27 9639.27
 9659.27 9669.27 9679.28 9699.28 9739.40 9779.53 9799.60 9809.63 9819.66 9839.73
 9849.76 9850.82 9880.21 9880.2110079.0310079.0310083.5710090.5410100.5810131.52
10144.4910153.9410165.1610187.5910232.4410243.6510254.8710266.0810277.0910288.51
10299.7210310.9410322.1510333.3610343.3910344.5810355.7910367.0010378.2210385.94
  145.84  143.40  140.43  139.08  137.75  136.90  135.41  130.21  127.78  123.56
  119.81  117.44  112.66  110.50  106.61  104.97  104.29  103.01  102.68  102.51
  102.65  103.00  103.42  104.71  108.58  112.64  114.37  114.97  115.44  115.91
  115.95  115.55  115.70  115.70  116.74  116.74  116.76  117.20  117.27  118.07
  118.23  118.61  119.21  119.92  120.97  122.61  134.44  147.13  159.75  173.69
  180.35  184.09  188.88  191.42  195.12  195.42  195.64  196.13  196.37  197.70
 -854.16 -856.60 -859.57 -860.92 -862.25 -863.10 -864.59 -869.79 -872.22 -876.44
 -880.19 -882.56 -887.34 -889.50 -893.39 -895.03 -895.71 -896.99 -897.32 -897.49
 -897.35 -897.00 -896.58 -895.29 -891.42 -887.36 -885.63 -885.03 -884.56 -884.09
 -884.05 -884.45 -884.30  109.70  110.74 -883.26 -883.24 -882.80 -882.73 -881.93
 -881.77 -881.39 -880.79 -880.08 -879.03 -877.39 -865.56 -852.87 -840.25 -826.31
 -819.65 -815.91 -811.12 -808.58 -804.88 -804.58 -804.36 -803.87 -803.63 -802.30
Pier Skew, UpSta & Num, DnSta & Num=  ,9964.16, 2 ,9979.62, 2 , 0 , 0 , 0 ,,
    4.00    4.00
 -883.86  116.14
    4.00    4.00
 -883.78  116.22
BR Coef=-1 , 0 , 0 ,, 0 ,,,0.8,0,1,0,
WSPro=,,,, 1 ,,,, 0 ,,,, 0 ,,,,-1 ,-1 ,-1 , 0 , 0 , 0 , 0 , 0
BC Design=,, 0 ,, 0 ,,,,,,

Type RM Length L Ch R = 1 ,85110.36,458.934500,458.934500,458.934500
XS GIS Cut Line= 6
437591.089876303844274.554613022437411.402376303844555.804613022
437380.152376303844652.158779688437384.058626303844805.804613022
437416.610709636845178.200446355437540.308626303845406.065029688
#Sta/Elev= 30
9171.594133.91239207.723128.55179267.056125.52039290.789119.37689385.723108.5992
9424.366106.44769480.656105.56049515.011108.52039578.088101.28479629.488102.3207
9639.49197.871659689.507100.98159719.51795.378999749.52793.867579859.90998.20382
9900.061 88.50639940.21487.050319950.25284.13218 9960.29 77.09249990.40474.76099
10020.5277.6715810060.6797.03338 10120.9115.433910255.67120.004310267.05129.7769
10301.19169.467910319.42182.195910335.32187.1682 10346.7186.542910393.43193.4986
#Mann= 3 , 0 , 0
9171.594  0.0473       09171.594  0.0473       010393.43  0.0473       0
#XS Ineff= 2 , 0
       09622.681         10095.7       0
Bank Sta=9171.594,10393.43
Exp/Cntr=0.3,0.1

Type RM Length L Ch R = 1 ,84651.43,806.799000,806.799000,806.799000
XS GIS Cut Line= 3
436838.419494808844309.981371433436921.752828151844698.002204746
437085.815328151845609.460538089
#Sta/Elev= 30
9017.579 143.5629165.905139.14219298.869125.71119462.201119.90689489.226114.9318
9563.808111.0604 9594.29106.0577 9736.54104.72419777.183101.00259888.95196.64219
9919.43393.663719940.81388.704419949.91585.758829960.07675.7349110000.7274.60927
10021.0474.87811 10031.278.3146110051.5290.7964710071.8493.1551310102.33100.4328
10153.13108.999410163.29109.365410183.61105.310910203.93105.679510224.25113.1797
10244.58117.2146 10279.5130.443410295.38138.3769 10315.7152.867910340.55 174.887
#Mann= 3 , 0 , 0
9017.579  0.0932       09017.579  0.0932       010340.55  0.0932       0
#XS Ineff= 2 , 0
       09560.644        10151.86       0
Bank Sta=9017.579,10340.55
Exp/Cntr=0.3,0.1

Type RM Length L Ch R = 1 ,83844.63,749.123600,749.123600,749.123600
XS GIS Cut Line= 2
436090.589633733845174.998732537436502.916022599845652.429288074
#Sta/Elev= 30
9733.685163.9181  9746.9163.35579760.113159.08059773.326158.71749786.539159.9356
 9801.63153.00939852.605136.79329862.828132.21929905.457109.84719924.026103.7441
9931.88499.261749945.09790.09329 9958.31 85.63429971.52376.780369984.73672.43337
10011.1672.1725510031.12 73.692410037.5975.23432 10050.884.0725410061.7288.67042
10077.0287.4414510090.4487.7673610107.6290.0166110130.0894.3176610153.52101.6646
10168.82 104.59210184.12112.369510291.21145.203810328.28154.148510364.52167.8192
#Mann= 3 , 0 , 0
9733.685    0.12       09733.685    0.12       010364.52    0.12       0
#XS Ineff= 2 , 0
       0                               0
Bank Sta=9733.685,10364.52
Exp/Cntr=0.3,0.1

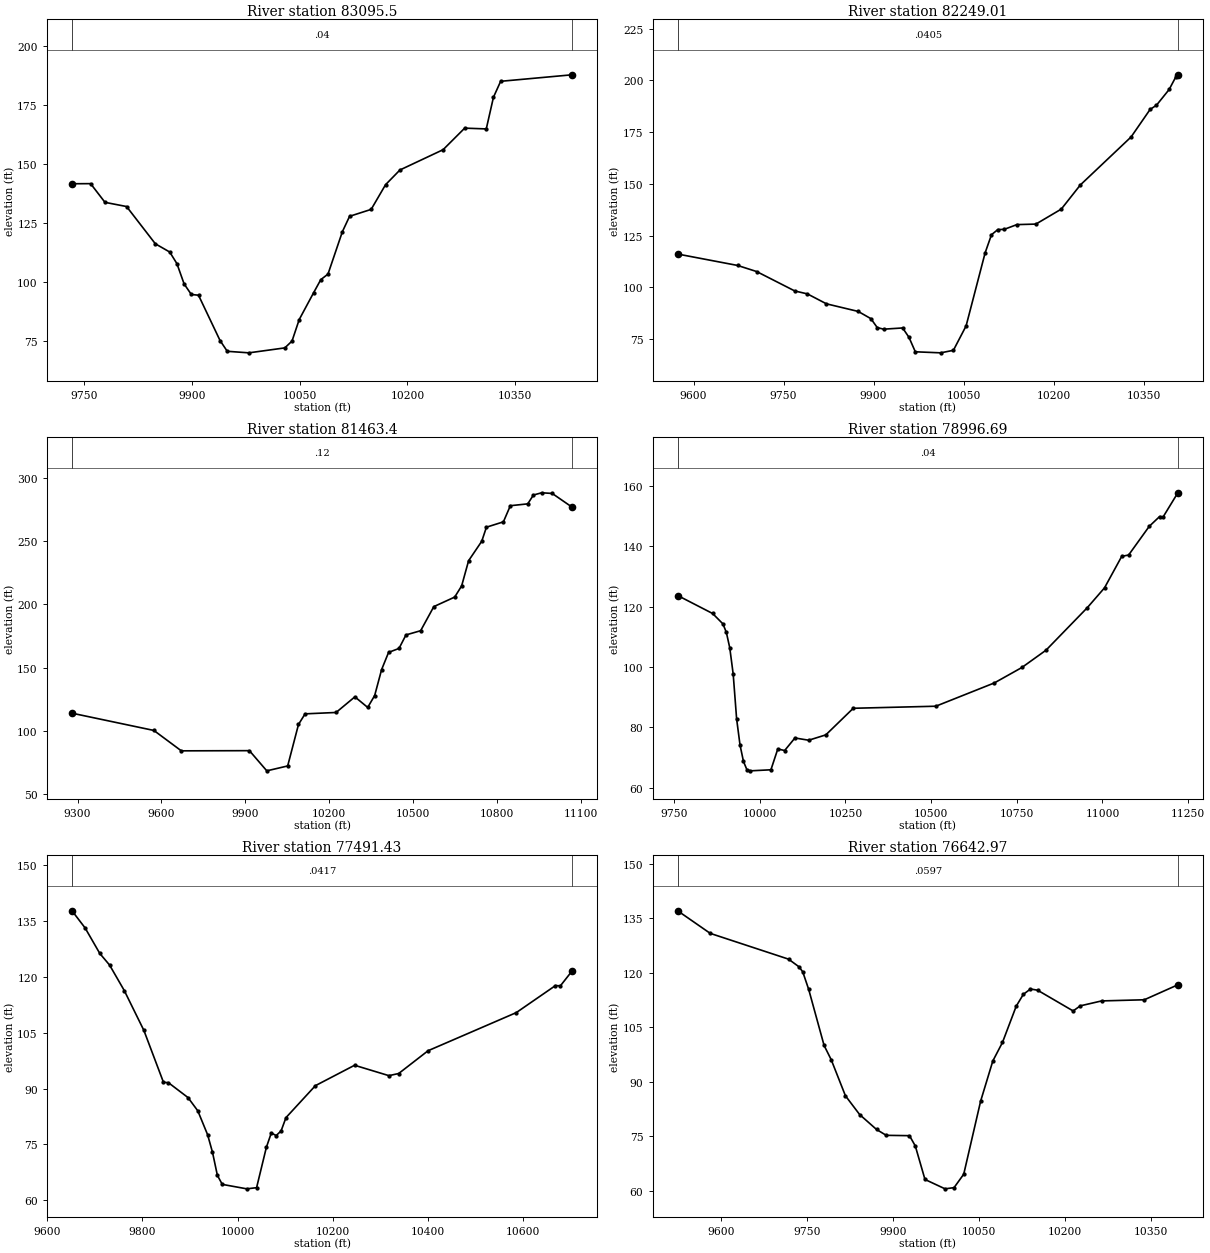
Type RM Length L Ch R = 1 , 83095.5,846.491000,846.491000,846.491000
XS GIS Cut Line= 2
 435679.13130036846056.509149194 436374.44380036846012.238315865
#Sta/Elev= 30
9732.912141.72359758.833141.76659778.874133.85519808.935 132.0859849.016116.3253
9869.056112.83559879.076107.91969889.09799.344799899.11794.888789909.13794.56902
9939.19875.365049949.21870.844029979.279 70.195110029.3872.28782 10039.475.18651
10049.4284.2840110069.46 95.621110079.48101.1636 10089.5103.508410109.54121.4475
10119.56127.947510149.62130.876810169.66141.3164 10189.7147.545510249.83156.1291
10279.89165.246410309.95164.916910319.97178.320510329.99185.058310429.63187.8188
#Mann= 3 , 0 , 0
9732.912    0.04       09732.912    0.04       010429.63    0.04       0
#XS Ineff= 2 , 0
       0                               0
Bank Sta=9732.912,10429.63
Exp/Cntr=0.3,0.1

Type RM Length L Ch R = 1 ,82249.01,785.612400,785.612400,785.612400
XS GIS Cut Line= 2
436070.494147569846831.422343656436858.688592017846560.589010298
#Sta/Elev= 30
9573.594116.06749673.523110.54579705.245107.59899768.68898.224979789.83696.79076
9821.55891.989699874.42788.316449895.57584.821349906.149 80.51379916.72379.73681
9948.444 80.32819959.01875.797649969.59268.8021510011.8968.2970310033.0469.52249
10054.1881.29846 10085.9116.642510096.48125.399110107.05 127.89610117.63127.9908
10138.77130.2944 10170.5130.546310212.79137.793310244.51149.4515 10329.1172.6768
10360.83185.9995 10371.4188.021610392.55195.640910403.12201.449610407.02202.7408
#Mann= 3 , 0 , 0
9573.594  0.0405       09573.594  0.0405       010407.02  0.0405       0
#XS Ineff= 2 , 0
       0                               0
Bank Sta=9573.594,10407.02
Exp/Cntr=0.3,0.1

Type RM Length L Ch R = 1 , 81463.4,2466.713500,2466.713500,2466.713500
XS GIS Cut Line= 4
436108.688592046847001.561232522436369.105258793847169.095954761
 436512.33442536847304.512621433437542.716369808848067.533454731
#Sta/Elev= 30
9280.084113.92869572.965100.2965 9671.1184.193129914.59784.337199976.81468.40027
10051.4772.2592510090.13105.022110113.69113.402910224.56 114.49510291.77126.8299
10337.67118.476410362.56127.853210387.45148.377210412.33161.938510449.66165.0708
10474.55175.737210527.02179.0578 10574.1198.082310648.76205.618210673.64214.4474
10698.53234.349910745.47249.680110762.27 260.80610822.96265.034610847.85277.7794
10910.07279.2384 10930.3286.206810959.84287.987710997.52287.469111068.99276.5732
#Mann= 3 , 0 , 0
9280.084    0.12       09280.084    0.12       011068.99    0.12       0
#XS Ineff= 2 , 0
       0                               0
Bank Sta=9280.084,11068.99
Exp/Cntr=0.3,0.1

Type RM Length L Ch R = 1 ,78996.69,1505.263000,1505.263000,1505.263000
XS GIS Cut Line= 3
435869.973314255847103.123732522435890.806647599847689.929288074
435970.667758703848557.984843642
#Sta/Elev= 30
9760.926123.68519862.866117.71939892.885114.28469902.892111.48459912.898106.3472
9922.90497.630659932.91182.752229942.91774.054859952.92368.645659962.92965.90979
9972.93665.5405610032.9765.8913710052.9972.79772   1007372.2788910103.0276.44016
10143.0475.6934310193.0777.4661610273.1286.2889210513.8786.9684610684.5994.69238
10764.9299.8100610835.22105.539910955.73119.648411005.94126.226611056.15136.6699
11076.23137.108911136.49146.640111166.61149.866411176.66149.708611219.82157.7509
#Mann= 3 , 0 , 0
9760.926    0.04       09760.926    0.04       011219.82    0.04       0
#XS Ineff= 2 , 0
       0                               0
Bank Sta=9760.926,11219.82
Exp/Cntr=0.3,0.1

Type RM Length L Ch R = 1 ,77491.43,848.455800,848.455800,848.455800
XS GIS Cut Line= 2
 434660.77192539847648.262621418434917.716369838848669.095954746
#Sta/Elev= 30
9651.616137.75919679.187133.15289710.123126.29839730.746123.17439761.682116.3212
 9802.93105.62049844.17791.669939854.489 91.58639895.73787.586559916.36184.02846
9936.98477.614179947.29672.896039957.60866.67548 9967.9264.2601510019.4863.06456
 10040.163.3750910060.7374.2315710071.0478.0627510081.3577.3800610091.6678.62038
10101.9782.1988110163.85 90.779410246.3496.2617610318.5293.4694910339.1594.04489
10401.02100.166510586.63110.403810669.13117.668210679.44117.592410704.29121.6246
#Mann= 3 , 0 , 0
9651.616  0.0417       09651.616  0.0417       010704.29  0.0417       0
#XS Ineff= 2 , 0
       09848.034        10405.03       0
Bank Sta=9651.616,10704.29
Exp/Cntr=0.3,0.1

Type RM Length L Ch R = 1 ,76642.97,939.458600,939.458600,939.458600
XS GIS Cut Line= 2
434300.236425757847709.203147396433784.035814315848412.151510298
#Sta/Elev= 30
9524.671137.0405 9581.49130.82779717.963123.74559736.259121.63519742.776120.2555
9753.154115.41719779.996100.01349792.403 96.09169817.21686.169429842.02981.00251
9871.41976.913589888.31475.299429928.87675.205469938.99972.383059955.89463.16461
9990.90960.5872910006.5860.9167710023.4764.6173810052.9484.7118110074.1695.73887
10091.05100.859210114.98110.808410127.38114.061810139.79115.5334 10152.2115.2043
10214.23109.500210226.64110.898310263.86112.2548 10338.3112.571210396.79116.6856
#Mann= 3 , 0 , 0
9524.671  0.0597       09524.671  0.0597       010396.79  0.0597       0
#XS Ineff= 2 , 0
       09753.316                       0
Bank Sta=9524.671,10396.79
Exp/Cntr=0.3,0.1