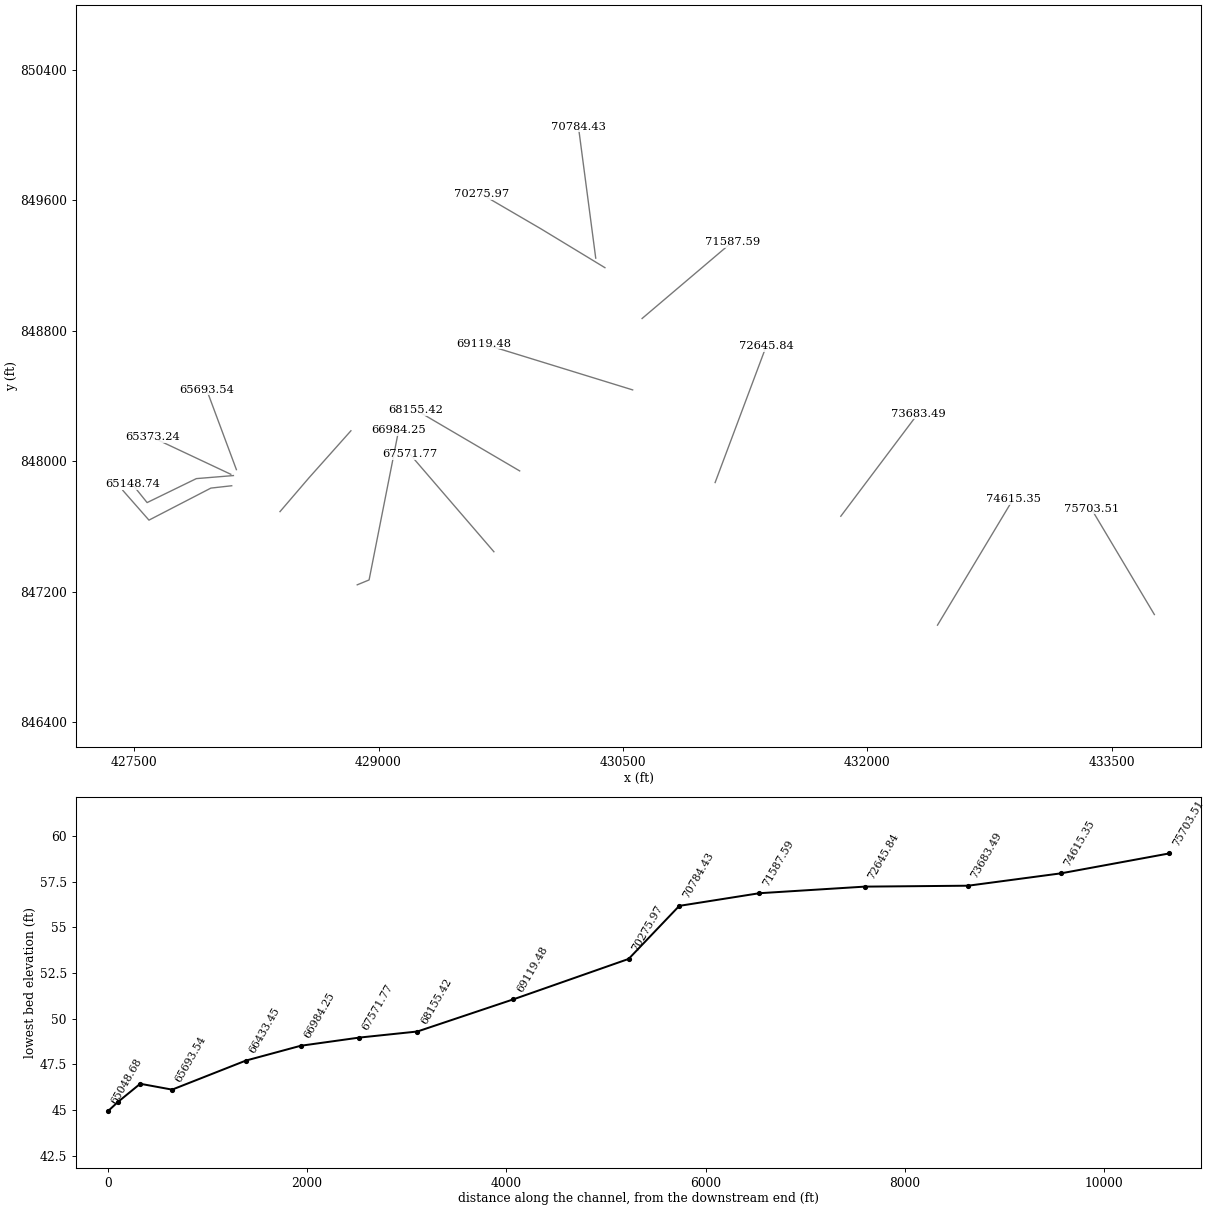
HEC-RAS study 7132_ras.prj: 7132

--- 7132_ras.g01 (geometry) --- (continued)

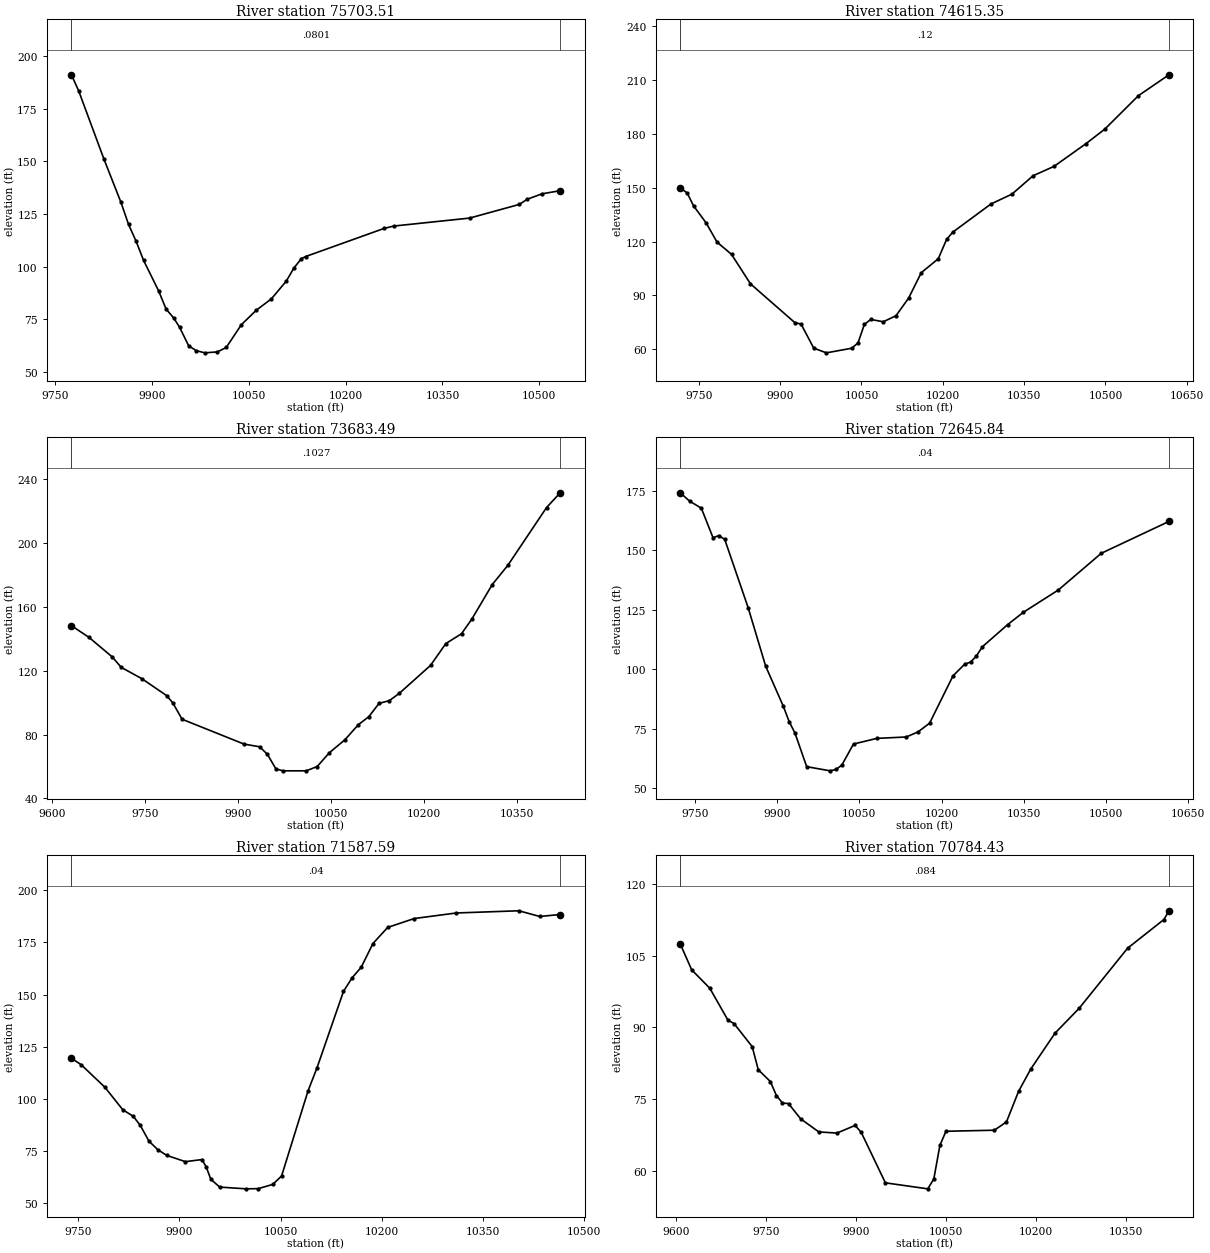
Type RM Length L Ch R = 1 ,75703.51,1088.163200,1088.163200,1088.163200
XS GIS Cut Line= 2
 433760.77192536847059.026510313433373.153092414847709.203147396
#Sta/Elev= 30
9775.296191.06349786.567183.39649825.624151.06429852.104130.43189863.746120.0371
9875.389112.10039887.031102.97229910.31588.496769921.95879.81579  9933.675.65999
9942.794 71.21519956.88462.412639968.52760.09764 9981.8559.0596610001.3859.49827
 10015.161.6135510038.3872.3660710061.6679.3163410084.9584.6690610108.2393.16476
10119.8899.3359610131.52103.800310138.08104.779610259.58118.133310274.77119.2555
10391.94123.031310469.14129.529510480.79131.915210504.07134.544910532.25136.0359
#Mann= 3 , 0 , 0
9775.296  0.0801       09775.296  0.0801       010532.25  0.0801       0
#XS Ineff= 2 , 0
       0                               0
Bank Sta=9775.296,10532.25
Exp/Cntr=0.3,0.1

Type RM Length L Ch R = 1 ,74615.35,931.858000,931.858000,931.858000
XS GIS Cut Line= 2
432430.042758703846993.922343642432893.986425728847766.494814068
#Sta/Elev= 30
9715.861149.94899728.783147.00059740.448139.87189763.777130.30169783.763  119.66
9810.435112.84989845.42996.411739927.08174.833599938.74573.972129962.07460.57898
9985.40357.9671610032.0660.5286710043.7363.5189610055.3973.7816210067.0676.56068
10090.3875.2912610113.71 78.640210137.0488.4820110160.37102.638410191.67110.3743
10207.03121.185110218.69125.271910288.79 140.89610327.64146.412210366.49 156.633
10405.33161.897910463.61174.426910498.64182.582810560.73201.254510617.03212.8931
#Mann= 3 , 0 , 0
9715.861    0.12       09715.861    0.12       010617.03    0.12       0
#XS Ineff= 2 , 0
       0                               0
Bank Sta=9715.861,10617.03
Exp/Cntr=0.3,0.1

Type RM Length L Ch R = 1 ,73683.49,1037.654000,1037.654000,1037.654000
XS GIS Cut Line= 2
431836.694759041847662.328147396432310.653092414848292.536480725
#Sta/Elev= 30
9631.627148.18869659.995140.85729697.532128.61359711.994122.09139745.269114.9961
9785.119104.43969795.18199.881279810.144 89.59989910.24374.020399935.26872.35736
 9947.7867.665169961.55558.506869972.80557.2938310010.3457.28995 10028.159.99322
10047.8868.65457 10072.976.7552610094.6586.2371210111.2991.1291410127.9399.52528
10144.57101.253610160.49105.770610211.12123.353510235.57136.953610261.03143.1492
10277.66152.320410310.64173.968810335.66185.937510398.23222.172410420.17231.4106
#Mann= 3 , 0 , 0
9631.627  0.1027       09631.627  0.1027       010420.17  0.1027       0
#XS Ineff= 2 , 0
       0                               0
Bank Sta=9631.627,10420.17
Exp/Cntr=0.3,0.1

Type RM Length L Ch R = 1 ,72645.84,1058.249900,1058.249900,1058.249900
XS GIS Cut Line= 2
 431065.45942542847868.922343656431378.361425728848703.994814068
#Sta/Elev= 30
9723.087174.16759740.257170.64099761.615167.70559782.972155.26589793.651156.1752
 9804.33154.55329847.046125.85859879.083101.2177 9911.1284.457759921.79977.97739
9932.47873.118129953.83659.000819996.55157.2396910007.2357.8060710017.9159.64064
10039.2768.5212210081.9870.8865810135.3871.4777610156.74 73.571610178.0977.26884
10220.8197.1706910242.17102.112210252.85102.957310263.53105.5296 10274.2109.3731
10320.28118.682110348.78123.844510413.03133.285310491.28148.711710614.86162.1195
#Mann= 3 , 0 , 0
9723.087    0.04       09723.087    0.04       010614.86    0.04       0
#XS Ineff= 2 , 0
       0                               0
Bank Sta=9723.087,10614.86
Exp/Cntr=0.3,0.1

Type RM Length L Ch R = 1 ,71587.59,803.152600,803.152600,803.152600
XS GIS Cut Line= 2
430617.348556846848875.683085248431170.028092414849344.619814053
#Sta/Elev= 30
9739.716119.48549754.116116.39989789.094105.66769815.94394.775759831.39991.66058
9841.552 87.45789854.66779.765129867.78175.657969880.89672.946649908.68269.91521
9933.35470.906279939.59567.379519946.468 61.47129959.58357.720859998.92756.87807
10016.8856.9765410038.2758.9976810051.3863.0338910090.73103.931310103.84 114.816
10143.19151.533610155.99158.056310169.42 163.072 10186.9174.492510208.76182.2093
 10248.1186.464110310.55 189.12910403.29190.1822 10434.2 187.45510464.53188.3931
#Mann= 3 , 0 , 0
9739.716    0.04       09739.716    0.04       010464.53    0.04       0
#XS Ineff= 2 , 0
       0                               0
Bank Sta=9739.716,10464.53
Exp/Cntr=0.3,0.1

Type RM Length L Ch R = 1 ,70784.43,508.458400,508.458400,508.458400
XS GIS Cut Line= 2
430332.820536464849246.092482537430226.483730942850053.384149194
#Sta/Elev= 30
9607.231107.50229626.302102.06339656.56198.19701 9686.8291.500719696.90790.80707
9727.166 85.96989737.25281.134439757.425 78.65739767.51175.727249777.59874.16803
9787.68474.035229807.857  70.8559838.11668.104749868.37567.867379898.63469.46694
9908.72168.031129949.06657.4422110019.6756.1850410029.7658.2638810039.8465.26951
10049.9368.2418510130.6268.4654610150.79 70.205310170.9776.6058710191.14 81.2491
10231.4888.7636710271.83 93.992210352.52106.580310413.04112.5871 10421.5114.4251
#Mann= 3 , 0 , 0
9607.231   0.084       09607.231   0.084       0 10421.5   0.084       0
#XS Ineff= 2 , 0
       0                10212.75       0
Bank Sta=9607.231,10421.5
Exp/Cntr=0.3,0.1

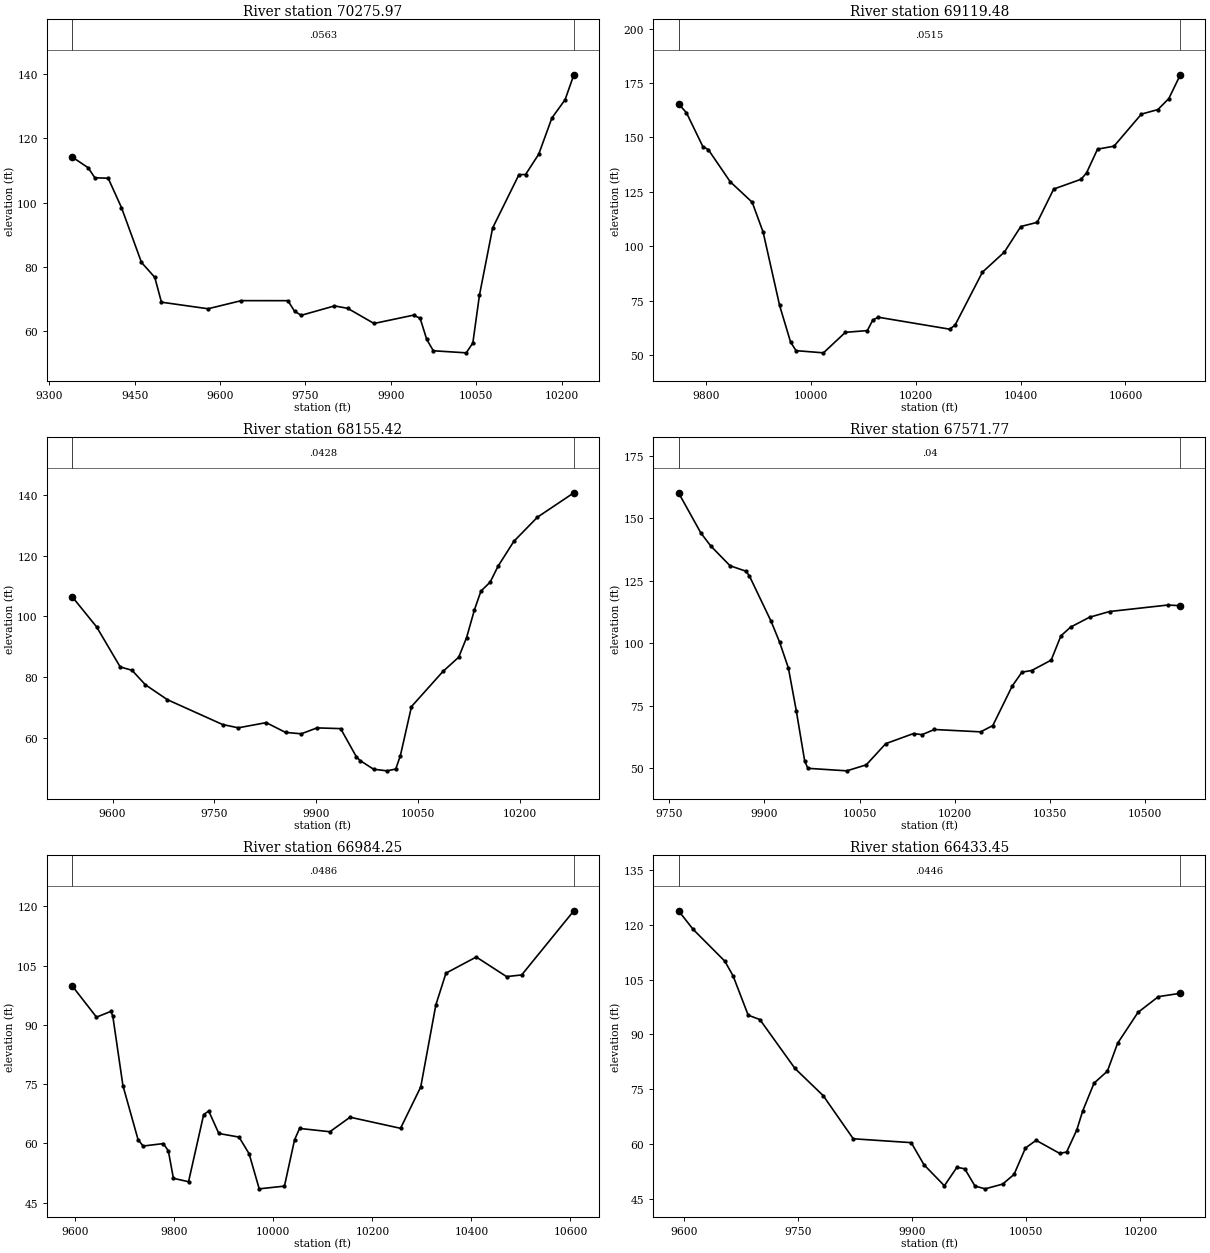
Type RM Length L Ch R = 1 ,70275.97,1156.493800,1156.493800,1156.493800
XS GIS Cut Line= 3
430389.244147569849187.498732522429996.254806846849426.030307487
429631.671473533849638.703918591
#Sta/Elev= 30
9339.886114.21899368.246110.85219379.944107.7288 9403.34107.61049426.736 98.4621
9461.82981.413259485.22576.766569496.92369.035749578.80866.992539637.29869.51384
9719.18369.505979730.88166.218519742.57964.954699801.05367.877549824.20767.12294
9870.51662.412219939.97865.006149951.55564.010779963.13257.446919974.70953.92082
10032.5953.2780410044.1756.3567110055.7571.19261 10078.992.0968910125.21108.7196
10136.79 108.74510159.94 115.075 10183.1126.343910206.25132.022210221.68139.7788
#Mann= 3 , 0 , 0
9339.886  0.0563       09339.886  0.0563       010221.68  0.0563       0
#XS Ineff= 2 , 0
       0                               0
Bank Sta=9339.886,10221.68
Exp/Cntr=0.3,0.1

Type RM Length L Ch R = 1 ,69119.48,964.055800,964.055800,964.055800
XS GIS Cut Line= 2
430559.383036524848437.498732522429643.986425757848719.619814068
#Sta/Elev= 30
9746.885165.44019761.936161.35969793.328 145.7899803.792144.38199845.649129.6139
9887.506120.22929908.434106.44479939.82672.834239960.75555.998249971.21952.06644
10023.54 51.0645 10065.4 60.492210107.2561.2781310117.7266.1215410128.1867.42111
10264.2261.9439310274.6863.74795   1032788.1220810368.8697.3245710400.25109.0773
10431.64111.001510463.03126.284610515.35130.786810525.82133.747410546.75144.6215
10578.14145.970110630.46160.707310661.85162.783210682.78167.837610704.77178.7733
#Mann= 3 , 0 , 0
9746.885  0.0515       09746.885  0.0515       010704.77  0.0515       0
#XS Ineff= 2 , 0
       0                               0
Bank Sta=9746.885,10704.77
Exp/Cntr=0.3,0.1

Type RM Length L Ch R = 1 ,68155.42,583.654900,583.654900,583.654900
XS GIS Cut Line= 2
429866.133279085847940.353224143 429228.74067539848314.234843642
#Sta/Elev= 30
9540.422106.53699576.51696.599279611.29683.438849628.66482.332499648.42877.57045
9680.85772.669299762.01164.521949785.198 63.43349826.30865.135179854.758 61.9263
9877.945 61.46869901.13263.408379935.91263.173069959.09953.921369964.65952.67233
9984.42449.8308210004.1949.3010410017.0749.8887310023.9554.3381310040.2570.41102
10086.6381.9575310109.8186.6338410121.4193.06509   10133102.222610142.54 108.343
10156.19111.311810167.78116.541210190.97124.680810225.75132.624910279.38140.6409
#Mann= 3 , 0 , 0
9540.422  0.0428       09540.422  0.0428       010279.38  0.0428       0
#XS Ineff= 2 , 0
       0                               0
Bank Sta=9540.422,10279.38
Exp/Cntr=0.3,0.1

Type RM Length L Ch R = 1 ,67571.77,587.515900,587.515900,587.515900
XS GIS Cut Line= 2
429707.907342046 847444.44317697429192.282342017848043.401510313
#Sta/Elev= 30
9764.699160.1554 9799.81144.10849815.138138.97849845.793130.98219870.994128.7858
9876.448126.82049910.579 108.7179923.775100.48219937.75990.043879950.16572.98433
 9963.3652.921129968.41449.9743610029.7248.9673310060.3851.3639110091.0359.83103
 10134.9 63.889610148.0963.4190910167.67 65.498110240.4664.5566110259.6467.05585
10290.2982.8886110305.6288.4286210320.9589.08953 10351.693.2308810366.93102.9371
10382.26106.446510411.99110.387610443.57112.673510535.54115.272810555.03114.9933
#Mann= 3 , 0 , 0
9764.699    0.04       09764.699    0.04       010555.03    0.04       0
#XS Ineff= 2 , 0
       0                               0
Bank Sta=9764.699,10555.03
Exp/Cntr=0.3,0.1

Type RM Length L Ch R = 1 ,66984.25,550.803700,550.803700,550.803700
XS GIS Cut Line= 3
428869.407762945847241.395775869428942.048329562847271.314951107
429123.153092384848188.369814053
#Sta/Elev= 30
9593.517 99.93169642.825 91.98469672.07793.445449675.83492.20085 9696.2274.65648
9726.79960.968019736.99259.352879777.76559.975139787.95858.122819798.15151.18193
9828.73150.32633 9859.3167.335149869.50368.20934 9889.8962.528999930.66261.62232
9951.04857.397869971.43548.51979 10022.449.2069610042.7960.9229110052.9863.81209
10114.1462.9743710154.9166.6536510256.8463.8413810297.6174.3067810328.1995.10135
10348.58 103.11910409.74107.2069 10470.9102.245310501.48102.665710606.84118.9073
#Mann= 3 , 0 , 0
9593.517  0.0486       09593.517  0.0486       010606.84  0.0486       0
#XS Ineff= 2 , 0
       09870.751                       0
Bank Sta=9593.517,10606.84
Exp/Cntr=0.3,0.1

Type RM Length L Ch R = 1 ,66433.45,739.905500,739.905500,739.905500
XS GIS Cut Line= 3
428395.407342046 847690.53692697428572.730501294847897.492981091
428830.543001294848186.555481076
#Sta/Elev= 30
9592.719123.80859611.765118.7575 9653.57 110.022 9664.44105.99819684.30995.24093
9699.67894.037079745.78680.665019782.958 73.21119822.46461.408939898.70960.35084
 9915.5154.293389942.30948.545729958.80453.609429969.10853.194139982.50848.47709
9995.90747.70693 10018.949.0008110033.9251.6537810048.9558.88409 10062.960.98776
10094.0257.39335 10103.157.79701 10116.563.8458410124.0768.9457710139.0976.62774
 10156.779.92612 10170.187.54579 10196.995.99504 10223.7100.304310252.58 101.228
#Mann= 3 , 0 , 0
9592.719  0.0446       09592.719  0.0446       010252.58  0.0446       0
#XS Ineff= 2 , 0
       0                               0
Bank Sta=9592.719,10252.58
Exp/Cntr=0.3,0.1

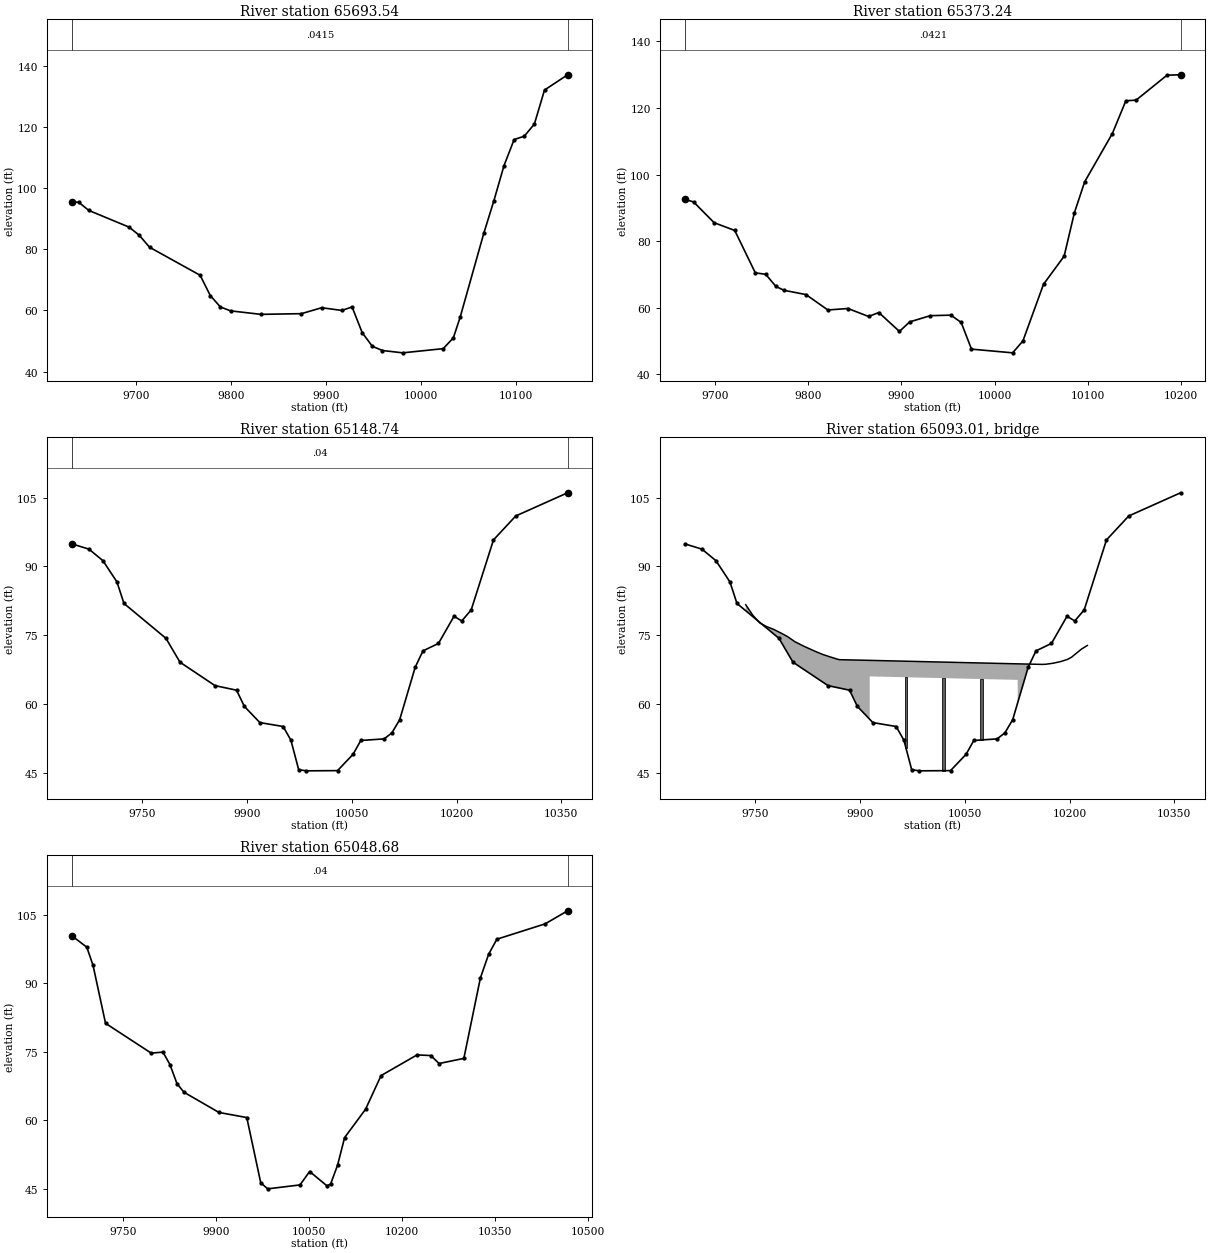
Type RM Length L Ch R = 1 ,65693.54,320.302100,320.302100,320.302100
XS GIS Cut Line= 2
428127.829217046847948.240920037 427945.53755039848437.824253365
#Sta/Elev= 30
9631.86895.48455 9639.0895.425139649.75192.745719692.434 87.23899703.10584.56111
9713.77580.688989767.12971.50315  9777.864.87387 9788.4761.129219799.14159.86051
9831.15358.712489873.83658.939999895.17760.882979916.51959.995119927.18961.14496
 9937.8652.727069948.53148.247469959.20146.880989980.54346.1163810023.23 47.4877
 10033.951.0251210041.19 57.918410065.9185.1858910076.5895.8869610087.25107.3881
10097.92115.930110108.59117.029910119.26121.000410129.93132.145410154.29137.1365
#Mann= 3 , 0 , 0
9631.868  0.0415       09631.868  0.0415       010154.29  0.0415       0
#XS Ineff= 2 , 0
       0 9714.59                       0
Bank Sta=9631.868,10154.29
Exp/Cntr=0.3,0.1

Type RM Length L Ch R = 1 ,65373.24,224.499900,224.499900,224.499900
XS GIS Cut Line= 2
428093.563834636847919.628397744427611.793001303848146.190897744
#Sta/Elev= 30
9667.38392.572759676.847  91.7669698.94885.528719721.04983.20125 9743.1570.45469
9754.20170.047459765.251 66.38349773.99965.220729797.49763.943699820.99659.31605
9842.605 59.75519864.70657.362589875.75758.546599897.85852.869279908.90955.73745
 9931.0157.602339953.111 57.76149964.16255.562649975.21247.5506810019.4146.43743
10030.4750.0259910052.5767.0406410074.6775.4490910085.7288.5166210096.77 97.8271
10126.47112.324710140.97 122.15410152.02122.361410185.17129.854410199.77 129.971
#Mann= 3 , 0 , 0
9667.383  0.0421       09667.383  0.0421       010199.77  0.0421       0
#XS Ineff= 2 , 0
       09776.706                       0
Bank Sta=9667.383,10199.77
Exp/Cntr=0.3,0.1

Type RM Length L Ch R = 1 ,65148.74,100.063700,100.063700,100.063700
XS GIS Cut Line= 4
428109.491543412847911.782586709427882.046376944 847893.10575524
 427579.96304372847745.970338553427488.397793412 847859.69925335
#Sta/Elev= 30
9648.797 94.93699673.37193.789099693.43891.269149713.50586.634699723.53981.94495
9783.74174.327479803.80869.124369853.97764.020529884.84563.020259895.96859.49827
9918.21555.960269951.58455.103889962.70752.10461 9973.8345.678829984.95345.43622
10029.4545.4819510051.6949.0403710062.8252.0601110096.1852.4022910107.31 53.7159
10118.4356.5682410140.6868.01717 10151.871.5947510174.0573.2246410196.29 79.1435
10207.4278.1253810220.9380.5372110252.8295.7960210284.72 101.01910359.03106.0769
#Mann= 3 , 0 , 0
9648.797    0.04       09648.797    0.04       010359.03    0.04       0
#XS Ineff= 2 , 0
       09881.539        10162.66       0
Bank Sta=9648.797,10359.03
Exp/Cntr=0.3,0.1

Type RM Length L Ch R = 3 ,65093.01,,,
BEGIN DESCRIPTION:
END DESCRIPTION:
Bridge Culvert--1,0,-1,-1, 0
Deck Dist Width WeirC Skew NumUp NumDn MinLoCord MaxHiCord MaxSubmerge Is_Ogee
35.596200,28.871300,2.6,0, 32, 32, , , 0.95, 0, 0,0,,
 9736.14 9746.14 9756.14 9766.14 9776.14 9786.14 9795.69 9796.14 9806.23 9816.32
 9826.41 9827.12 9836.50 9846.59 9856.68 9866.77 9867.58 9870.00 9913.74 9913.74
10125.6810125.6810160.9110165.8810170.6410176.5910186.7310196.8710203.0510207.01
10217.1510225.46
   81.66   79.39   77.70   76.89   76.28   75.52   74.74   74.70   73.63   72.84
   72.12   72.08   71.44   70.81   70.30   69.82   69.79   69.68   69.53   69.53
   68.77   68.77   68.65   68.68   68.78   68.91   69.25   69.73   70.24   70.75
   72.00   72.78
 -918.34 -920.61 -922.30 -923.11 -923.72 -924.48 -925.26 -925.30 -926.37 -927.16
 -927.88 -927.92 -928.56 -929.19 -929.70 -930.18 -930.21 -930.32 -930.47   66.03
   65.27 -931.23 -931.35 -931.32 -931.22 -931.09 -930.75 -930.27 -929.76 -929.25
 -928.00 -927.22
 9736.14 9746.14 9756.14 9766.14 9776.14 9786.14 9795.69 9796.14 9806.23 9816.32
 9826.41 9827.12 9836.50 9846.59 9856.68 9866.77 9867.58 9870.00 9910.19 9910.19
10122.1310122.1310160.9110165.8810170.6410176.5910186.7310196.8710203.0510207.01
10217.1510225.46
   81.66   79.39   77.70   76.89   76.28   75.52   74.74   74.70   73.63   72.84
   72.12   72.08   71.44   70.81   70.30   69.82   69.79   69.68   69.54   69.54
   68.79   68.79   68.65   68.68   68.78   68.91   69.25   69.73   70.24   70.75
   72.00   72.78
 -918.34 -920.61 -922.30 -923.11 -923.72 -924.48 -925.26 -925.30 -926.37 -927.16
 -927.88 -927.92 -928.56 -929.19 -929.70 -930.18 -930.21 -930.32 -930.46   66.04
   65.29 -931.21 -931.35 -931.32 -931.22 -931.09 -930.75 -930.27 -929.76 -929.25
 -928.00 -927.22
Pier Skew, UpSta & Num, DnSta & Num=  ,9965.72, 2 ,9962.17, 2 , 0 , 0 , 0 ,,
    4.00    4.00
 -930.66   69.34
    4.00    4.00
 -930.64   69.36
Pier Skew, UpSta & Num, DnSta & Num=  ,10019.71, 2 ,10016.16, 2 , 0 , 0 , 0 ,,
    4.00    4.00
 -930.85   69.15
    4.00    4.00
 -930.84   69.16
Pier Skew, UpSta & Num, DnSta & Num=  ,10073.69, 2 ,10070.14, 2 , 0 , 0 , 0 ,,
    4.00    4.00
 -931.04   68.96
    4.00    4.00
 -931.03   68.97
BR Coef=-1 , 0 , 0 ,, 0 ,,,0.8,0,1,0,
WSPro=,,,, 1 ,,,, 0 ,,,, 0 ,,,,-1 ,-1 ,-1 , 0 , 0 , 0 , 0 , 0
BC Design=,, 0 ,, 0 ,,,,,,

Type RM Length L Ch R = 1 ,65048.68,393.188500,393.188500,393.188500
XS GIS Cut Line= 4
428099.074876785847849.282586709427971.470710099847834.959670022
427591.262376755847638.345086709427431.106126755 847820.63675335
#Sta/Elev= 30
 9667.61100.36259691.83697.860969701.89893.868279722.02481.186769795.65474.65308
9814.55874.878549825.81672.156839837.07467.996399848.33266.095689904.77961.66365
9949.65360.543619972.16946.240069983.42744.93216 10035.445.7902410050.9748.72901
10078.9445.5792910084.7545.9857710096.0150.1337110107.2656.1463110141.0462.36025
10166.0269.7304310224.0574.2696210246.2274.1220510259.5372.3776910299.4773.50047
10326.0991.10176 10339.496.3145610352.7199.60558 10430.5102.9672 10466.7105.8295
#Mann= 3 , 0 , 0
 9667.61    0.04       0 9667.61    0.04       0 10466.7    0.04       0
#XS Ineff= 2 , 0
       09868.725        10161.97       0
Bank Sta=9667.61,10466.7
Exp/Cntr=0.3,0.1