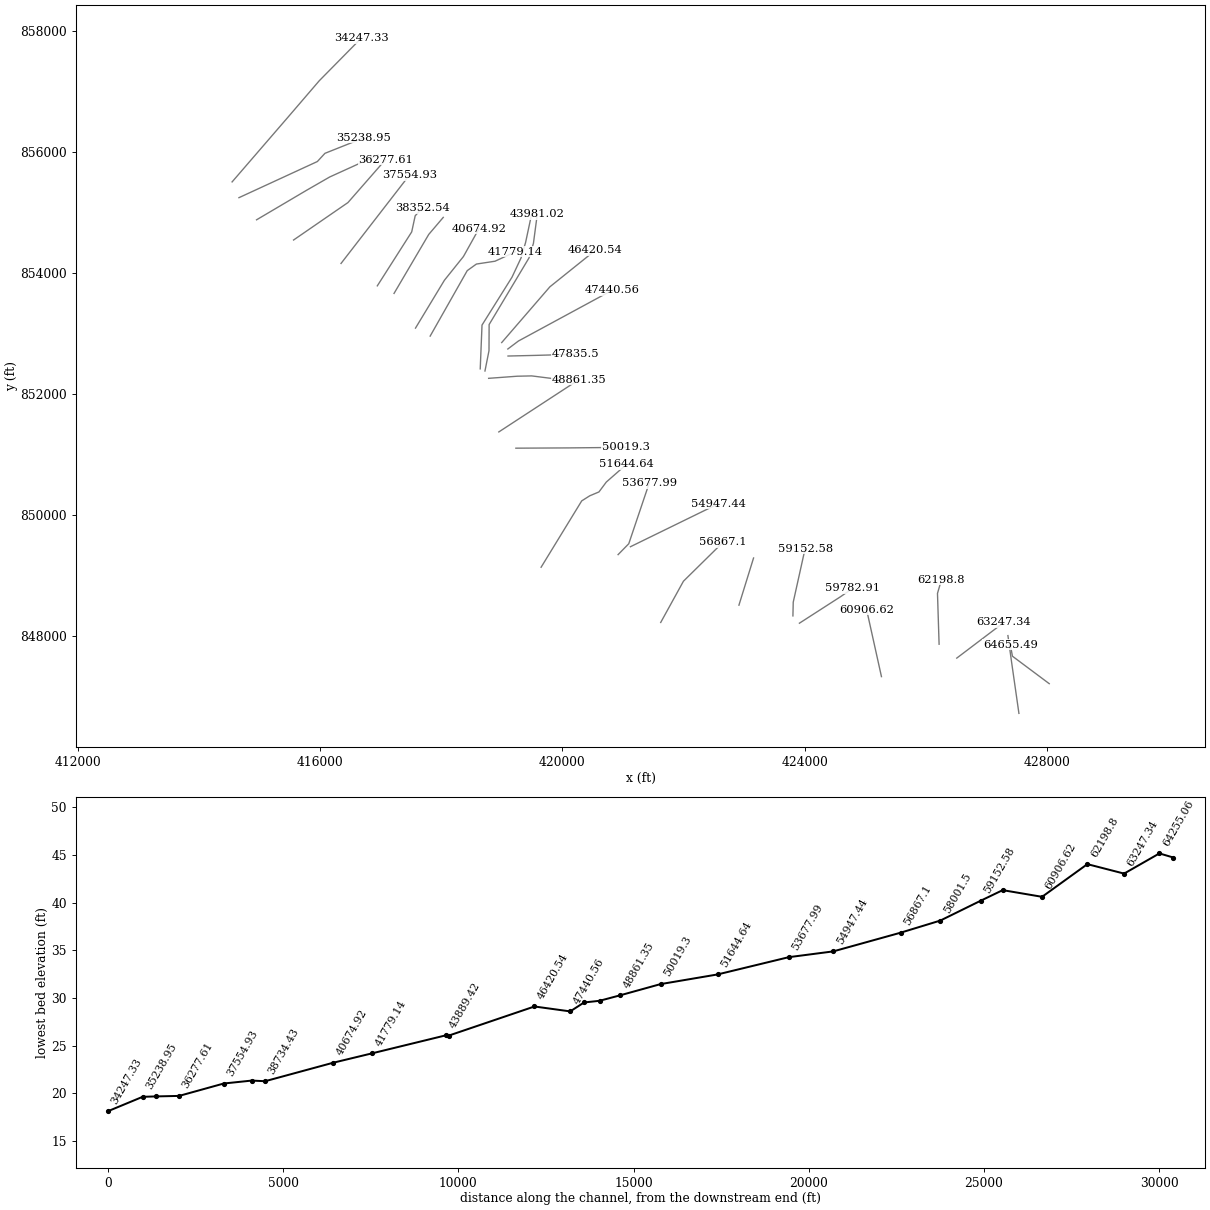
HEC-RAS study 7132_ras.prj: 7132

--- 7132_ras.g01 (geometry) --- (continued)

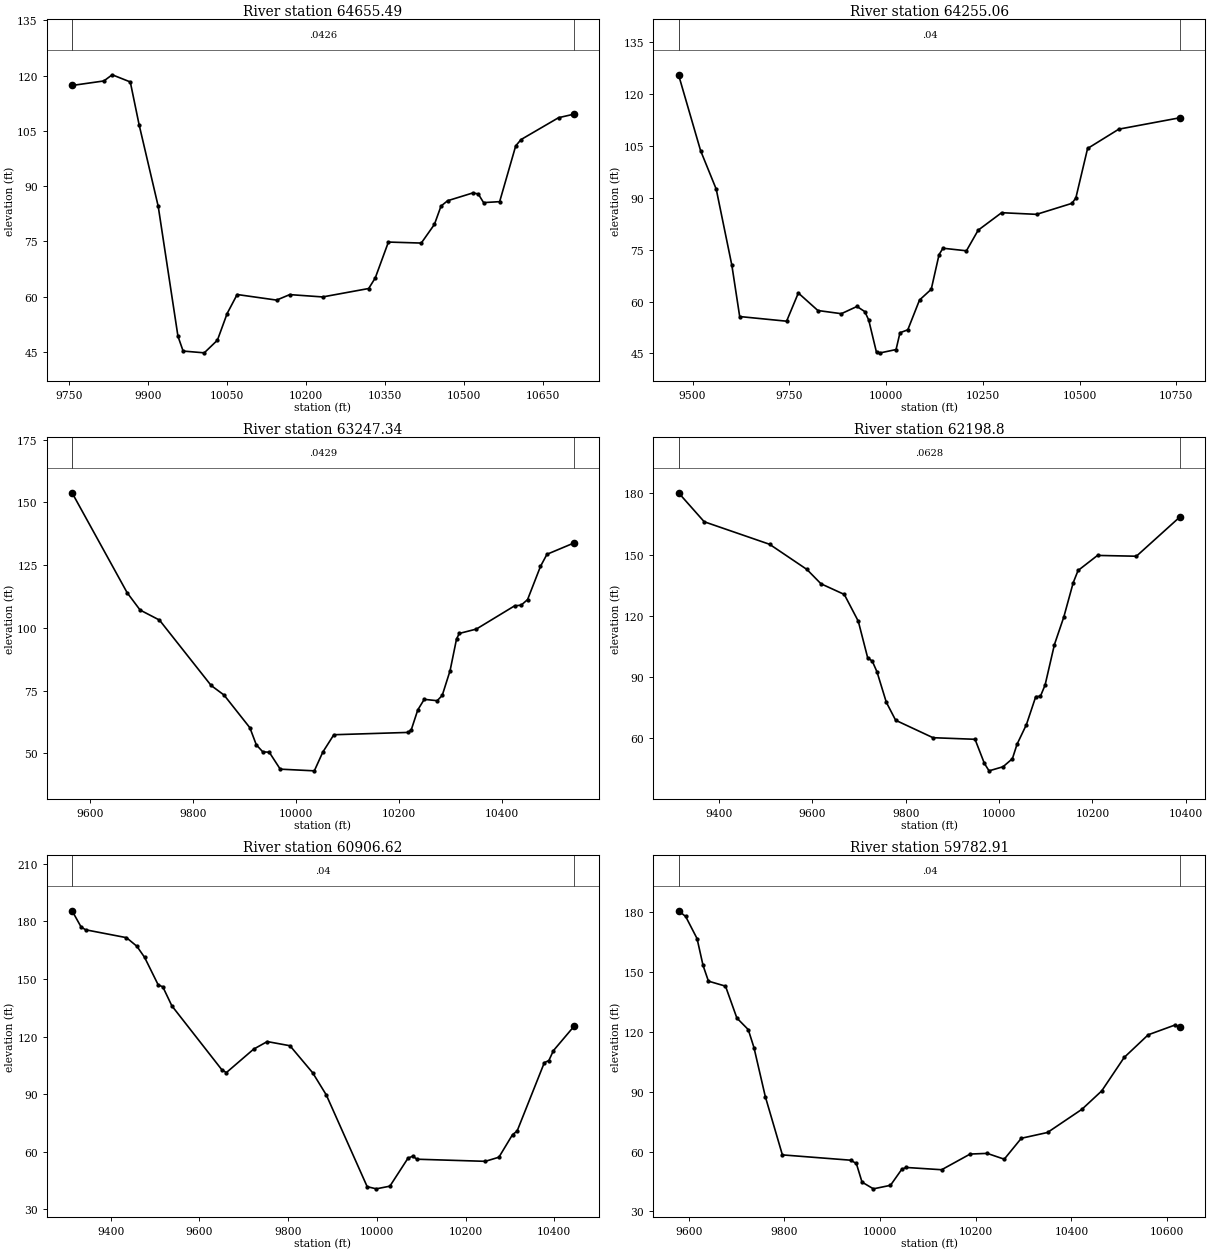
Type RM Length L Ch R = 1 ,64655.49,400.428400,400.428400,400.428400
XS GIS Cut Line= 3
428036.010640621847218.886174649427428.516427666847672.589878365
427393.794205457847863.562100589
#Sta/Elev= 30
9756.044 117.3139816.397118.53799832.192120.21399866.532118.26659883.244106.6753
 9919.5684.490169957.003 49.23899966.80345.2238110006.9344.7424710031.8948.17438
10050.3655.4190610069.3360.5723410144.2259.0566810169.1860.5478710231.5959.91344
10318.9562.2016410331.4465.06736 10356.474.81024 10418.874.5361610443.7779.61414
10456.2584.5731710468.7386.0260210516.7188.1456210526.8887.8695810537.0485.51889
10567.5385.7773410598.02100.920510608.19102.636210679.34108.566810708.37109.5192
#Mann= 3 , 0 , 0
9756.044  0.0426       09756.044  0.0426       010708.37  0.0426       0
#XS Ineff= 2 , 0
       0                10376.76       0
Bank Sta=9756.044,10708.37
Exp/Cntr=0.3,0.1

Type RM Length L Ch R = 1 ,64255.06,1007.723200,1007.723200,1007.723200
XS GIS Cut Line= 3
 427535.72128877846728.579461709427415.061566561847571.461406127
427354.297677696848012.433628365
#Sta/Elev= 30
9463.671125.65139520.667103.69119561.075 92.54689601.48370.496839621.68755.68243
 9742.9154.336069773.21662.494719823.72557.430629884.33756.506679924.74558.59876
9944.949 57.11189955.051  54.6959975.25545.283259985.35645.1789710025.7646.12897
10035.8750.9874710056.0751.8465710086.3860.4656410116.6863.5795310136.8973.61927
10146.9975.45265 10207.674.7111710237.9180.6768910298.5285.7356110388.8585.25865
10480.2388.4439110490.3290.0052110520.61104.316210601.36109.912710760.28 113.234
#Mann= 3 , 0 , 0
9463.671    0.04       09463.671    0.04       010760.28    0.04       0
#XS Ineff= 2 , 0
       09787.763        10324.98       0
Bank Sta=9463.671,10760.28
Exp/Cntr=0.3,0.1

Type RM Length L Ch R = 1 ,63247.34,1048.538000,1048.538000,1048.538000
XS GIS Cut Line= 2
426509.669296086847640.858239993427286.657751948 848229.38733691
#Sta/Elev= 30
9564.659153.79969671.705113.98049696.794107.10519734.429 103.1019834.78877.05542
9859.87773.242479910.05760.220019922.60153.394789935.14650.629149947.69150.47669
9969.00543.7326810035.25  43.06110051.8150.5622410073.1457.4384710217.4358.36336
10223.6859.4920310236.2267.3354110248.7771.5349810273.86 70.993210283.6873.09333
10298.9582.9760310311.4995.5803310316.8197.7766910349.9399.5178610424.39108.7864
10436.94109.027610449.48111.266810474.57124.494710487.12129.302110539.38133.7896
#Mann= 3 , 0 , 0
9564.659  0.0429       09564.659  0.0429       010539.38  0.0429       0
#XS Ineff= 2 , 0
       09789.649                       0
Bank Sta=9564.659,10539.38
Exp/Cntr=0.3,0.1

Type RM Length L Ch R = 1 , 62198.8,1292.184200,1292.184200,1292.184200
XS GIS Cut Line= 3
426218.002629429847870.024906665426191.485361725  848709.0018529
426257.180870205848935.418425187
#Sta/Elev= 30
9313.359180.27899368.361166.08599508.431155.04519588.471 142.7099618.486135.7035
9668.511130.47399698.526 117.3439718.53699.512449728.54197.757269738.546 92.5767
9758.55677.649679778.56668.829949858.60660.289569948.65159.506999968.66147.70882
9978.66644.0529510008.6846.0560510028.6949.99338 10038.757.1076610058.71 66.6841
10078.7280.4023310088.7280.5704510098.7386.0713210118.74105.901210138.75119.3412
   10159 136.21710169.41 142.20810211.06  149.5910294.36149.196510388.51168.6307
#Mann= 3 , 0 , 0
9313.359  0.0628       09313.359  0.0628       010388.51  0.0628       0
#XS Ineff= 2 , 0
       0                               0
Bank Sta=9313.359,10388.51
Exp/Cntr=0.3,0.1

Type RM Length L Ch R = 1 ,60906.62,1123.705000,1123.705000,1123.705000
XS GIS Cut Line= 2
425266.613740534847335.302684426425021.714775026848440.027996153
#Sta/Elev= 30
 9312.65185.51669332.825177.14699343.068175.61579435.253171.5138 9458.72167.0456
9476.224161.24039506.953146.86039517.195 145.9329537.681135.98839650.351102.6818
9660.594 101.1989722.051113.41219752.779117.36089803.993115.19159855.207 101.108
9885.93589.55005 9978.1241.761719998.60640.6257110029.3342.01929 10070.356.64501
10080.5557.6094410090.7956.0589210244.4354.9610210275.1657.1020910305.8968.86986
10316.13 70.676510377.59106.365710387.83107.484110398.07112.636910444.19125.2234
#Mann= 3 , 0 , 0
 9312.65    0.04       0 9312.65    0.04       010444.19    0.04       0
#XS Ineff= 2 , 0
       0                 10248.2       0
Bank Sta=9312.65,10444.19
Exp/Cntr=0.3,0.1

Type RM Length L Ch R = 1 ,59782.91,630.331500,630.331500,630.331500
XS GIS Cut Line= 3
423912.447073877848217.247128889424589.857136071848653.569662839
424790.377969384848791.590496153
#Sta/Elev= 30
9578.521180.60319593.452177.73849617.242166.68019629.772153.23429641.031145.3564
9676.716142.85049700.506126.87759724.295 121.089 9736.19112.1178 9759.9887.50883
9795.66458.333019938.40255.668339950.29754.029479962.19244.693149985.98141.32586
10021.6743.0879510045.4651.1669710054.5252.0312210128.7250.8955510188.1958.74538
10223.8859.0870110259.5656.1756310295.25 66.6526   1035069.5499610422.0981.18682
10463.3790.3836710510.27107.121110560.49118.477910616.09123.338910627.72122.2819
#Mann= 3 , 0 , 0
9578.521    0.04       09578.521    0.04       010627.72    0.04       0
#XS Ineff= 2 , 0
       0                               0
Bank Sta=9578.521,10627.72
Exp/Cntr=0.3,0.1

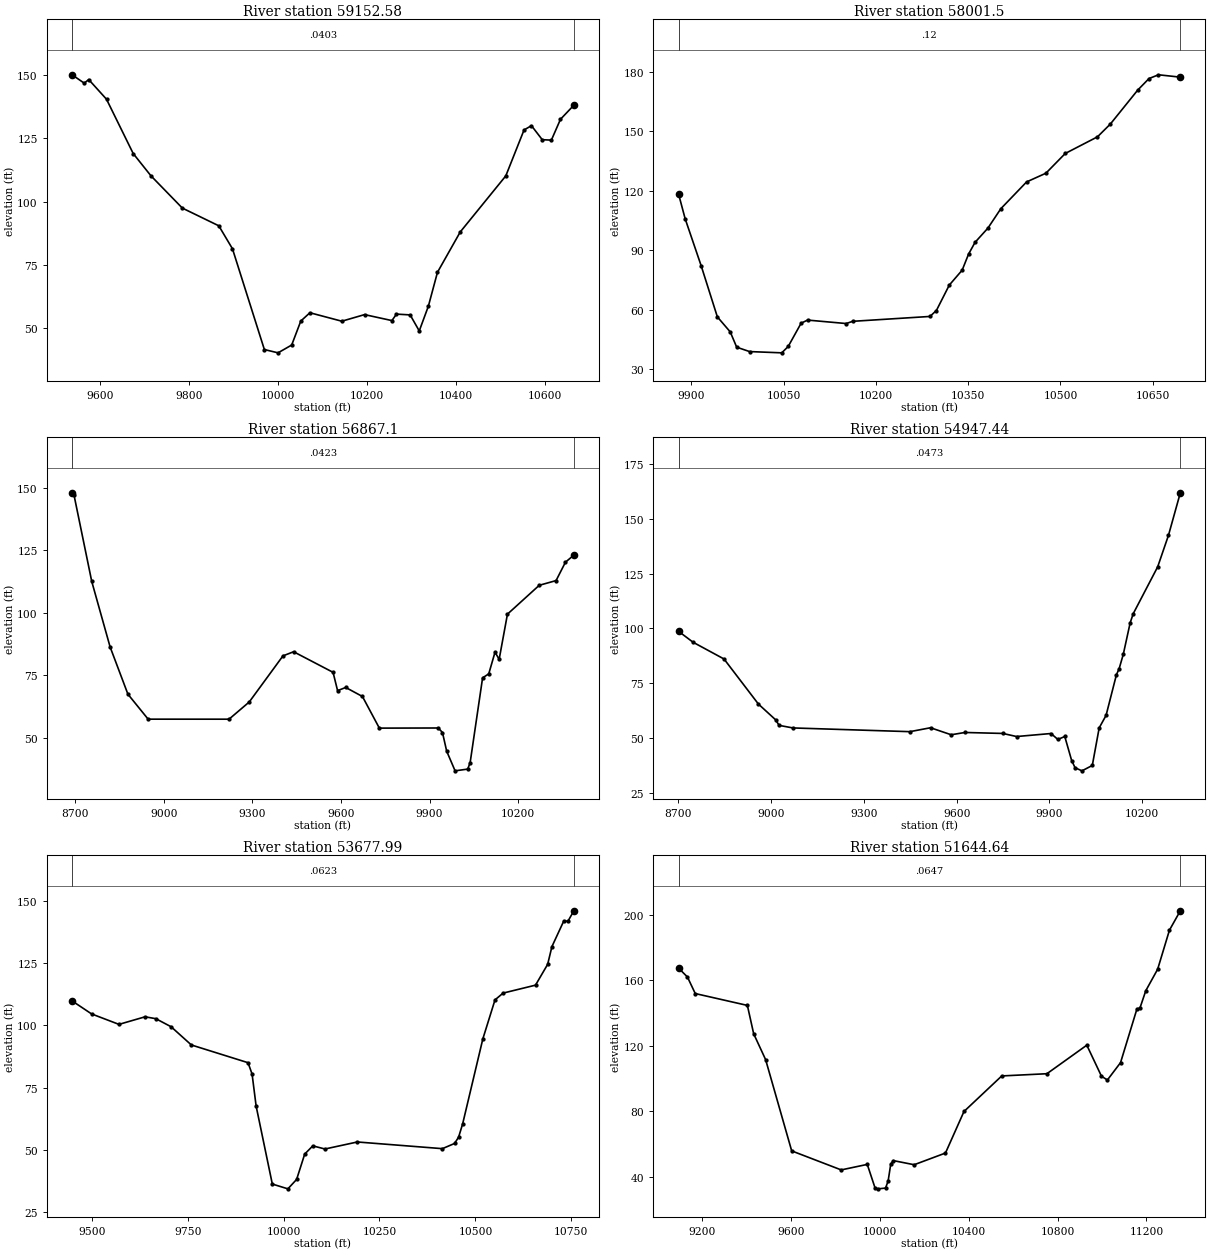
Type RM Length L Ch R = 1 ,59152.58,1151.076800,1151.076800,1151.076800
XS GIS Cut Line= 3
423805.134913892848337.597440615423810.343247175  848564.1599406
424005.655747175849444.368273944
#Sta/Elev= 30
9537.635150.12919565.045146.80529575.048148.24519615.058140.46979675.074118.9989
9715.085110.17199785.60497.42585 9867.5590.42902 9898.2881.343469969.98241.51903
10000.71 40.211610031.4443.2990910051.9352.7783810072.41  56.05910144.1252.71594
10195.33 55.324810256.7952.9616610267.0455.5200810297.7755.2087110318.2548.87404
10338.74 58.646210359.2372.0636510410.4488.0053310512.87110.170110553.85128.3154
10570.52130.013610594.82124.465510615.31124.298410635.79132.538910665.87138.0999
#Mann= 3 , 0 , 0
9537.635  0.0403       09537.635  0.0403       010665.87  0.0403       0
#XS Ineff= 2 , 0
       0                               0
Bank Sta=9537.635,10665.87
Exp/Cntr=0.3,0.1

Type RM Length L Ch R = 1 , 58001.5,1134.405700,1134.405700,1134.405700
XS GIS Cut Line= 2
422914.093348593848514.738351449423155.502629459 849293.63601777
#Sta/Elev= 30
9879.394118.43899890.137105.91369916.235 82.08969942.48456.298989963.42248.71356
9973.891 40.9891 9994.8338.7715810047.1838.1319910057.6541.3768810078.5853.09721
10089.0554.6871910151.8752.9388510162.3454.0623510287.9756.5239310298.4459.52802
10319.3872.3681710340.3279.9175810350.7988.0770810361.2693.9805110382.19101.1768
10403.13110.967210445.01124.505110476.42 128.91410507.83138.884610560.17147.2943
10581.11 153.74710625.59 170.91210643.93176.747510659.37178.655910694.84177.4533
#Mann= 3 , 0 , 0
9879.394    0.12       09879.394    0.12       010694.84    0.12       0
#XS Ineff= 2 , 0
       0                               0
Bank Sta=9879.394,10694.84
Exp/Cntr=0.3,0.1

Type RM Length L Ch R = 1 , 56867.1,1919.662700,1919.662700,1919.662700
XS GIS Cut Line= 3
421622.816196173848229.302841321421997.816196173848909.858396888
422655.304286033849557.273073673
#Sta/Elev= 30
8688.822148.00188695.327147.1206 8755.51112.54178817.67286.378028878.00967.49439
8946.51557.513629220.53857.505019289.04464.38939 9403.2282.811449439.29984.46138
9572.95176.229959588.21168.909999615.70970.188239672.41666.57543 9729.7353.93311
9929.26653.985969943.51952.183139957.77144.722869986.27636.8594910029.0337.55798
10037.31  40.17510079.41 74.0171 10100.375.6304610121.5184.2909210135.5581.44061
10163.6199.4854810271.33111.024210328.34112.904110360.09120.255610388.59123.0893
#Mann= 3 , 0 , 0
8688.822  0.0423       08688.822  0.0423       010388.59  0.0423       0
#XS Ineff= 2 , 0
       08948.675        10119.06       0
Bank Sta=8688.822,10388.59
Exp/Cntr=0.3,0.1

Type RM Length L Ch R = 1 ,54947.44,1269.441000,1269.441000,1269.441000
XS GIS Cut Line= 2
421122.816196203849479.302841321 422580.76001519850191.821684778
#Sta/Elev= 30
8700.645 98.62138747.59793.62725 8847.7785.969768959.07465.373339014.72558.18896
9025.85655.663389070.37754.490589448.80852.79001 9515.5954.575349582.37251.37717
9626.89352.417589749.32751.976089793.84850.568069905.15251.946279927.41249.23071
9949.673 50.58889971.93439.613759983.06436.3129710005.3234.9003210038.7237.36046
10060.98 54.524110083.2460.2196210116.6378.7216610125.6581.6183410138.89 88.0823
10161.15102.4873 10171.2106.689710250.19128.069310285.07142.453210323.38161.8731
#Mann= 3 , 0 , 0
8700.645  0.0473       08700.645  0.0473       010323.38  0.0473       0
#XS Ineff= 2 , 0
       09106.641                       0
Bank Sta=8700.645,10323.38
Exp/Cntr=0.3,0.1

Type RM Length L Ch R = 1 ,53677.99,2033.352400,2033.352400,2033.352400
XS GIS Cut Line= 3
420919.391518325849349.191573322421095.612221688 849528.86672771
 421433.28040719850529.747128889
#Sta/Elev= 30
9448.679109.79159499.533104.5586 9570.94100.35859638.904103.39879666.917102.6493
 9706.8299.407049759.589 92.08879907.34284.964569917.89580.408849928.44967.53187
9970.66436.2114110011.2634.2936910033.9938.0772710055.0948.26052 10076.251.55872
10107.8650.2971310192.29 53.117810413.9250.4338310445.5852.5180710456.1455.03182
10466.6960.3389610519.4694.5692910551.12110.207610572.23112.924410656.66 116.114
10688.32124.468710699.47131.599910730.54141.948310741.09141.754110756.65145.9917
#Mann= 3 , 0 , 0
9448.679  0.0623       09448.679  0.0623       010756.65  0.0623       0
#XS Ineff= 2 , 0
       0                               0
Bank Sta=9448.679,10756.65
Exp/Cntr=0.3,0.1

Type RM Length L Ch R = 1 ,51644.64,1625.341500,1625.341500,1625.341500
XS GIS Cut Line= 6
419648.558185011849140.858239993420318.765799403850236.016348764
420451.311230481850319.946684808420603.419296086850383.913795561
420724.947073877850547.108239979421061.752629489850842.247128889
#Sta/Elev= 30
 9095.14167.35059135.168161.8958 9170.34151.78249404.819144.53799433.161127.2023
9486.887111.41249604.12655.661779826.88144.042939944.12147.411139979.29332.96169
9991.01732.4815410026.1932.9265810037.9137.2245810049.6447.5480810061.3649.72972
10155.1547.2107610295.8454.35075 10379.179.7295710549.02101.455610752.22102.8103
10931.61120.246310997.61 101.293 11024.298.9743211083.35 109.57611157.16142.4064
11170.46142.869311197.05153.550811250.24166.624711303.42190.532211352.29202.3519
#Mann= 3 , 0 , 0
 9095.14  0.0647       0 9095.14  0.0647       011352.29  0.0647       0
#XS Ineff= 2 , 0
       09815.845                       0
Bank Sta=9095.14,11352.29
Exp/Cntr=0.3,0.1

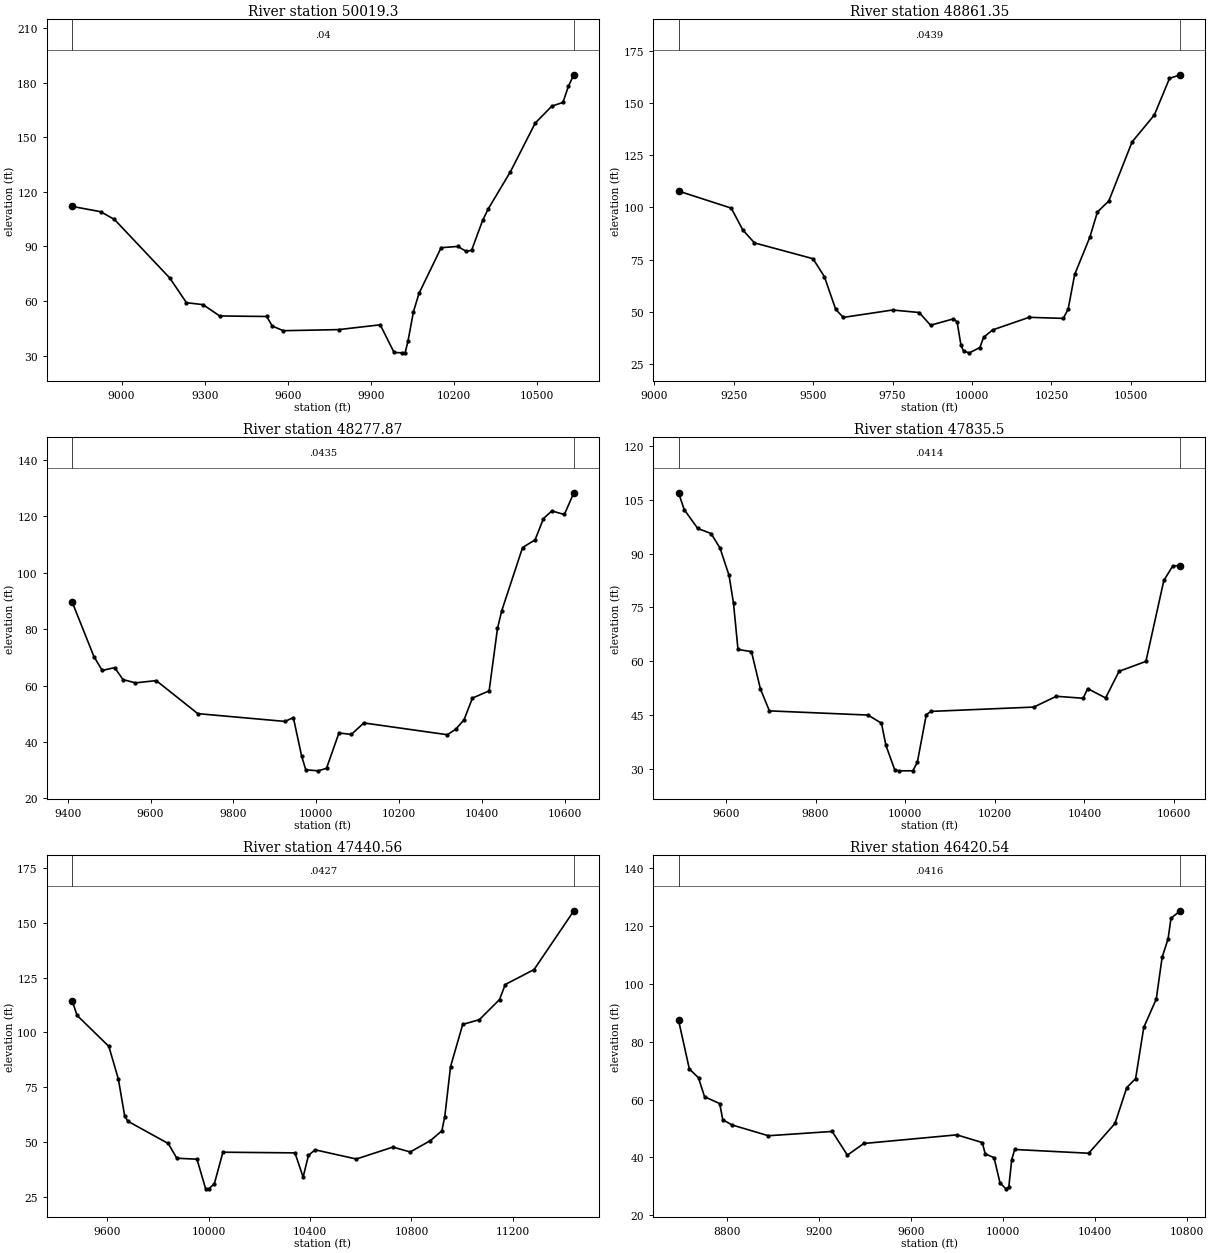
Type RM Length L Ch R = 1 , 50019.3,1157.955300,1157.955300,1157.955300
XS GIS Cut Line= 3
419231.891518354851106.136017784420100.203348964851110.639646873
421044.391518325851120.024906665
#Sta/Elev= 30
8821.181111.96978924.291109.05278974.291104.78839174.29472.552149234.29559.04304
9294.29657.957329354.29751.744679524.29951.449089544.29946.19775  9584.343.63447
9784.30644.241079934.31346.877079984.31631.6698210014.3231.4682710024.32 31.5237
10034.3237.7256910054.3254.0419710074.3264.1261410154.3289.2591710214.33 89.9628
10244.3387.3069110264.3387.7987410304.33104.308310324.33110.571610404.34130.9397
10494.34157.817310554.34167.088710594.35169.115410614.35178.143410633.74 184.317
#Mann= 3 , 0 , 0
8821.181    0.04       08821.181    0.04       010633.74    0.04       0
#XS Ineff= 2 , 0
       09296.724                       0
Bank Sta=8821.181,10633.74
Exp/Cntr=0.3,0.1

Type RM Length L Ch R = 1 ,48861.35,583.473000,583.473000,583.473000
XS GIS Cut Line= 2
418950.507168412851374.268119097420273.558184981852238.080462217
#Sta/Elev= 30
9076.064107.8674 9242.0399.683399278.61489.178979315.19883.008829499.42375.42966
9535.25166.848819571.07951.109749594.96447.282339750.21950.827939833.81849.63104
9869.64643.522479941.30146.564469953.24445.104629965.18734.129039973.705 31.0276
9991.99730.28881 10024.932.8306710036.8437.7363210065.1641.2909810180.1547.32085
10287.6446.8053610302.9651.2832410323.4767.8854610371.2485.7607510395.1297.84853
10430.95103.115310504.17131.412310574.26144.328410622.03161.894510656.14163.6295
#Mann= 3 , 0 , 0
9076.064  0.0439       09076.064  0.0439       010656.14  0.0439       0
#XS Ineff= 2 , 0
       0                               0
Bank Sta=9076.064,10656.14
Exp/Cntr=0.3,0.1

Type RM Length L Ch R = 1 ,48277.87,442.375600,442.375600,442.375600
XS GIS Cut Line= 4
418782.495015651852259.077146873419253.394563824852293.905018136
419492.977897137852299.113351449419987.769563794852236.613351449
#Sta/Elev= 30
9410.72289.735689463.371 70.29389483.42565.349199513.50766.354939533.562 62.1094
9563.64460.943039613.78161.745899714.05450.020789924.52347.254259944.52848.63596
9964.53334.956439974.53530.0869110004.5429.7171810024.5530.6229110054.5543.14796
10084.5642.6551310114.5746.72061 10316.1 42.533610336.2544.4854310356.4147.85846
10376.5755.5337910416.89 58.110610437.0580.2892810447.1386.4622110497.53 108.972
10527.76111.721810547.92119.270110568.08121.972110598.32120.712710621.27128.4189
#Mann= 3 , 0 , 0
9410.722  0.0435       09410.722  0.0435       010621.27  0.0435       0
#XS Ineff= 2 , 0
       0                               0
Bank Sta=9410.722,10621.27
Exp/Cntr=0.3,0.1

Type RM Length L Ch R = 1 , 47835.5,394.934500,394.934500,394.934500
XS GIS Cut Line= 3
419102.352897137852627.238351464419550.269563794852637.655018136
420221.731126755852656.646591321
#Sta/Elev= 30
9494.132106.91089506.783102.23229536.79197.001849566.79995.566429586.80591.50255
 9606.8183.937059616.81376.145829626.81563.303879656.82462.720819676.82952.34069
9696.83446.227289916.89445.062249946.90342.803049956.90736.631089976.91529.70471
9986.91929.5407410016.9329.5545410026.9331.8627410046.9445.1306210056.9546.07712
10287.0447.2858910337.0650.2825410397.0849.7359710407.0952.41333 10447.149.82898
10477.1157.2255110537.1459.9977910577.15 82.539410597.1686.56145 10613.986.65615
#Mann= 3 , 0 , 0
9494.132  0.0414       09494.132  0.0414       0 10613.9  0.0414       0
#XS Ineff= 2 , 0
       09697.646                       0
Bank Sta=9494.132,10613.9
Exp/Cntr=0.3,0.1

Type RM Length L Ch R = 1 ,47440.56,1020.022000,1020.022000,1020.022000
XS GIS Cut Line= 3
419099.097688794852743.123768121419274.120446146          852875
 420823.07661286853713.938258007
#Sta/Elev= 30
9460.564114.53019480.475107.76379605.68493.636669643.24778.746359668.28861.80474
9680.70859.477519839.92449.315089874.04242.574599953.64942.138199987.767 28.6205
9999.13928.6053510021.8830.80754   1005645.3268610340.3245.0204910372.6233.95689
10393.6243.8802410419.9246.41693 10582.642.2136210726.9847.6608610795.2245.44175
10874.8350.5997110920.3255.0944910931.6961.5405410954.4384.3482611002.55103.6631
11068.16105.825711147.77115.005111170.51121.881311284.24 128.70811441.26155.5381
#Mann= 3 , 0 , 0
9460.564  0.0427       09460.564  0.0427       011441.26  0.0427       0
#XS Ineff= 2 , 0
       09713.336        10807.03       0
Bank Sta=9460.564,11441.26
Exp/Cntr=0.3,0.1

Type RM Length L Ch R = 1 ,46420.54,2439.521500,2439.521500,2439.521500
XS GIS Cut Line= 3
418998.186230481852849.460573673419793.325119346853769.599462554
420546.600918412854374.528535783
#Sta/Elev= 30
8589.47887.470288636.44870.58717 8676.3767.540938702.53160.982368768.61358.61364
 8781.8353.028328821.47951.243448980.077 47.49169257.623 48.97889323.70640.78029
9395.19744.80689  9799.547.79956 9910.3345.133859923.15541.226379961.63239.89853
9987.282 31.242210012.9329.1204210025.7629.7422210038.5839.2703810051.4142.73593
10373.1741.4362610487.4751.7322810538.7864.1573810577.2567.2537510612.7384.97613
10667.0394.7784510692.68109.286710718.33115.572510731.16122.756810771.69125.3201
#Mann= 3 , 0 , 0
8589.478  0.0416       08589.478  0.0416       010771.69  0.0416       0
#XS Ineff= 2 , 0
       08792.868                       0
Bank Sta=8589.478,10771.69
Exp/Cntr=0.3,0.1

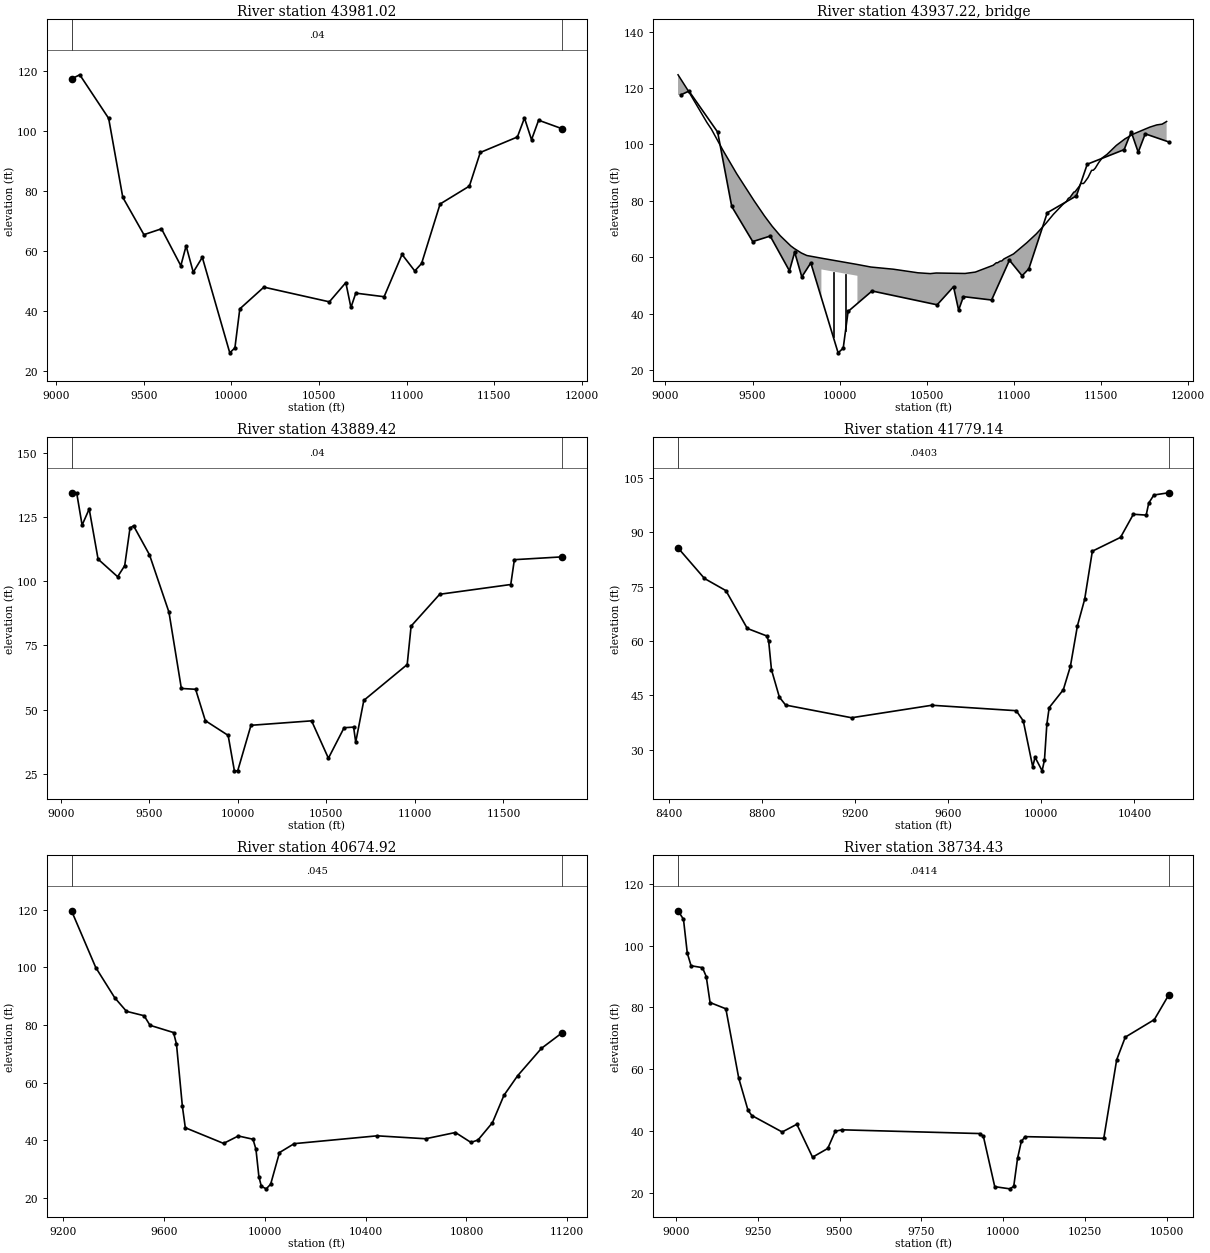
Type RM Length L Ch R = 1 ,43981.02,91.599000,91.599000,91.599000
XS GIS Cut Line= 6
418721.699749559 852380.20317772418788.366416335852715.619844407
418790.449749559853146.869844392419448.783082902854246.869844392
419521.699749649 854486.45317772419585.468493193854967.919051692
#Sta/Elev= 30
9087.931117.51289135.074118.89059299.941104.33689380.51577.980169501.08165.52007
9601.37267.477739711.69355.148839741.78161.765199782.574 52.99259834.23657.95718
9990.96426.0745710020.2627.7250310048.2140.74856 10185.648.00487 10559.243.10136
10653.15 49.514610682.3141.2122410709.9546.0031210871.6244.8047810973.9958.92312
11046.5653.4019111085.4355.9020311190.9675.75034 11358.281.7335411420.24 92.9494
11632.0898.1272811672.42104.456311712.7797.2125311753.12103.7253 11887.2100.8785
#Mann= 3 , 0 , 0
9087.931    0.04       09087.931    0.04       0 11887.2    0.04       0
#XS Ineff= 2 , 0
       09894.619        10175.25       0
Bank Sta=9087.931,11887.2
Exp/Cntr=0.3,0.1

Type RM Length L Ch R = 3 ,43937.22,,,
BEGIN DESCRIPTION:
END DESCRIPTION:
Bridge Culvert--1,0,-1,-1, 0
Deck Dist Width WeirC Skew NumUp NumDn MinLoCord MaxHiCord MaxSubmerge Is_Ogee
30.543600,30.511800,2.6,0, 60, 60, , , 0.95, 0, 0,0,,
 9072.52 9128.98 9238.08 9264.13 9328.82 9408.89 9508.98 9569.03 9612.53 9659.12
 9719.17 9739.19 9780.08 9811.27 9895.13 9895.1310101.8310101.8310178.9910308.31
10449.2510519.7210553.4110719.3910778.1210880.7210898.7610905.4110920.6410930.10
10942.5110997.2011073.7611128.4411183.1311226.4011279.9011300.9811311.5311322.07
11343.1511350.2711374.4711384.5811398.3811404.8111425.0311445.2511455.3611466.16
11485.6911505.9111533.9411586.8011637.3511687.9011778.9011819.3411849.6711875.82
  124.67  119.20  107.78  105.37   98.06   89.60   80.00   74.57   70.97   67.59
   64.00   63.08   61.48   60.59   59.64   59.64   57.40   57.40   56.50   55.73
   54.46   54.17   54.38   54.22   54.71   57.13   58.03   57.99   58.59   58.66
   59.38   61.14   65.13   68.28   71.98   75.21   78.66   79.76   80.84   81.22
   83.06   83.18   85.12   86.17   86.11   86.52   88.26   90.79   90.84   91.54
   93.51   95.17   96.45   99.61  101.97  103.74  106.10  106.90  107.16  108.11
 -875.33 -880.80 -892.22 -894.63 -901.94 -910.40 -920.00 -925.43 -929.03 -932.41
 -936.00 -936.92 -938.52 -939.41 -940.36   55.64   53.40 -942.60 -943.50 -944.27
 -945.54 -945.83 -945.62 -945.78 -945.29 -942.87 -941.97 -942.01 -941.41 -941.34
 -940.62 -938.86 -934.87 -931.72 -928.02 -924.79 -921.34 -920.24 -919.16 -918.78
 -916.94 -916.82 -914.88 -913.83 -913.89 -913.48 -911.74 -909.21 -909.16 -908.46
 -906.49 -904.83 -903.55 -900.39 -898.03 -896.26 -893.90 -893.10 -892.84 -891.89
 9072.52 9128.98 9238.08 9264.13 9328.82 9408.89 9508.98 9569.03 9612.53 9679.14
 9719.17 9749.20 9780.08 9811.27 9902.51 9902.5110109.2110109.2110178.9910308.31
10449.2510519.7210553.4110719.3910778.1210880.7210898.7610905.4110920.6410930.10
10942.5110997.2011073.7611128.4411183.1311226.4011279.9011300.9811311.5311322.07
11343.1511350.2711374.4711384.5811398.3811404.8111425.0311445.2511455.3611466.16
11485.6911505.9111533.9411586.8011637.3511687.9011778.9011819.3411849.6711875.82
  124.67  119.20  107.78  105.37   98.06   89.60   80.00   74.57   70.97   66.35
   64.00   62.68   61.48   60.59   59.56   59.56   57.32   57.32   56.50   55.73
   54.46   54.17   54.38   54.22   54.71   57.13   58.03   57.99   58.59   58.66
   59.38   61.14   65.13   68.28   71.98   75.21   78.66   79.76   80.84   81.22
   83.06   83.18   85.12   86.17   86.11   86.52   88.26   90.79   90.84   91.54
   93.51   95.17   96.45   99.61  101.97  103.74  106.10  106.90  107.16  108.11
 -875.33 -880.80 -892.22 -894.63 -901.94 -910.40 -920.00 -925.43 -929.03 -933.65
 -936.00 -937.32 -938.52 -939.41 -940.44   55.56   53.32 -942.68 -943.50 -944.27
 -945.54 -945.83 -945.62 -945.78 -945.29 -942.87 -941.97 -942.01 -941.41 -941.34
 -940.62 -938.86 -934.87 -931.72 -928.02 -924.79 -921.34 -920.24 -919.16 -918.78
 -916.94 -916.82 -914.88 -913.83 -913.89 -913.48 -911.74 -909.21 -909.16 -908.46
 -906.49 -904.83 -903.55 -900.39 -898.03 -896.26 -893.90 -893.10 -892.84 -891.89
Pier Skew, UpSta & Num, DnSta & Num=  ,9963.37, 2 ,9970.74, 2 , 0 , 0 , 0 ,,
    4.00    4.00
 -941.10   58.90
    4.00    4.00
 -941.18   58.82
Pier Skew, UpSta & Num, DnSta & Num=  ,10033.60, 2 ,10040.97, 2 , 0 , 0 , 0 ,,
    4.00    4.00
 -941.86   58.14
    4.00    4.00
 -941.94   58.06
BR Coef=-1 , 0 , 0 ,, 0 ,,,0.8,0,1,0,
WSPro=,,,, 1 ,,,, 0 ,,,, 0 ,,,,-1 ,-1 ,-1 , 0 , 0 , 0 , 0 , 0
BC Design=,, 0 ,, 0 ,,,,,,

Type RM Length L Ch R = 1 ,43889.42,2110.284000,2110.284000,2110.284000
XS GIS Cut Line= 6
418643.574749559852415.388362914418673.088638455853138.189288855
419167.880305171853928.119844407419317.185860693854245.828177735
419392.508216858854502.353337154419496.005305111854987.147622168
#Sta/Elev= 30
9060.371134.51299090.077134.28679120.172121.90449160.299128.19219210.458108.6387
9320.808101.77919360.814106.08869390.816120.76439410.817 121.6389500.821110.3331
9610.82687.955559680.83658.212939761.37957.890029816.16145.660339945.13439.91396
9980.30926.121569999.07626.0926110074.1143.8502110416.4845.5884710511.4231.00676
10600.0942.9039110653.8343.13968 10665.737.2866310711.5253.56924 10956.567.53338
 10978.682.53325   1114094.9390411541.5498.74787 11561.9108.430711831.48109.5237
#Mann= 3 , 0 , 0
9060.371    0.04       09060.371    0.04       011831.48    0.04       0
#XS Ineff= 2 , 0
       09881.626        10162.36       0
Bank Sta=9060.371,11831.48
Exp/Cntr=0.3,0.1

Type RM Length L Ch R = 1 ,41779.14,1104.210500,1104.210500,1104.210500
XS GIS Cut Line= 5
417817.191588998852956.087626025418429.170755655854036.816792697
418580.212422311854145.323737144418887.504088998854192.198737144
419222.573533446854346.712626025
#Sta/Elev= 30
8439.26785.650868552.93777.224428644.87373.884268736.809 63.45538820.41261.38745
8828.745 59.90518840.70752.080868874.71344.51055 8901.5942.328219184.99638.83531
9529.75642.27844 9892.2940.779949922.63737.96316  9963.125.343279973.21627.95309
10003.5624.1990410013.6827.2182310023.7937.0086910033.9141.63331 10094.646.54781
10124.9552.98697 10155.3 64.203510186.3271.4906610219.3584.7511210340.4988.56592
10395.5594.9340310450.6194.6986510461.6298.0160210483.64100.239710547.04100.8551
#Mann= 3 , 0 , 0
8439.267  0.0403       08439.267  0.0403       010547.04  0.0403       0
#XS Ineff= 2 , 0
       08817.476                       0
Bank Sta=8439.267,10547.04
Exp/Cntr=0.3,0.1

Type RM Length L Ch R = 1 ,40674.92,1940.492400,1940.492400,1940.492400
XS GIS Cut Line= 4
417575.110756367853088.233686224 418052.54131192853878.164241806
418366.718493193854270.002385005418621.117700815854726.688547343
#Sta/Elev= 30
9232.026 119.6499328.476 99.93919403.51789.502979450.25584.781329520.36283.25125
9543.73279.937199637.20877.417999648.89373.387839672.26251.823769683.94744.40638
9835.84638.973729894.26941.550529952.69240.422779964.37736.936099976.06127.44984
9985.78624.1100710005.1223.21901 10022.824.8304610057.8535.8005310116.2838.88896
10445.7741.6058410638.0440.5887210756.4842.7569710818.13 39.311810846.1440.16065
10903.3746.1561110949.1655.6557811003.0762.4038411097.9771.9368711180.0377.33293
#Mann= 3 , 0 , 0
9232.026   0.045       09232.026   0.045       011180.03   0.045       0
#XS Ineff= 2 , 0
       0                               0
Bank Sta=9232.026,11180.03
Exp/Cntr=0.3,0.1

Type RM Length L Ch R = 1 ,38734.43,381.889000,381.889000,381.889000
XS GIS Cut Line= 3
417220.885159867853660.627385012417793.801826534854634.585718346
418033.385159867854915.835718346
#Sta/Elev= 30
9006.334 111.2349023.009108.46549034.61197.554219046.21393.449969081.01892.83541
 9092.6289.940479104.22281.552019152.51279.526629191.95857.05823 9220.2446.68206
9231.84245.005349324.65639.670529369.46642.170189417.47131.517569463.878 34.3398
9487.08239.933459507.52740.375759927.95139.168169939.55338.290469974.35821.98512
10020.3321.2818710032.3722.0817110043.97 31.107610055.5736.6084810067.1738.16519
10307.6237.6445710347.0363.04701 10373.370.3552910461.9976.0183810505.7683.94273
#Mann= 3 , 0 , 0
9006.334  0.0414       09006.334  0.0414       010505.76  0.0414       0
#XS Ineff= 2 , 0
       0                               0
Bank Sta=9006.334,10505.76
Exp/Cntr=0.3,0.1

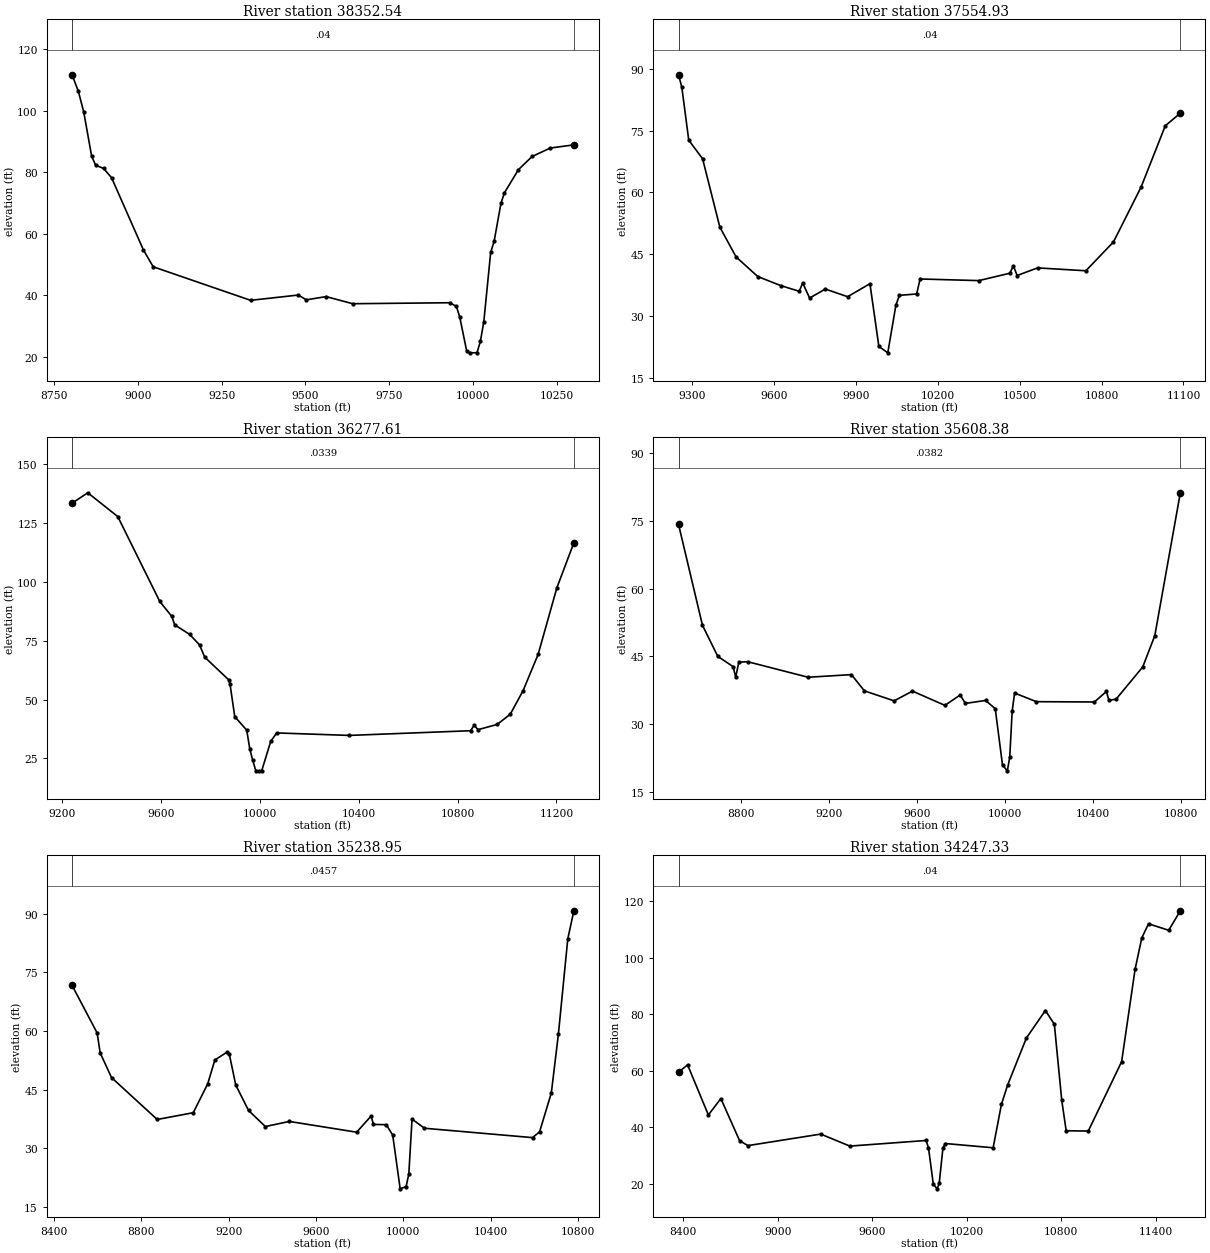
Type RM Length L Ch R = 1 ,38352.54,797.616800,797.616800,797.616800
XS GIS Cut Line= 4
  416944.8434932853785.627385012417512.551826534854676.252385013
  417569.8434932854941.877385013417684.426826534855066.877385013
#Sta/Elev= 30
8803.501111.73978822.396106.31788838.33399.638218862.05185.19466 8873.9182.36841
8897.62881.277638921.34578.284959016.21654.834049045.64749.318519336.403 38.4156
9478.70940.140719502.42738.568099561.72139.63408 9640.9837.315879930.00537.63445
9950.46536.458019960.694 32.85739981.15421.926019991.38421.3476410011.8421.38824
10022.0725.09535 10032.331.5159410052.7654.0008810062.9957.5807610083.4569.97647
10093.6873.3549810135.65 80.907610176.3485.1776110230.6187.9230710300.9888.95722
#Mann= 3 , 0 , 0
8803.501    0.04       08803.501    0.04       010300.98    0.04       0
#XS Ineff= 2 , 0
       0                               0
Bank Sta=8803.501,10300.98
Exp/Cntr=0.3,0.1

Type RM Length L Ch R = 1 ,37554.93,1277.316000,1277.316000,1277.316000
XS GIS Cut Line= 2
416345.885159867854155.419051679417470.885159867 855608.54405168
#Sta/Elev= 30
 9250.7288.547289262.83785.48739 9288.1372.665199338.71768.18508 9401.9551.56533
9461.632 44.31919541.06339.554839624.98537.370279692.82335.983059705.46937.99705
9730.76334.344629788.337 36.52899870.01434.66758 9951.6937.82312 9984.3622.60776
10017.0321.0407510046.9332.6570310059.5835.0020810122.8135.3308910135.4638.97054
10350.4538.5783610464.2740.3714910476.9142.1835410490.7539.8145810565.4441.66239
10742.4940.9650710843.6747.9673610944.84  61.29711033.37 76.167911088.4479.22873
#Mann= 3 , 0 , 0
 9250.72    0.04       0 9250.72    0.04       011088.44    0.04       0
#XS Ineff= 2 , 0
       0                               0
Bank Sta=9250.72,11088.44
Exp/Cntr=0.3,0.1

Type RM Length L Ch R = 1 ,36277.61,669.234500,669.234500,669.234500
XS GIS Cut Line= 3
415562.604969352854542.314994097416460.468493193 855160.62738502
 417080.26015991855868.960718364
#Sta/Elev= 30
9239.586133.42579303.203137.85059424.622127.73019594.60791.684659643.17485.36526
9655.31681.738629716.02577.66116 9755.6373.213759776.73468.010569873.86958.37539
 9879.0556.576269898.15242.78253 9946.72 37.00459958.86129.142359971.00324.18706
9983.14519.879379995.287 19.739110007.4319.8166810043.8532.2830710068.1435.83911
10362.14 34.786410852.9636.7792610867.0739.0525810883.3337.2490110960.0939.42447
11013.24 43.732511065.56 53.831511126.3169.1980411202.2397.4971111270.97116.6008
#Mann= 3 , 0 , 0
9239.586  0.0339       09239.586  0.0339       011270.97  0.0339       0
#XS Ineff= 2 , 0
       0                               0
Bank Sta=9239.586,11270.97
Exp/Cntr=0.3,0.1

Type RM Length L Ch R = 1 ,35608.38,369.427200,369.427200,369.427200
XS GIS Cut Line= 4
414951.493858248 854875.64832744415778.176826537855363.752385005
 416158.38515988855582.502385035416960.468493193855947.085718364
#Sta/Elev= 30
8517.73574.205238626.32451.901658696.00245.009068765.67942.739438777.29240.43676
8791.81843.717238831.15543.833519106.51440.389029303.19940.971149362.20437.37316
 9497.1735.169329580.52537.32135 9727.9134.167929797.13136.462199821.15334.60238
9912.501 35.25459956.62733.43546 9989.5820.9662310011.5519.6858310022.5322.73265
10033.5232.90401 10044.536.8964310143.3634.9872610406.9934.9180710461.9237.24553
 10472.935.2570410505.8635.5599610626.6942.6681510681.6149.6097610797.4681.19711
#Mann= 3 , 0 , 0
8517.735  0.0382       08517.735  0.0382       010797.46  0.0382       0
#XS Ineff= 2 , 0
       09231.593                       0
Bank Sta=8517.735,10797.46
Exp/Cntr=0.3,0.1

Type RM Length L Ch R = 1 ,35238.95,991.617200,991.617200,991.617200
XS GIS Cut Line= 4
414660.695247114855241.099716321 415955.26015991855837.710718364
 416080.26015991 855973.12738502 416720.88515988856228.335718349
#Sta/Elev= 30
8482.20571.675218597.05459.507498610.98454.413358663.11948.096338872.32537.38217
9037.48839.114769103.55446.469329136.58652.61177 9191.6454.581949202.65154.10076
9232.178 46.21249290.73839.699789367.814 35.58019477.92336.880199786.22734.12891
9852.29238.256279863.30336.118899921.99236.048779951.479  33.3859985.59819.64454
10012.82 20.222710025.1923.3965610040.0337.4803510097.0235.1387710592.1832.74449
10624.4834.22112 10678.344.1827610710.5959.1647210753.6583.5783610781.5190.75614
#Mann= 3 , 0 , 0
8482.205  0.0457       08482.205  0.0457       010781.51  0.0457       0
#XS Ineff= 2 , 0
       09251.974                       0
Bank Sta=8482.205,10781.51
Exp/Cntr=0.3,0.1

Type RM Length L Ch R = 1 ,34247.33,1842.826900,1842.826900,1842.826900
XS GIS Cut Line= 4
414547.848024905855501.516383007415481.301826537856582.502385035
 415986.51015994857171.044051692416676.754274905857871.308049664
#Sta/Elev= 30
8370.17359.394248427.62662.056958559.74944.296678639.02450.114098757.93535.20052
8810.78433.442589273.21837.525729458.19133.274659942.26635.259119957.61932.74585
9988.325 19.815910012.5718.1319210025.7520.0295910049.7432.7177910065.2834.18324
 10368.432.6738710421.12 48.074210460.6554.9381810579.6171.5607310700.1181.29354
10757.0976.4530310804.2749.4225710832.3538.7029910972.7638.6001711184.4463.15841
11269.9195.8829111312.65107.020711355.38112.004611483.59109.715411557.32116.6194
#Mann= 3 , 0 , 0
8370.173    0.04       08370.173    0.04       011557.32    0.04       0
#XS Ineff= 2 , 0
       09123.497        10624.07       0
Bank Sta=8370.173,11557.32
Exp/Cntr=0.3,0.1