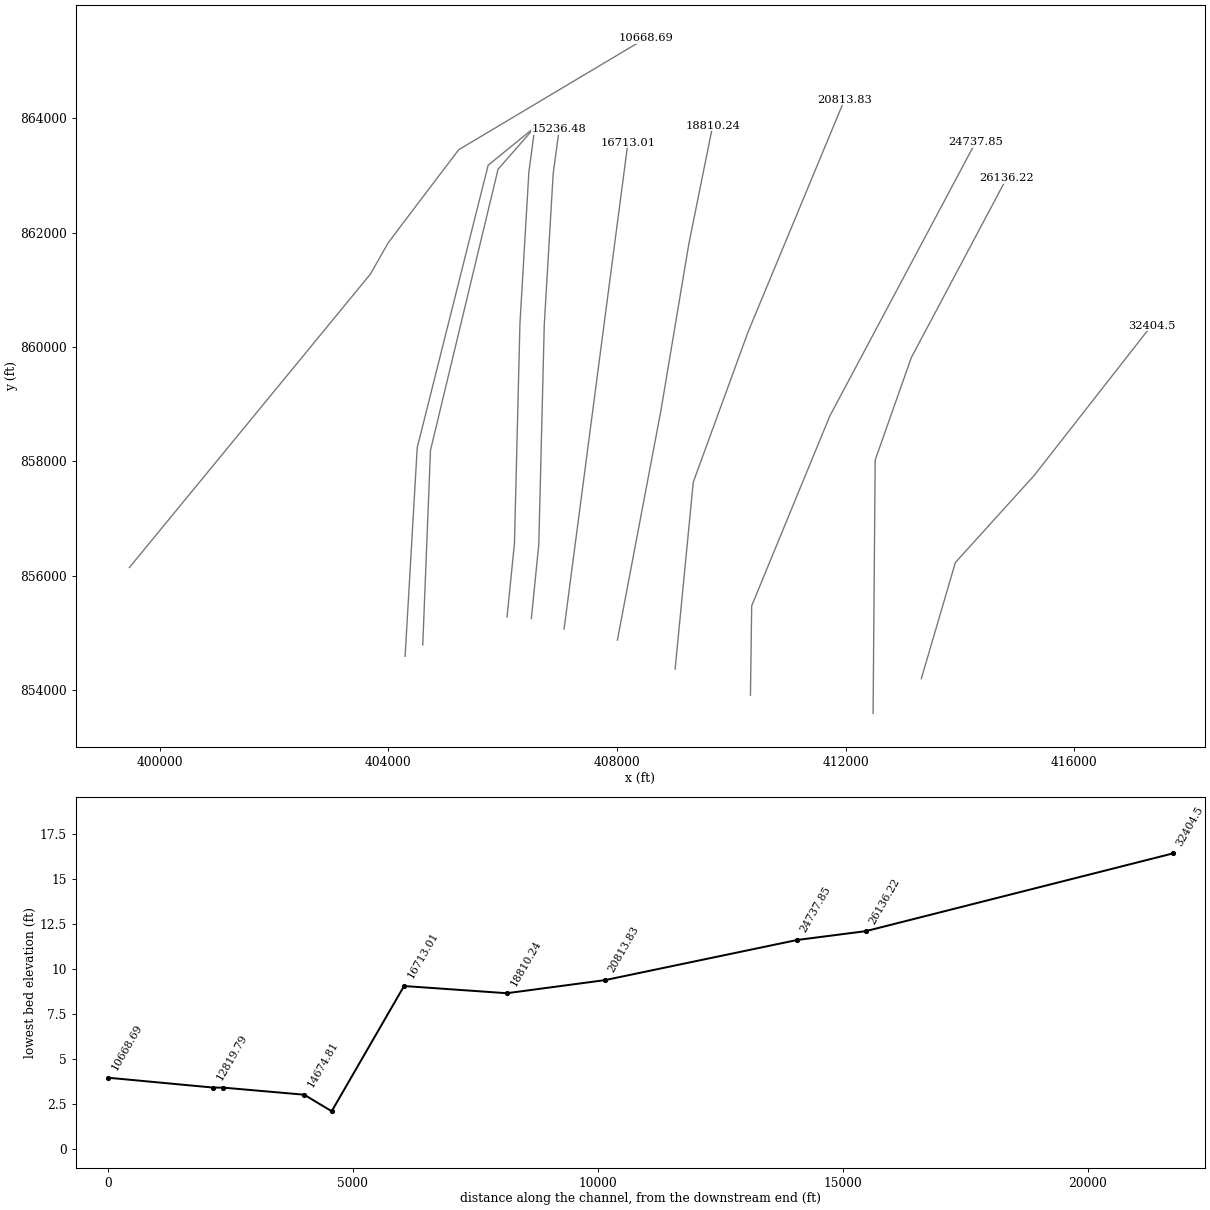
HEC-RAS study 7132_ras.prj: 7132

--- 7132_ras.g01 (geometry) --- (continued)

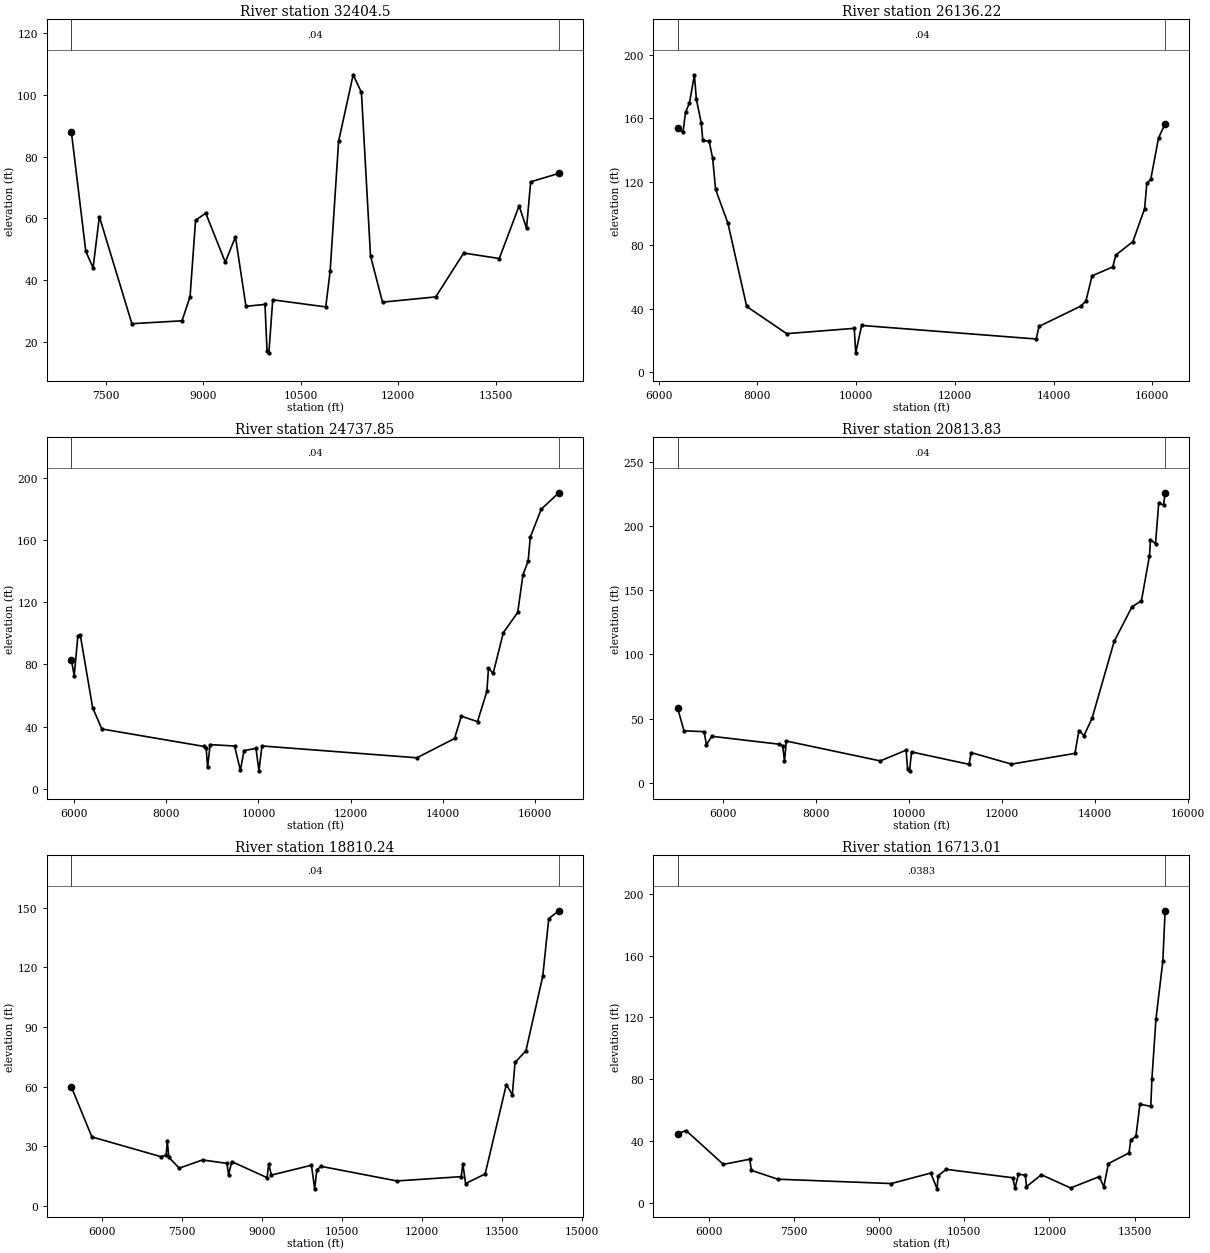
Type RM Length L Ch R = 1 , 32404.5,6268.286700,6268.286700,6268.286700
XS GIS Cut Line= 4
413320.851497114854201.603188545413917.040592104856233.628228083
415298.342284441 857759.24502261417346.459136009860375.648327455
#Sta/Elev= 30
6972.09988.090027194.49149.274597306.51743.977747402.92260.562927903.15525.85442
8674.34826.788828798.36934.628148882.77859.353049039.10161.709529340.02645.79246
9496.32554.005049658.20331.489259950.894 32.10839981.95917.1126310010.4916.40386
10070.0933.5863110885.7831.2964910953.2342.9025211083.2484.9793911307.51106.5449
11434.51100.8064 11574.247.8051311758.8732.8385412577.4734.5355213008.06 48.7506
13555.3346.9817313860.1164.0513113974.41 56.805714037.9171.8414414470.5174.56789
#Mann= 3 , 0 , 0
6972.099    0.04       06972.099    0.04       014470.51    0.04       0
#XS Ineff= 2 , 0
       09485.528        11247.14       0
Bank Sta=6972.099,14470.51
Exp/Cntr=0.3,0.1

Type RM Length L Ch R = 1 ,26136.22,1398.368600,1398.368600,1398.368600
XS GIS Cut Line= 4
412477.370453238853596.041422531412513.979673069858025.757026266
 413147.34179516859819.213102865414813.295460793862951.980828296
#Sta/Elev= 30
6381.996154.07356490.958151.1514 6540.96163.83496620.963169.73786720.966187.4699
6760.968171.99996860.971156.86146890.972146.16817020.977145.46957090.979134.7728
7150.981115.1457 7400.9993.759767781.00241.32854 8591.0324.184199961.07727.54348
9991.07812.0855710111.0829.3772213649.1620.8189113705.7928.7523614555.2441.59344
14657.1844.7783814781.7760.6662615200.7866.2662715264.6773.7988215608.5782.21911
15846.41103.023215891.72118.9595   15971121.486316129.57147.726316262.06156.4664
#Mann= 3 , 0 , 0
6381.996    0.04       06381.996    0.04       016262.06    0.04       0
#XS Ineff= 2 , 0
       09073.607        13506.34       0
Bank Sta=6381.996,16262.06
Exp/Cntr=0.3,0.1

Type RM Length L Ch R = 1 ,24737.85,3924.020000,3924.020000,3924.020000
XS GIS Cut Line= 4
410331.958655238853913.352356074410353.660044127855475.852356074
411720.847544127858796.164856074414270.760738571863581.321106074
#Sta/Elev= 30
5941.38982.975896003.04372.78602 6083.05 98.21216133.05599.188696403.08152.17544
  6603.138.492428811.68127.312998865.75426.209118898.19813.746948952.27128.45297
9482.18527.547769608.67611.936529687.46824.585699947.21226.02579 10012.111.59664
10076.9927.5778713439.0519.97847 14254.932.3740214402.2146.7151614753.4743.20664
14957.4462.7395714991.4377.5226615093.41  74.24115313.93100.360315625.98113.3722
15739.22137.5158 15852.6146.376315897.93161.690716135.88179.677516516.97 190.239
#Mann= 3 , 0 , 0
5941.389    0.04       05941.389    0.04       016516.97    0.04       0
#XS Ineff= 2 , 0
       09274.511        13495.33       0
Bank Sta=5941.389,16516.97
Exp/Cntr=0.3,0.1

Type RM Length L Ch R = 1 ,20813.83,2003.589300,2003.589300,2003.589300
XS GIS Cut Line= 4
409014.239836036854369.546065597409331.537119895857637.708089188
410289.870453238860262.708089203411977.370453209864325.208089188
#Sta/Elev= 30
5026.00458.039585162.09440.578515594.11639.855945644.351 29.5611 5758.2636.28715
 7207.04 30.12247282.01628.933187322.20417.089547362.392 32.56689381.85317.09525
9935.42325.457699967.35911.0400110009.949.36614110052.5224.0934811290.5614.41859
11333.8723.5764312200.1514.6054913564.5322.9554913651.1540.6985913759.4436.77716
13932.69 50.284714409.14110.309114793.01137.246714993.88141.791615167.13 176.831
15188.79189.361915297.07186.323115366.52 218.28515470.33216.375915503.04225.9701
#Mann= 3 , 0 , 0
5026.004    0.04       05026.004    0.04       015503.04    0.04       0
#XS Ineff= 2 , 0
       08971.362         12986.1       0
Bank Sta=5026.004,15503.04
Exp/Cntr=0.3,0.1

Type RM Length L Ch R = 1 ,18810.24,2097.228300,2097.228300,2097.228300
XS GIS Cut Line= 4
408004.377165258854876.639823556          408765858886.341207922
409253.411196768 861799.78591612409671.043831915863869.695379108
#Sta/Elev= 30
5424.72459.885625809.83134.736737102.47924.832897204.26325.585097224.61932.64703
7255.154 24.47017448.54319.028227886.21123.159888344.236  21.4418374.77115.81938
8435.84122.311519097.43214.252249127.96721.137929178.85915.551679930.43220.50025
9991.2698.63895110031.8318.3045610112.9419.9347611532.48 12.611812740.7914.76481
 12771.421.24095 12822.411.3084113189.6616.1069713587.5261.0741813699.7355.85383
13750.7472.1718713954.7778.0052114271.02 115.49114383.23144.448414571.65148.3895
#Mann= 3 , 0 , 0
5424.724    0.04       05424.724    0.04       014571.65    0.04       0
#XS Ineff= 2 , 0
       08798.039        12679.66       0
Bank Sta=5424.724,14571.65
Exp/Cntr=0.3,0.1

Type RM Length L Ch R = 1 ,16713.01,1476.536900,1476.536900,1476.536900
XS GIS Cut Line= 2
 407071.03272453 855067.75466612408188.654252321863574.699110568
#Sta/Elev= 30
5455.65644.769295604.16646.737416259.75224.877276723.70528.189186753.96220.99893
7217.91515.27604 9214.9312.462219910.85919.25016 10021.89.03801810041.9817.55444
10183.1821.6638211353.1516.2151511393.499.37398911454.0118.5063311575.0417.89592
11595.2110.4484611857.4418.1573712371.839.59942112876.1216.9236812956.8110.36328
 13037.525.3915313400.5932.2558813430.8540.7673713521.6242.9215613592.2263.78833
13783.86 62.439813804.0380.4073813874.63118.927913995.66156.3213 14035.7188.9651
#Mann= 3 , 0 , 0
5455.656  0.0383       05455.656  0.0383       0 14035.7  0.0383       0
#XS Ineff= 2 , 0
       09430.978        12527.67       0
Bank Sta=5455.656,14035.7
Exp/Cntr=0.3,0.1

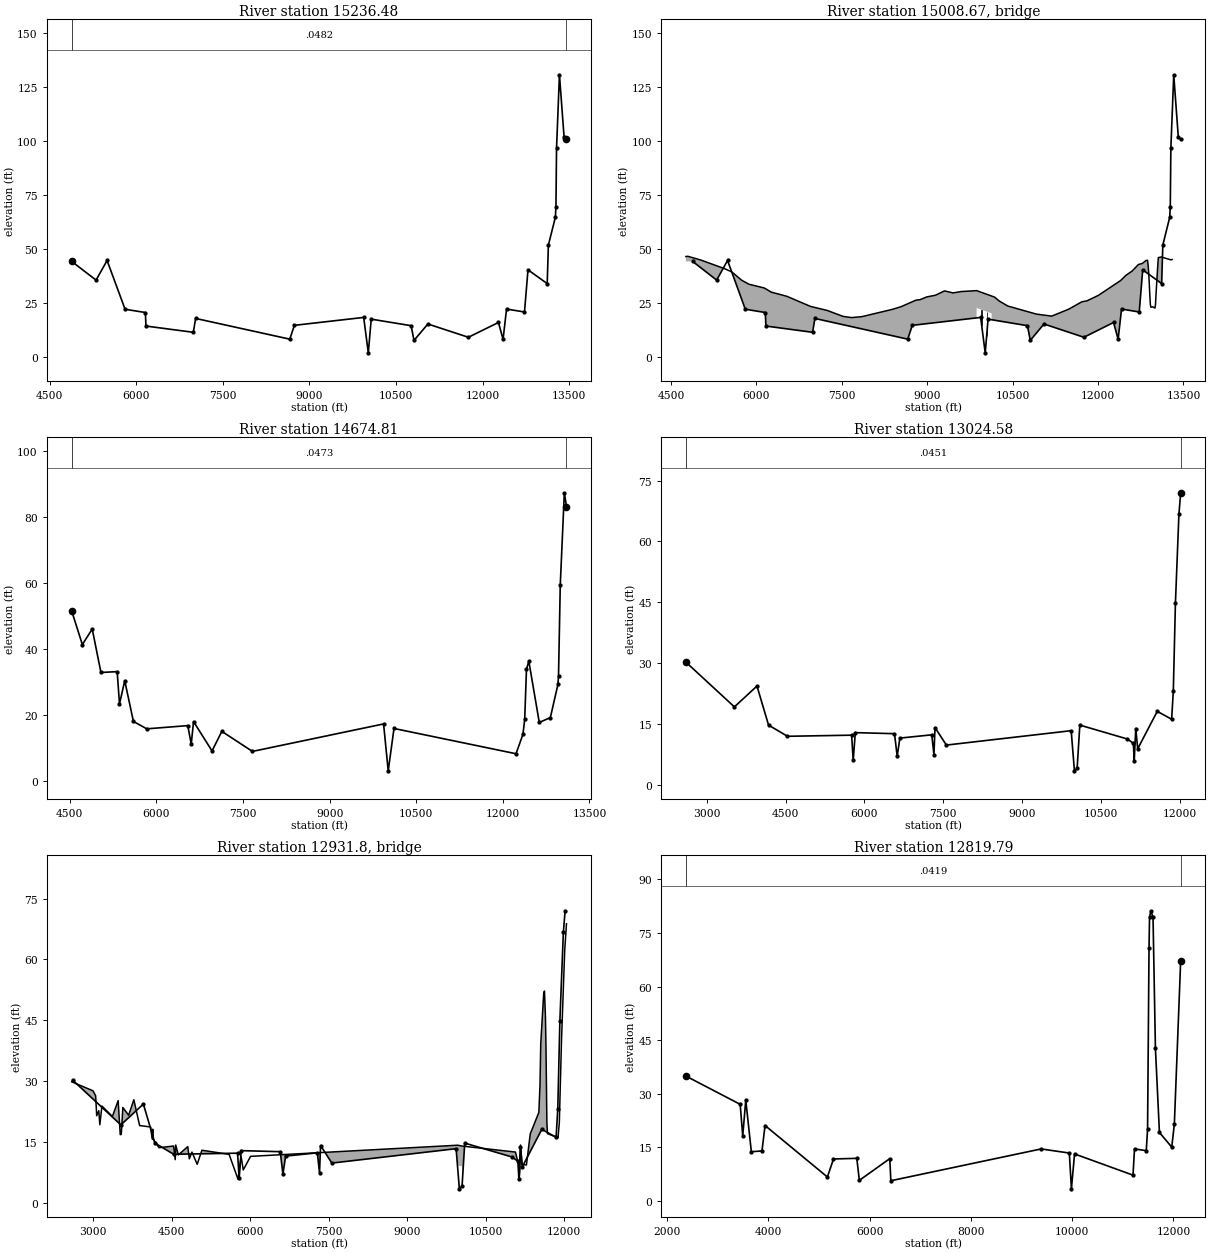
Type RM Length L Ch R = 1 ,15236.48,561.664900,561.664900,561.664900
XS GIS Cut Line= 5
406499.245453192 855255.51769567406629.453786565856548.920473446
 406724.93989764860385.726029014 406881.18989764863033.295473461
406985.356564297863805.864917894
#Sta/Elev= 30
4882.276 44.40255303.87835.756365494.83944.839165806.40622.268166158.17520.75123
6168.22514.486886988.54511.591337028.55818.011778659.0628.4193278739.087 14.8191
9939.45918.4825210019.482.08395710069.5717.6836410760.7714.6563510810.867.846284
11051.2715.4350811752.499.290644 12273.416.1392412353.548.35343312413.6422.35488
12724.56 20.9975 12785.140.5231213118.0934.1358713138.2751.9647813259.3564.83296
13269.4469.6421913279.5496.7555713329.99130.825313410.71101.789613451.95100.9678
#Mann= 3 , 0 , 0
4882.276  0.0482       04882.276  0.0482       013451.95  0.0482       0
#XS Ineff= 2 , 0
       0 9838.91        11767.24       0
Bank Sta=4882.276,13451.95
Exp/Cntr=0.3,0.1

Type RM Length L Ch R = 3 ,15008.67,,,
BEGIN DESCRIPTION:
END DESCRIPTION:
Bridge Culvert--1,0,-1,-1, 0
Deck Dist Width WeirC Skew NumUp NumDn MinLoCord MaxHiCord MaxSubmerge Is_Ogee
208.332450,145.000000,2.6,0, 60, 60, , , 0.95, 0, 0,0,,
 4763.52 4797.79 5018.77 5440.63 5571.20 5741.66 5871.77 6142.00 6262.10 6532.33
 6952.69 7242.94 7523.17 7673.30 7853.45 8393.91 8544.04 8804.26 8874.32 8994.43
 9144.55 9304.69 9454.82 9594.94 9868.44 9868.4410131.5610131.5610185.5110265.60
10415.7610916.4011186.8511487.3511717.7311807.8812008.2212398.8612489.0112599.20
12709.3812779.4912839.5912869.6412879.6612889.6812899.6912909.7112919.7312929.74
12959.7912999.8613009.8813019.8913039.9313049.9413059.9613110.0413280.3313300.85
   46.67   46.78   45.11   41.08   39.52   35.71   33.84   32.09   30.19   28.30
   23.57   21.73   18.96   18.40   18.84   22.25   23.48   26.49   26.69   27.99
   28.74   30.76   29.83   30.45   30.89   30.89   28.39   28.39   27.86   26.08
   23.76   20.03   19.08   22.32   25.73   26.17   28.72   35.59   37.94   39.95
   42.98   43.49   44.79   44.94   42.82   39.45   34.58   29.03   24.37   23.21
   23.38   22.82   24.50   29.57   38.43   42.64   46.17   46.47   45.13   45.32
 -953.33 -953.22 -954.89 -958.92 -960.48 -964.29 -966.16 -967.91 -969.81 -971.70
 -976.43 -978.27 -981.04 -981.60 -981.16 -977.75 -976.52 -973.51 -973.31 -972.01
 -971.26 -969.24 -970.17 -969.55 -969.11   22.89   20.39 -971.61 -972.14 -973.92
 -976.24 -979.97 -980.92 -977.68 -974.27 -973.83 -971.28 -964.41 -962.06 -960.05
 -957.02 -956.51 -955.21 -955.06 -957.18 -960.55 -965.42 -970.97 -975.63 -976.79
 -976.62 -977.18 -975.50 -970.43 -961.57 -957.36 -953.83 -953.53 -954.87 -954.68
 4763.52 4797.79 5018.77 5440.63 5571.20 5741.66 5871.77 6142.00 6262.10 6532.33
 6952.69 7242.94 7523.17 7673.30 7853.45 8393.91 8544.04 8804.26 8874.32 8994.43
 9144.55 9304.69 9454.82 9594.94 9868.44 9868.4410131.5610131.5610185.5110265.60
10415.7610916.4011186.8511487.3511717.7311807.8812008.2212398.8612489.0112599.20
12709.3812779.4912839.5912869.6412879.6612889.6812899.6912909.7112919.7312929.74
12959.7912999.8613009.8813019.8913039.9313049.9413059.9613110.0413280.3313300.85
   46.67   46.78   45.11   41.08   39.52   35.71   33.84   32.09   30.19   28.30
   23.57   21.73   18.96   18.40   18.84   22.25   23.48   26.49   26.69   27.99
   28.74   30.76   29.83   30.45   30.89   30.89   28.39   28.39   27.86   26.08
   23.76   20.03   19.08   22.32   25.73   26.17   28.72   35.59   37.94   39.95
   42.98   43.49   44.79   44.94   42.82   39.45   34.58   29.03   24.37   23.21
   23.38   22.82   24.50   29.57   38.43   42.64   46.17   46.47   45.13   45.32
 -953.33 -953.22 -954.89 -958.92 -960.48 -964.29 -966.16 -967.91 -969.81 -971.70
 -976.43 -978.27 -981.04 -981.60 -981.16 -977.75 -976.52 -973.51 -973.31 -972.01
 -971.26 -969.24 -970.17 -969.55 -969.11   22.89   20.39 -971.61 -972.14 -973.92
 -976.24 -979.97 -980.92 -977.68 -974.27 -973.83 -971.28 -964.41 -962.06 -960.05
 -957.02 -956.51 -955.21 -955.06 -957.18 -960.55 -965.42 -970.97 -975.63 -976.79
 -976.62 -977.18 -975.50 -970.43 -961.57 -957.36 -953.83 -953.53 -954.87 -954.68
Pier Skew, UpSta & Num, DnSta & Num=  ,9955.48, 2 ,9955.48, 2 , 0 , 0 , 0 ,,
    4.00    4.00
 -969.92   30.08
    4.00    4.00
 -969.92   30.08
Pier Skew, UpSta & Num, DnSta & Num=  ,10044.52, 2 ,10044.52, 2 , 0 , 0 , 0 ,,
    4.00    4.00
 -970.78   29.22
    4.00    4.00
 -970.78   29.22
BR Coef=-1 , 0 , 0 ,, 0 ,,,0.8,0,1,0,
WSPro=,,,, 1 ,,,, 0 ,,,, 0 ,,,,-1 ,-1 ,-1 , 0 , 0 , 0 , 0 , 0
BC Design=,, 0 ,, 0 ,,,,,,

Type RM Length L Ch R = 1 ,14674.81,1650.228800,1650.228800,1650.228800
XS GIS Cut Line= 5
 406073.89823097855281.559362337406204.106564343856574.962140113
406299.592675418 860411.76769568406455.842675418863059.337140128
406560.009342074863831.906584561
#Sta/Elev= 30
    453251.466834716.36841.301094887.22746.030265037.98532.844565319.40133.08925
5359.60323.293175450.05830.344975600.81617.980755831.97815.744336542.19816.72199
6602.21711.124316642.22917.943416962.3289.0392267132.38114.970557662.5458.895264
9933.62417.2294110013.76  3.002210113.9415.8525712227.618.18657112348.0114.11339
12378.2818.7268412408.5533.7662312448.9136.2932812630.5417.6797212822.2619.15643
12953.4329.2261512963.5331.65748 12993.859.3531413064.4387.3468513101.67 83.1718
#Mann= 3 , 0 , 0
    4532  0.0473       0    4532  0.0473       013101.67  0.0473       0
#XS Ineff= 2 , 0
       0 9714.43        11457.53       0
Bank Sta=4532,13101.67
Exp/Cntr=0.3,0.1

Type RM Length L Ch R = 1 ,13024.58,204.795400,204.795400,204.795400
XS GIS Cut Line= 4
404599.505869865854793.278112337404734.486040473858194.908025473
405916.669473588863109.413440168406548.290592104863830.278980404
#Sta/Elev= 30
2604.174 30.21773526.62219.17466 3956.9624.314354177.13314.685214537.417  11.919
5758.37712.19443  5788.45.9530715828.43212.819986574.26512.561926625.691 7.00355
6677.11711.473217283.94712.281957325.0887.3743067345.65914.069787561.6499.749443
9937.54213.302999999.2543.39506110050.68 3.9745310102.1114.6804511007.2111.24828
11121.3410.1730211137.085.80717411166.8613.8382911203.568.83595211575.8318.06874
 11849.716.1275311881.6323.1470211921.5244.73261   1198866.6463312021.61 71.9972
#Mann= 3 , 0 , 0
2604.174  0.0451       02604.174  0.0451       012021.61  0.0451       0
#XS Ineff= 2 , 0
       0 8052.79         10942.1       0
Bank Sta=2604.174,12021.61
Exp/Cntr=0.3,0.1

Type RM Length L Ch R = 3 , 12931.8,,,
BEGIN DESCRIPTION:
END DESCRIPTION:
Bridge Culvert--1,0,-1,-1, 0
Deck Dist Width WeirC Skew NumUp NumDn MinLoCord MaxHiCord MaxSubmerge Is_Ogee
91.570950,21.653500,2.6,0, 60, 60, , , 0.95, 0, 0,0,,
 2586.72 2994.22 3044.26 3064.28 3104.32 3124.34 3164.37 3364.55 3474.65 3514.69
 3534.71 3564.73 3674.83 3774.92 3885.02 4095.21 4125.24 4135.25 4145.26 4255.36
 4535.61 4565.64 4575.64 4625.69 4805.85 4835.88 4885.92 4986.01 5076.10 5596.56
 5766.72 5826.77 5866.81 6006.93 9967.06 9967.0610052.0310052.0311072.3811128.27
11142.2411154.8311169.1511197.7811281.9711355.2811519.5111541.4111555.7311613.00
11627.3211645.2611655.9511673.2111684.5911885.0411910.7511952.6712013.9012048.02
   29.80   27.58   26.36   21.43   22.68   19.20   23.82   21.26   25.15   16.75
   16.84   23.46   21.56   25.38   19.01   18.66   15.71   18.11   15.60   13.55
   13.96   10.60   14.21   11.77   13.81   10.80   12.46    9.46   12.92   11.90
    5.77   11.33    8.05   11.41   14.16   14.16   13.95   13.95   12.47    9.47
    5.72    7.56   14.21    9.36    9.29   16.96   22.25   29.04   39.18   51.74
   52.19   46.00   38.43   19.69   17.01   16.02   19.69   40.05   62.21   68.80
 -970.20 -972.42 -973.64 -978.57 -977.32 -980.80 -976.18 -978.74 -974.85 -983.25
 -983.16 -976.54 -978.44 -974.62 -980.99 -981.34 -984.29 -981.89 -984.40 -986.45
 -986.04 -989.40 -985.79 -988.23 -986.19 -989.20 -987.54 -990.54 -987.08 -988.10
 -994.23 -988.67 -991.95 -988.59 -985.84    9.16    8.95 -986.05 -987.53 -990.53
 -994.28 -992.44 -985.79 -990.64 -990.71 -983.04 -977.75 -970.96 -960.82 -948.26
 -947.81 -954.00 -961.57 -980.31 -982.99 -983.98 -980.31 -959.95 -937.79 -931.20
 2586.72 2994.22 3044.26 3064.28 3104.32 3124.34 3164.37 3364.55 3474.65 3514.69
 3534.71 3564.73 3674.83 3774.92 3885.02 4095.21 4125.24 4135.25 4145.26 4255.36
 4535.61 4565.64 4575.64 4625.69 4805.85 4835.88 4885.92 4986.01 5076.10 5596.56
 5766.72 5826.77 5866.81 6006.93 9960.34 9960.3410045.3110045.3111072.3811128.27
11142.2411154.8311169.1511197.7811281.9711355.2811519.5111541.4111555.7311613.00
11627.3211645.2611655.9511673.2111684.5911885.0411910.7511952.6712013.9012048.02
   29.80   27.58   26.36   21.43   22.68   19.20   23.82   21.26   25.15   16.75
   16.84   23.46   21.56   25.38   19.01   18.66   15.71   18.11   15.60   13.55
   13.96   10.60   14.21   11.77   13.81   10.80   12.46    9.46   12.92   11.90
    5.77   11.33    8.05   11.41   14.17   14.17   13.97   13.97   12.47    9.47
    5.72    7.56   14.21    9.36    9.29   16.96   22.25   29.04   39.18   51.74
   52.19   46.00   38.43   19.69   17.01   16.02   19.69   40.05   62.21   68.80
 -970.20 -972.42 -973.64 -978.57 -977.32 -980.80 -976.18 -978.74 -974.85 -983.25
 -983.16 -976.54 -978.44 -974.62 -980.99 -981.34 -984.29 -981.89 -984.40 -986.45
 -986.04 -989.40 -985.79 -988.23 -986.19 -989.20 -987.54 -990.54 -987.08 -988.10
 -994.23 -988.67 -991.95 -988.59 -985.83    9.17    8.97 -986.03 -987.53 -990.53
 -994.28 -992.44 -985.79 -990.64 -990.71 -983.04 -977.75 -970.96 -960.82 -948.26
 -947.81 -954.00 -961.57 -980.31 -982.99 -983.98 -980.31 -959.95 -937.79 -931.20
BR Coef=-1 , 0 , 0 ,, 0 ,,,0.8,0,1,0,
WSPro=,,,, 1 ,,,, 0 ,,,, 0 ,,,,-1 ,-1 ,-1 , 0 , 0 , 0 , 0 , 0
BC Design=,, 0 ,, 0 ,,,,,,

Type RM Length L Ch R = 1 ,12819.79,2151.093400,2151.093400,2151.093400
XS GIS Cut Line= 4
404290.772105724854594.367226034404502.676941037858241.933741555
405743.058362484863178.857884616406541.780175418863830.278980404
#Sta/Elev= 30
2368.59134.949083441.02927.040913491.11318.193873551.21528.22578  3661.413.77818
3871.75414.005563931.85521.115835163.9296.7083865284.13211.750515744.90711.93235
5794.9915.7737016396.65811.84892 6417.285.6657139386.78814.560899943.57113.41138
9984.8143.39788610046.6813.16373 11201.5 7.2288511231.3114.5578911463.5914.08026
11489.3920.0356611517.9470.6949411528.1179.3348811553.9181.1925811597.0579.37015
11644.2442.7512511723.6219.1678511966.8515.0696612018.4621.5410512143.3567.21948
#Mann= 3 , 0 , 0
2368.591  0.0419       02368.591  0.0419       012143.35  0.0419       0
#XS Ineff= 2 , 0
       08054.114        11148.67       0
Bank Sta=2368.591,12143.35
Exp/Cntr=0.3,0.1

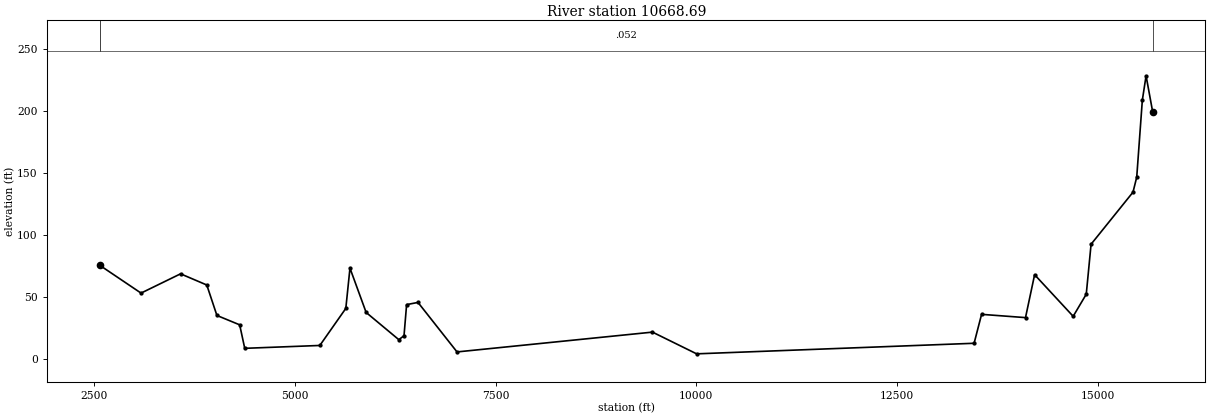
Type RM Length L Ch R = 1 ,10668.69,171.998000,171.998000,171.998000
XS GIS Cut Line= 6
399467.589437485856146.313693896403685.258713156861278.339335248
403989.657132715861814.475967541   404234.122639862141.067268133
405228.661490887  863451.0823908 408496.50127244865398.186670482
#Sta/Elev= 30
2568.04275.536423083.70953.008273575.95568.575493902.70259.543154028.70134.94547
4312.19927.372024375.1988.4001195310.41910.714075634.01340.632925685.78873.16005
5887.18537.369516294.14515.393516358.86418.565776391.18143.70288 6532.9345.47821
7018.9965.4926159453.33621.4874910003.133.94639113458.9112.4796813552.0335.84703
14099.1433.2018814212.5467.87216 14692.834.2540314855.7752.1006114915.8592.48787
 15437.8 134.52215484.36146.6816 15554.2208.836515600.77228.5399   15684199.0031
#Mann= 3 , 0 , 0
2568.042   0.052       02568.042   0.052       0   15684   0.052       0
#XS Ineff= 2 , 0
       09840.698        12427.96       0
Bank Sta=2568.042,15684
Exp/Cntr=0.3,0.1