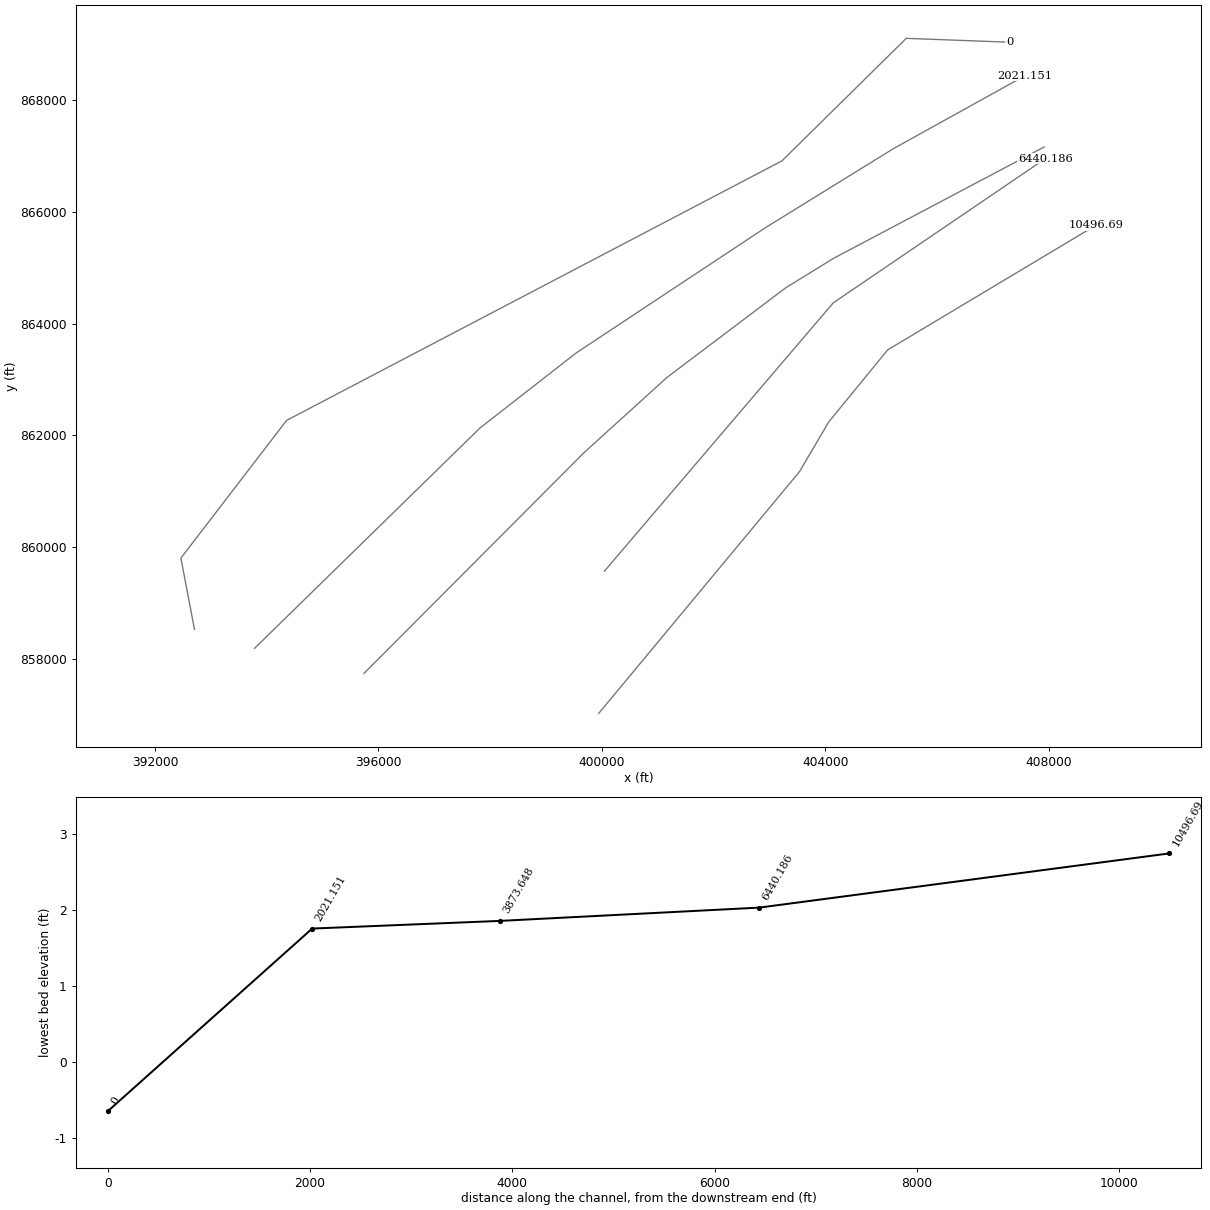
HEC-RAS study 7132_ras.prj: 7132

--- 7132_ras.g01 (geometry) --- (continued)

Type RM Length L Ch R = 3 , 10577.4,,,
BEGIN DESCRIPTION:
END DESCRIPTION:
Bridge Culvert--1,0,-1,-1, 0
Deck Dist Width WeirC Skew NumUp NumDn MinLoCord MaxHiCord MaxSubmerge Is_Ogee
59.752350,52.493300,2.6,0, 60, 60, , , 0.95, 0, 0,0,,
 8945.02 8961.16 8984.92 9015.03 9041.42 9054.80 9060.20 9068.18 9075.25 9090.31
 9105.36 9165.58 9192.28 9545.33 9770.76 9935.20 9935.2010064.8010064.8010157.60
10533.9411059.0811188.6111335.1111892.2211911.8111930.7711942.4011951.0012186.12
12205.7112225.3012361.0312372.6612477.3212570.3512597.5712617.1612686.6412768.04
12779.6612791.2912793.5012813.0912832.6912872.6912907.5813000.6113035.4913105.27
13151.7813186.6713430.8713459.6613535.5313570.4113593.6713605.3013616.9313674.65
   75.07   70.10   66.18   58.90   58.03   47.16   41.80   29.60   23.71   19.77
   18.40   19.13   18.43   19.67   19.39   18.29   18.29   17.65   17.65   16.64
   15.48   12.26   12.43   11.11   10.20    4.67    7.05   10.13   10.74   10.87
   11.64   11.21   12.73   12.25   12.92   12.02   13.07    9.96    8.91   10.29
   11.29   14.88   14.95   11.95   11.63   12.59   11.83   12.84   11.69   11.67
   12.74   11.79   11.84   12.58   12.61   14.10   28.57   31.81   33.86   34.68
 -924.93 -929.90 -933.82 -941.10 -941.97 -952.84 -958.20 -970.40 -976.29 -980.23
 -981.60 -980.87 -981.57 -980.33 -980.61 -981.71   10.79   10.15 -982.35 -983.36
 -984.52 -987.74 -987.57 -988.89 -989.80 -995.33 -992.95 -989.87 -989.26 -989.13
 -988.36 -988.79 -987.27 -987.75 -987.08 -987.98 -986.93 -990.04 -991.09 -989.71
 -988.71 -985.12 -985.05 -988.05 -988.37 -987.41 -988.17 -987.16 -988.31 -988.33
 -987.26 -988.21 -988.16 -987.42 -987.39 -985.90 -971.43 -968.19 -966.14 -965.32
 8945.02 8961.16 8984.92 9015.03 9041.42 9054.80 9060.20 9068.18 9075.25 9090.31
 9105.36 9165.58 9192.28 9545.33 9770.76 9915.05 9915.0510044.6510044.6510157.60
10533.9411059.0811188.6111335.1111892.2211911.8111930.7711942.4011951.0012186.12
12205.7112225.3012361.0312372.6612477.3212570.3512597.5712617.1612686.6412768.04
12779.6612791.2912793.5012813.0912832.6912872.6912907.5813000.6113035.4913105.27
13151.7813186.6713430.8713459.6613535.5313570.4113593.6713605.3013616.9313674.65
   75.07   70.10   66.18   58.90   58.03   47.16   41.80   29.60   23.71   19.77
   18.40   19.13   18.43   19.67   19.39   18.38   18.38   17.75   17.75   16.64
   15.48   12.26   12.43   11.11   10.20    4.67    7.05   10.13   10.74   10.87
   11.64   11.21   12.73   12.25   12.92   12.02   13.07    9.96    8.91   10.29
   11.29   14.88   14.95   11.95   11.63   12.59   11.83   12.84   11.69   11.67
   12.74   11.79   11.84   12.58   12.61   14.10   28.57   31.81   33.86   34.68
 -924.93 -929.90 -933.82 -941.10 -941.97 -952.84 -958.20 -970.40 -976.29 -980.23
 -981.60 -980.87 -981.57 -980.33 -980.61 -981.62   10.88   10.25 -982.25 -983.36
 -984.52 -987.74 -987.57 -988.89 -989.80 -995.33 -992.95 -989.87 -989.26 -989.13
 -988.36 -988.79 -987.27 -987.75 -987.08 -987.98 -986.93 -990.04 -991.09 -989.71
 -988.71 -985.12 -985.05 -988.05 -988.37 -987.41 -988.17 -987.16 -988.31 -988.33
 -987.26 -988.21 -988.16 -987.42 -987.39 -985.90 -971.43 -968.19 -966.14 -965.32
BR Coef=-1 , 0 , 0 ,, 0 ,,,0.8,0,1,0,
WSPro=,,,, 1 ,,,, 0 ,,,, 0 ,,,,-1 ,-1 ,-1 , 0 , 0 , 0 , 0 , 0
BC Design=,, 0 ,, 0 ,,,,,,

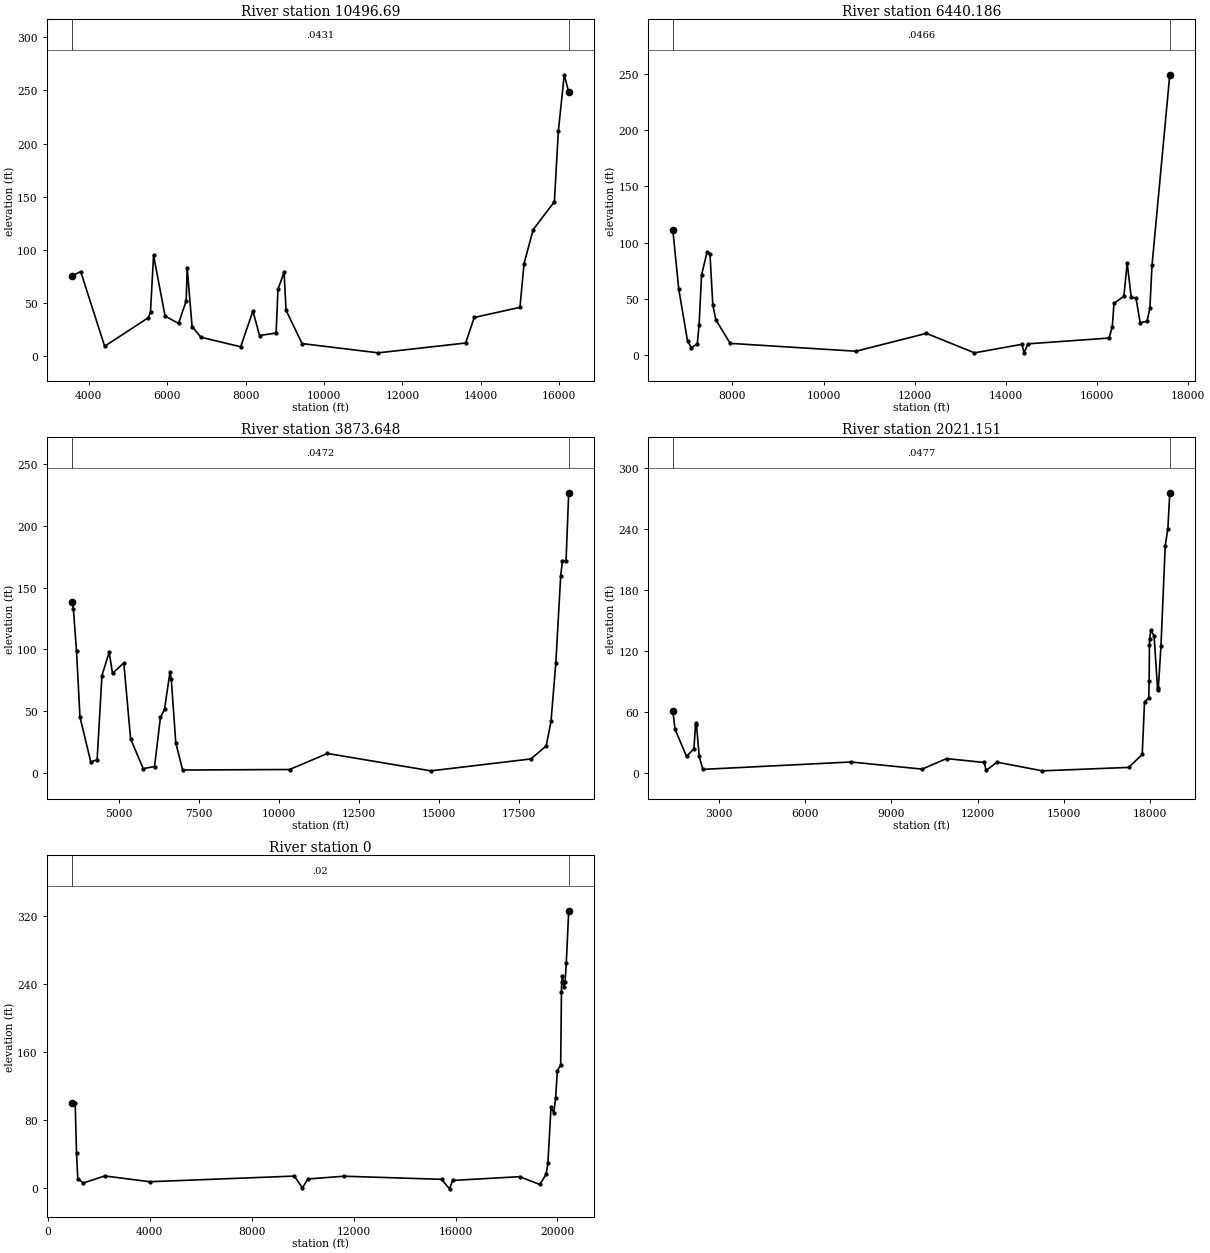
Type RM Length L Ch R = 1 ,10496.69,4056.508400,4056.508400,4056.508400
XS GIS Cut Line= 5
399945.019993097857020.879666105403538.991352022861348.000793591
404064.164963126862239.927876905405118.852463096863528.990376934
408852.370453209865762.708089188
#Sta/Elev= 30
3566.19875.091863792.54479.343434403.5168.9348655521.46535.954145573.46241.65154
5651.45994.61442 5945.1537.42276 6288.4330.429556483.42151.661596509.41982.82002
6633.80327.544956860.40317.439797874.3568.4591568186.34242.135838355.33419.07347
8778.01921.413648824.97262.488938981.484 78.84889031.30342.978079439.54511.45975
11382.742.73995313611.9712.0014713833.3836.0653214998.6945.6311215103.5786.88085
15336.63118.8985 15876.9145.096515977.55211.423216129.04264.774416242.51248.4511
#Mann= 3 , 0 , 0
3566.198  0.0431       03566.198  0.0431       016242.51  0.0431       0
#XS Ineff= 2 , 0
       09883.232        12547.17       0
Bank Sta=3566.198,16242.51
Exp/Cntr=0.3,0.1

Type RM Length L Ch R = 1 ,6440.186,2566.537700,2566.537700,2566.537700
XS GIS Cut Line= 3
 400046.86179911859567.586100837404142.726180543864369.708020737
 407937.48679911866950.398600851
#Sta/Elev= 30
6694.531110.66566822.56658.805067015.26712.666687098.5776.6021877230.011 9.92768
7269.44126.987337323.46171.177827446.73991.951487508.37889.667827570.01744.58945
7637.45631.281247952.89810.4209610713.01 3.4647512254.5719.3109213311.232.029944
14351.269.60129314399.632.02679714484.2810.0229816262.0115.1483916334.5724.99464
16370.8545.8841616588.5352.3253816661.0981.65143 16749.951.2708316854.5850.69517
16945.5128.7049717096.4530.06394 17158.941.5185117205.2979.6668717595.28248.9281
#Mann= 3 , 0 , 0
6694.531  0.0466       06694.531  0.0466       017595.28  0.0466       0
#XS Ineff= 2 , 0
       0 8717.82        14621.65       0
Bank Sta=6694.531,17595.28
Exp/Cntr=0.3,0.1

Type RM Length L Ch R = 1 ,3873.648,1852.497500,1852.497500,1852.497500
XS GIS Cut Line= 6
395741.042969167857734.857246786399686.355469197861693.190580115
401164.870453209863033.541422531403289.870453358864637.708089188
404146.674212933865166.164053276407918.175808549867160.208622262
#Sta/Elev= 30
3533.795138.51593581.896132.97873681.05598.608323788.13645.28168 4126.998.939153
4324.65410.934894474.32278.83369 4700.9797.718344804.69780.690145157.66989.06183
5369.45227.732785763.3823.6140876117.7545.3441226301.67145.02902 6429.16 51.6251
6599.14681.667026640.153 75.89826781.34224.37951 6995.782.51309510335.47 2.92404
11519.2615.8848814750.121.85189817872.5411.4710318351.5221.9714218500.9541.81334
18652.6489.2697618804.32159.730118858.77171.659318971.49171.781119053.97226.5875
#Mann= 3 , 0 , 0
3533.795  0.0472       03533.795  0.0472       019053.97  0.0472       0
#XS Ineff= 2 , 0
       07673.317        16130.74       0
Bank Sta=3533.795,19053.97
Exp/Cntr=0.3,0.1

Type RM Length L Ch R = 1 ,2021.151,2021.151000,2021.151000,2021.151000
XS GIS Cut Line= 6
393782.101996958858184.191737533397818.560330302862129.504237518
399542.896155238863474.984300524402929.660324097  865716.5112755
405223.063101888867132.309886619407572.855641216868434.768555015
#Sta/Elev= 30
1400.27660.751681472.96442.854721873.54416.02636 2131.0623.479662188.28547.25109
2215.36448.706812317.04315.899882439.098 3.184157589.97610.4638810065.253.458209
10913.1513.8176412220.269.99306812293.852.13577512663.9610.3236514242.081.751299
17248.235.140495   1771717.8779217797.0369.5478317945.67 73.7594 17957.190.03468
17968.53125.8059 17974.1131.769318015.36139.9657 18128.6134.950218254.3780.94038
18277.2482.95435 18368.7124.551518517.34223.606818608.81240.176818674.95275.5827
#Mann= 3 , 0 , 0
1400.276  0.0477       01400.276  0.0477       018674.95  0.0477       0
#XS Ineff= 2 , 0
       05253.077        15709.71       0
Bank Sta=1400.276,18674.95
Exp/Cntr=0.3,0.1

Type RM Length L Ch R = 1 ,       0,0.000000,0.000000,0.000000
XS GIS Cut Line= 6
392707.796441406858524.643126398392464.740885854  859800.6847931
394357.101996988862265.962570846403226.535324037866913.125858843
405450.851996958869106.240348637407299.810330302869036.795904189
#Sta/Elev= 30
940.8863100.48531073.587100.12381124.48641.171331175.38511.45203 1389.166.156756
2234.08314.479534000.7137.705518  9676.314.333989993.5640.21112810200.3110.93819
11626.6614.1767415450.9510.5190515766.43-0.6516215886.229.20848918513.6613.61165
 19307.34.48885719557.4816.4527319627.5329.8297319747.6195.0812719857.6988.43582
19927.74105.831919997.79137.721620127.88145.0777 20157.9230.530920167.91241.8702
20197.93248.865220257.97236.5549   20298 242.08220348.03264.284120442.91325.8371
#Mann= 3 , 0 , 0
940.8863    0.02       0940.8863    0.02       020442.91    0.02       0
#XS Ineff= 2 , 0
       06022.013        17398.61       0
Bank Sta=940.8863,20442.91
Exp/Cntr=0.3,0.1